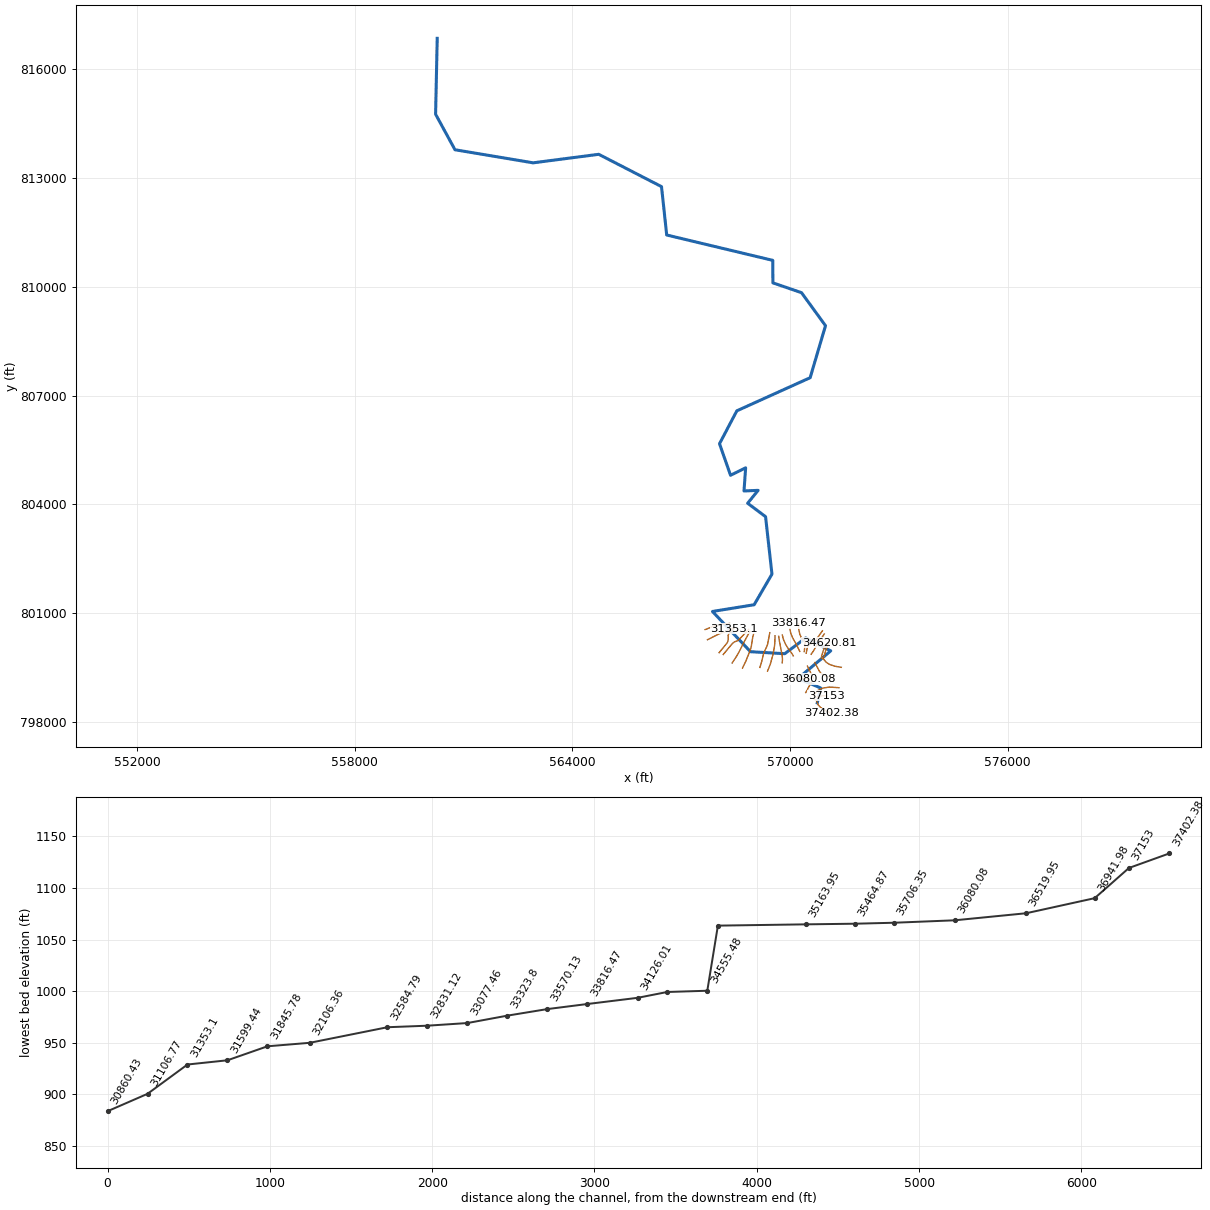
--- 11081_ras.prj (project) ---

Proj Title=11081
Current Plan=p01
Default Exp/Contr=0.3,0.1
English Units
Geom File=g01
Flow File=f01
Plan File=p01
Y Axis Title=Elevation
X Axis Title(PF)=Main Channel Distance
X Axis Title(XS)=Station
BEGIN DESCRIPTION:
RFD model 11081 exported to HEC-RAS
END DESCRIPTION:

--- 11081_ras.p01 (plan) ---

Plan Title=Plan 01
Program Version=4.10
Short Identifier=Plan 01
Geom File=g01
Flow File=f01
Subcritical Flow
Calc Critical at every XS
Secant Critical Depth

--- 11081_ras.f01 (steady flow) ---

Flow Title=Flow 01
Program Version=5.01
Number of Profiles= 6
Profile Names=10yr,25yr,50yr,100yr,100plus,500yr
River Rch & RM=11081,121,37402.38
 4630.14 7439.3810099.6912490.8118236.5919755.85
River Rch & RM=11081,121,   37153
 4632.39 7443.1210104.8912497.3918246.1819765.24
River Rch & RM=11081,121,36941.98
 4669.72 7505.5910191.9812607.5118406.9719923.11
River Rch & RM=11081,121,36519.95
  4674.2 7513.0610202.3812620.6418426.1419941.84
River Rch & RM=11081,121,36080.08
 4691.52 7541.7910242.2112670.7718499.3220012.77
River Rch & RM=11081,121,35706.35
 4695.61 7548.61 10251.712682.7618516.84 20029.9
River Rch & RM=11081,121,35464.87
 4698.38 7553.2510258.1612690.9318528.7620041.58
River Rch & RM=11081,121,35163.95
 4702.07 7559.4210266.7712701.8118544.6520057.15
River Rch & RM=11081,121,34620.81
    4742 7626.3510360.1612820.0218717.2220226.53
River Rch & RM=11081,121,34555.48
 4743.66 7629.1210364.03 12824.918724.3620233.51
River Rch & RM=11081,121,34309.14
 4745.87 7632.8210369.1812831.4218733.8720242.82
River Rch & RM=11081,121,34126.01
 4748.82 7637.7410376.05 12840.118746.5520255.22
River Rch & RM=11081,121,33816.47
 4756.35 7650.3610393.6312862.3418779.02   20287
River Rch & RM=11081,121,33570.13
 4766.15 7666.7210416.4212891.1418821.0720328.05
River Rch & RM=11081,121, 33323.8
  4769.9 7672.9610425.0912902.0718837.0220343.53
River Rch & RM=11081,121,33077.46
 4776.11 7683.2910439.4212920.1218863.3720369.06
River Rch & RM=11081,121,32831.12
 4781.57 7692.3510452.0112935.9818886.5320391.49
River Rch & RM=11081,121,32584.79
 4788.34 7703.6110467.6312955.6618915.2620419.32
River Rch & RM=11081,121,32106.36
 4803.55 7728.8810502.7312999.8918979.8420481.88
River Rch & RM=11081,121,31845.78
 4806.01 7732.9610508.3813007.0118990.2320491.91
River Rch & RM=11081,121,31599.44
 4810.41 7740.2410518.4613019.6619008.7120509.66
River Rch & RM=11081,121, 31353.1
 4811.95 7742.7910521.9713024.0719015.1420515.83
River Rch & RM=11081,121,31106.77
 5099.53 8215.5811173.9913840.69 20207.421647.67
River Rch & RM=11081,121,30860.43
 5171.08 8333.0611335.8814043.2920503.2121926.42
River Rch & RM=11081,121,30614.09
 5173.51 8337.0911341.4614050.3120513.4521936.19
River Rch & RM=11081,121,30367.76
 5221.54 8416.1211450.5214186.9720712.9722124.46
River Rch & RM=11081,121,30121.42
 5234.66 8437.8411480.5814224.7520768.1422176.86
River Rch & RM=11081,121,29875.08
 5236.72 8441.2411485.2914230.6820776.7922185.09
River Rch & RM=11081,121,29628.75
  5239.7 8446.1811492.1414239.2920789.3722197.06
River Rch & RM=11081,121,29382.41
 5252.36 8467.1611521.2214275.8820842.7822247.89
River Rch & RM=11081,121,29136.07
 5260.25 8480.2911539.4714298.8820876.3722280.01
River Rch & RM=11081,121,28889.74
 5265.36  8488.811551.3114313.8220898.1822300.92
River Rch & RM=11081,121, 28643.4
 5282.25 8516.9811590.5314363.3520970.48 22370.3
River Rch & RM=11081,121,28397.06
 5285.16 8521.8411597.2914371.8720982.9422382.23
River Rch & RM=11081,121,28150.73
 5286.44 8523.9611600.24 14375.620988.3822387.45
River Rch & RM=11081,121,27904.39
 5306.84 8558.0511647.7314435.6121075.9922471.62
River Rch & RM=11081,121,27658.05
 5325.08 8588.3511689.7814488.5721153.3122545.25
River Rch & RM=11081,121,27411.72
 5333.72  8602.7 11709.714513.6721189.9622580.18
River Rch & RM=11081,121,27165.38
 5360.95 8648.1811773.0514593.7221306.8322692.24
River Rch & RM=11081,121,26919.04
 5363.32 8652.1211778.5414600.6421316.9322701.88
River Rch & RM=11081,121, 26672.7
  5377.4 8675.5411811.0714641.6521376.8122758.93
River Rch & RM=11081,121,26426.37
 5381.05 8681.6211819.5114652.2921392.3422773.74
River Rch & RM=11081,121,26180.03
 5381.78 8682.83 11821.214654.4221395.4522776.71
River Rch & RM=11081,121,25703.93
 5408.74 8727.7111883.5814733.08 21510.322886.17
River Rch & RM=11081,121,25227.83
 5417.34    874211903.4214758.08 21546.822920.89
River Rch & RM=11081,121,24751.73
 5419.18 8745.0511907.6614763.4221554.5922928.28
River Rch & RM=11081,121,24275.63
 5429.24 8761.7811930.8814792.6821597.3222968.88
River Rch & RM=11081,121,23799.53
 5435.33 8771.8611944.8714810.2821623.0122993.22
River Rch & RM=11081,121,23323.43
 5502.33 8882.7912098.5515003.5221905.1423259.63
River Rch & RM=11081,121,22847.33
 5508.06 8892.2812111.6915020.0521929.2823282.39
River Rch & RM=11081,121,22371.23
 5513.42 8901.1612123.9915035.5121951.8523303.67
River Rch & RM=11081,121,21895.13
 5518.78 8910.0312136.2815050.9621974.4123324.95
River Rch & RM=11081,121,21419.03
 5593.68 9033.9512307.8715266.6422289.2923621.27
River Rch & RM=11081,121,21194.21
 5594.79 9035.7912310.4215269.8422293.9623625.64
River Rch & RM=11081,121,20942.93
 5609.46  9060.112344.1315312.26 22355.9   23684
River Rch & RM=11081,121,20693.55
 5614.98 9069.2312356.7915328.1722379.1323705.87
River Rch & RM=11081,121,20444.16
 5625.12 9086.0112380.0215357.3822421.7823745.94
River Rch & RM=11081,121,20194.78
 5629.35 9093.0312389.7415369.5922439.6123762.69
River Rch & RM=11081,121,19945.39
 5630.46 9094.8612392.2715372.7822444.2623767.06
River Rch & RM=11081,121,19696.51
 5634.53 9101.5812401.5815384.4722461.3323783.07
River Rch & RM=11081,121,19450.38
 5644.13 9117.4612423.57 15412.122501.6623820.91
River Rch & RM=11081,121,19219.75
 5649.86 9126.9312436.6715428.56 22525.723843.46
River Rch & RM=11081,121,18963.57
 5651.14 9129.0612439.6215432.2722531.1223848.55
River Rch & RM=11081,121,18714.19
 5660.85 9145.1412461.9215460.3322572.0823887.07
River Rch & RM=11081,121,18427.83
 5740.71 9277.8412646.1815692.4822911.0324206.68
River Rch & RM=11081,121,18215.42
 5745.27  9285.412656.6515705.6622930.2724224.75
River Rch & RM=11081,121,17966.03
 5752.17 9296.8612672.5515725.6722959.4824252.21
River Rch & RM=11081,121,17716.65
 5754.52 9300.7512677.96 15732.522969.44 24261.6
River Rch & RM=11081,121,17502.81
 5756.68 9304.3512682.9615738.7922978.6424270.26
River Rch & RM=11081,121,17413.55
 5761.03 9311.5712692.9815751.4122997.0624287.59
River Rch & RM=11081,121,17217.88
 7258.8111814.9516182.6420162.8529437.7630287.53
River Rch & RM=11081,121,16988.11
 7260.3511817.51 16186.220167.3429444.3230293.49
River Rch & RM=11081,121,16758.34
 7267.0311828.6216201.64 20186.829472.72 30319.3
River Rch & RM=11081,121,16528.57
 7275.26 11842.316220.6420210.7529507.6930351.05
River Rch & RM=11081,121, 16298.8
 7277.6611846.2916226.1820217.7329517.8830360.31
River Rch & RM=11081,121,16099.61
 7282.4811854.2816237.2920231.71 29538.330378.83
River Rch & RM=11081,121,15843.02
 7284.8811858.2716242.83 20238.7 29548.530388.08
River Rch & RM=11081,121,15599.22
 7294.1411873.66 16264.220265.6329587.8230423.77
River Rch & RM=11081,121,15369.45
 7303.2411888.7716285.1920292.0729626.4330458.79
River Rch & RM=11081,121,15139.68
 7373.3612004.3116444.8320492.26 29918.730720.56
River Rch & RM=11081,121,14904.86
 7401.0412050.0816508.2220571.9130034.9930825.15
River Rch & RM=11081,121,14670.05
 7406.2312058.6816520.14 20586.930056.8730844.87
River Rch & RM=11081,121,14435.23
  7410.912066.4116530.8620600.3830076.5630862.62
River Rch & RM=11081,121,13965.59
 7454.1612137.7216629.4220724.0230257.0631024.09
River Rch & RM=11081,121,13505.08
 7506.5312224.2716749.2520874.5430476.8231221.22
River Rch & RM=11081,121, 13318.6
 7526.2512256.8216794.2820931.0730559.36 31295.1
River Rch & RM=11081,121,12469.28
  7549.612295.3816847.6320998.0530657.1631382.62
River Rch & RM=11081,121,12224.38
 7554.1212302.8416857.9621011.0430676.1131399.59
River Rch & RM=11081,121,11979.49
 7558.6512310.3316868.3221024.0330695.0831416.56
River Rch & RM=11081,121,11734.59
 7560.0412312.62 16871.521028.0230700.9131421.78
River Rch & RM=11081,121, 11489.7
 7561.2612314.6316874.2821031.5230706.0231426.35
River Rch & RM=11081,121,11244.81
 7703.3212547.0917194.0721430.8931289.1131940.12
River Rch & RM=11081,121,10755.02
 8064.6413143.6218019.4422467.0632801.9133284.66
River Rch & RM=11081,121,10280.43
 8071.8313155.51 18035.922487.7532832.1133311.44
River Rch & RM=11081,121,10049.61
 8073.3713158.0618039.4322492.1832838.5833317.18
River Rch & RM=11081,121,9530.548
 8344.4913601.09 18648.423252.0733948.0234282.19
River Rch & RM=11081,121, 9040.76
 8347.5513606.1518655.4123260.8733960.8734293.54
River Rch & RM=11081,121,8795.866
 8355.5313619.3518673.6923283.8433994.4134323.16
River Rch & RM=11081,121,8550.972
 8417.3413721.0818814.1923459.8934251.4534548.49
River Rch & RM=11081,121,8061.184
 8425.7613735.0418833.5423484.2334286.9734579.91
River Rch & RM=11081,121, 7816.29
 8432.8413746.7618849.7823504.6734316.81 34606.3
River Rch & RM=11081,121,7571.396
  8440.613759.61 18867.623527.0734349.5234635.19
River Rch & RM=11081,121,7326.502
 9424.6915373.9121092.26 26309.238411.4338145.57
River Rch & RM=11081,121,7190.361
 9425.5115375.2721094.1526311.58 38414.938148.59
River Rch & RM=11081,121, 6462.03
 9443.0115404.3221134.4826362.3638489.0438213.27
River Rch & RM=11081,121,6097.865
 9470.5515449.9921197.8626442.1338605.5138314.71
River Rch & RM=11081,121,5955.458
 9471.04 15450.821198.9926443.5538607.5938316.52
River Rch & RM=11081,121,5667.109
 9488.5815479.8821239.3526494.3538681.7538381.08
River Rch & RM=11081,121, 5378.76
 9497.0615493.9621258.9126518.97 38717.738412.45
River Rch & RM=11081,121, 5090.41
 9498.8415496.9321263.0426524.18 38725.338419.07
River Rch & RM=11081,121,4969.111
 9499.1715497.4721263.7826525.1238726.6838420.28
River Rch & RM=11081,121, 4503.85
 9725.2815872.4721784.2427180.1339682.99 39251.2
River Rch & RM=11081,121,4038.588
 9746.8315908.2721833.9827242.7739774.4539330.69
River Rch & RM=11081,121,3573.326
 9787.4615975.7621927.7427360.89 39946.939480.52
River Rch & RM=11081,121,3108.065
 9790.0315980.0421933.69 27368.439957.8639490.07
River Rch & RM=11081,121,785.5793
 9785.5315972.5521923.2727355.2639938.6839473.36
Boundary for River Rch & Prof#=11081,121,1
Up Type= 0
Dn Type= 2
Boundary for River Rch & Prof#=11081,121,2
Up Type= 0
Dn Type= 2
Boundary for River Rch & Prof#=11081,121,2
Up Type= 0
Dn Type= 2
Boundary for River Rch & Prof#=11081,121,2
Up Type= 0
Dn Type= 2
Boundary for River Rch & Prof#=11081,121,2
Up Type= 0
Dn Type= 2
Boundary for River Rch & Prof#=11081,121,2
Up Type= 0
Dn Type= 2

--- 11081_ras.g01 (geometry) ---

Geom Title=11081
Program Version=4.10

River Reach=11081,121
Reach XY= 30
570754.866003752798527.317842513570845.785889149 798936.67385155
  570222.6648193799198.492954969571124.826113701 799959.51606141
570435.017645031800316.513256043569856.419166237  799881.1633683
 568911.69070065 799936.93324323567863.514796734801045.890223637
569013.017649233801231.466997832569504.041298151802075.660932481
569327.518282503803658.858163923568833.334670544804029.957574204
  569122.9104065804385.119779319 568733.01662904804368.459667608
568778.278685629805006.400811702568362.090154588804801.227692053
568057.820540816 805670.82848233  568535.4471111806578.291686416
570556.907629311807491.436041832570980.521508753808925.741693631
 570318.26705879809835.882185981569530.037020057810106.711396188
 569526.15834102 810727.08876498566601.830358386811426.032870978
566458.659106523812759.947621599564727.672489345813651.092875272
562918.650492996813416.106468633560763.751664996813776.718857661
560229.388743132814756.468503207560274.168149143816848.754725218

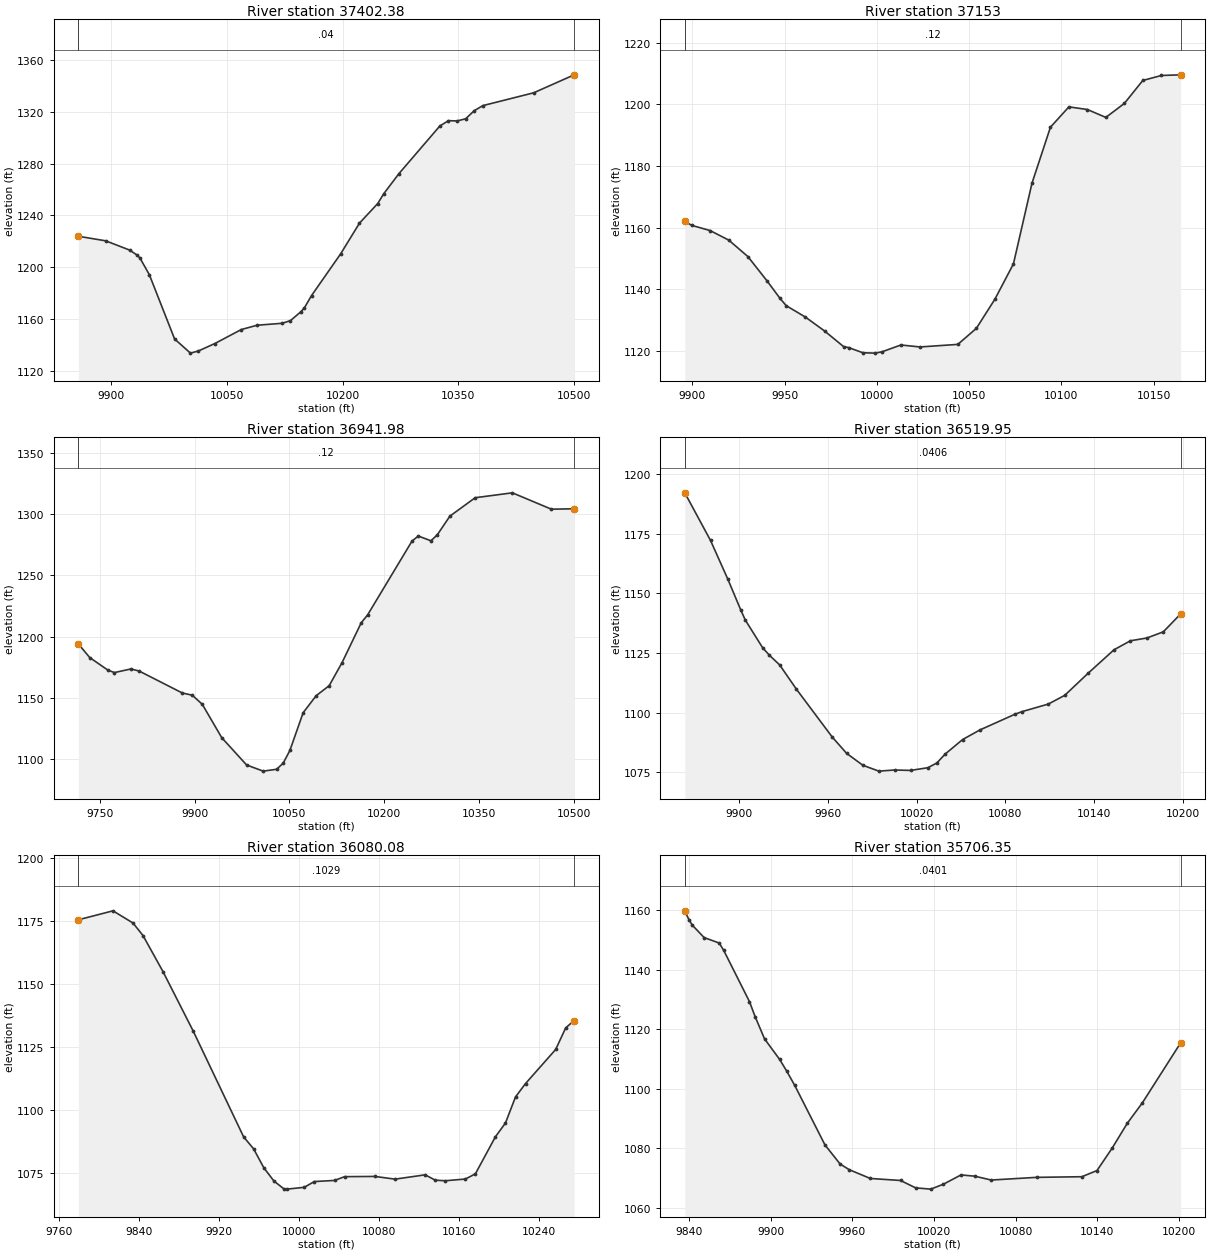
Type RM Length L Ch R = 1 ,37402.38,249.385500,249.385500,249.385500
XS GIS Cut Line= 6
  570666.9664267798629.784854283570729.840200943798587.647587939
570777.226693068798472.699493686570844.522914277798399.122339859
570970.641501364798315.996054329571143.305375901798236.023436376
#Sta/Elev= 30
9856.9691223.8259892.4661220.3029923.6331213.1269933.7751209.0659936.9921206.981
9949.1391194.178 9981.961144.43110002.541133.48110012.871135.15110034.281140.914
10068.531151.70210089.221155.06510121.441156.53810132.351158.57410146.091165.546
10150.611168.58910159.781177.97710197.711210.34610222.05 1233.9910245.721249.109
10253.621256.76110273.21 1272.1910326.461309.11910337.621313.18610348.781312.959
10359.931314.66110371.091320.90810382.251324.82410448.261334.72910500.79 1348.62
#Mann= 3 , 0 , 0
9856.969    0.04       09856.969    0.04       010500.79    0.04       0
#XS Ineff= 2 , 0
       0                               0
Bank Sta=9856.969,10500.79
Exp/Cntr=0.3,0.1

Type RM Length L Ch R = 1 ,   37153,211.015800,211.015800,211.015800
XS GIS Cut Line= 6
570741.357682514798684.569492721570765.787150145798687.748419391
570881.741808831798718.839576562570924.924368292798723.026280517
570980.657753222798721.090734885571005.359480889798718.266899106
#Sta/Elev= 30
9895.9141162.0979899.5871160.7659909.6711159.0599919.7551155.9629930.1151150.632
9940.4971142.7499947.5041137.097 9950.881134.7229961.2631131.0329971.6461126.531
9982.0291121.4359984.6761121.1479992.4111119.465    99991119.34310002.751119.764
10013.061121.98310023.361121.34310043.891122.17510053.931127.37410063.981136.827
10074.03 1148.2810084.071174.41210094.081192.56910104.091199.16110114.091198.299
 10124.11195.742 10134.11200.24910144.141207.715 10154.21209.32710164.631209.541
#Mann= 3 , 0 , 0
9895.914    0.12       09895.914    0.12       010164.63    0.12       0
#XS Ineff= 2 , 0
       0                               0
Bank Sta=9895.914,10164.63
Exp/Cntr=0.3,0.1

Type RM Length L Ch R = 1 ,36941.98,422.031700,422.031700,422.031700
XS GIS Cut Line= 6
570643.514743591798732.276148963570763.090371631798863.669777339
570858.009573161 798912.61339786570925.786634521798935.859124898
 571082.02895557 798960.84176703571350.858201396798944.069857091
#Sta/Elev= 30
9715.9471193.9989734.0311182.818 9763.05 1172.469773.1831170.5779799.2851173.538
9812.335  1171.89880.5651153.8859896.2471152.1039912.1541144.6829942.986 1117.41
9982.3081095.11910008.561090.07910029.871091.58810040.371096.64610050.871106.954
10071.871137.79410092.471151.66410113.061159.85210133.421178.659 10163.81211.209
10173.931217.669 10244.2 1277.94 10254.21282.079 10274.21278.184 10284.21283.025
10304.211298.32910344.241313.36510403.131317.358 10464.81304.00510500.921304.308
#Mann= 3 , 0 , 0
9715.947    0.12       09715.947    0.12       010500.92    0.12       0
#XS Ineff= 2 , 0
       0                               0
Bank Sta=9715.947,10500.92
Exp/Cntr=0.3,0.1

Type RM Length L Ch R = 1 ,36519.95,439.869000,439.869000,439.869000
XS GIS Cut Line= 6
570435.049067835798810.275731836570465.183284108798858.903708871
570491.832493353798909.306403502570506.119804817798945.615962134
570547.796981971799013.792877533 570592.93130132799105.075699082
#Sta/Elev= 30
9863.3491192.0449880.7241172.1049892.474 1155.819901.1651142.9749904.2241138.756
9915.9741127.125 9920.561123.9829927.4561119.9579938.7681109.7949962.9571089.752
9972.7031082.9049983.6981077.9079994.4521075.46610005.161075.93910015.941075.762
 10027.6  1076.910033.631078.86810039.32 1082.6410051.041088.68710062.761092.724
 10086.21099.23610091.141100.38110108.951103.55210120.061107.21210136.071116.587
10153.371126.30310164.471130.07110175.581131.23610186.681133.81510198.371141.313
#Mann= 3 , 0 , 0
9863.349  0.0406       09863.349  0.0406       010198.37  0.0406       0
#XS Ineff= 2 , 0
       0                               0
Bank Sta=9863.349,10198.37
Exp/Cntr=0.3,0.1

Type RM Length L Ch R = 1 ,36080.08,373.725900,373.725900,373.725900
XS GIS Cut Line= 4
570010.371108145799225.280483499570121.482219219799228.752705708
570315.926663667799200.974927947570503.426663667799185.349927947
#Sta/Elev= 30
9779.3241175.375 9813.971178.926 9833.981174.0979843.9851169.1319863.9941154.821
9894.0431131.3849944.5511089.3749954.6521084.5449964.7541077.1119974.8551071.855
9984.957  1068.79987.7361068.63210005.161069.34210015.261071.63410035.461072.078
10045.571073.57110075.871073.66310096.011072.58510126.12  1074.310136.151072.176
10146.19 1071.9510166.261072.62610176.29 1074.6810196.361089.39510206.391094.839
10216.431105.17810226.461110.48210256.571123.982 10266.61132.53110275.061135.452
#Mann= 3 , 0 , 0
9779.324  0.1029       09779.324  0.1029       010275.06  0.1029       0
#XS Ineff= 2 , 0
       0                               0
Bank Sta=9779.324,10275.06
Exp/Cntr=0.3,0.1

Type RM Length L Ch R = 1 ,35706.35,241.484300,241.484300,241.484300
XS GIS Cut Line= 2
570482.593330324799537.780483484570640.579441428799209.655483499
#Sta/Elev= 30
9836.9071159.8789839.9931156.8549842.4551155.0439851.0921150.8849862.1911149.045
9865.5061146.5649884.3881129.3589888.5571124.2939895.4871116.8059906.5861109.885
9911.609 1106.099917.6841101.1339939.882 1081.129950.9811074.7169957.711  1072.8
9973.1781069.8519995.3761069.17710006.471066.68810017.571066.26710026.861067.924
10039.771071.04410049.921070.62110061.971069.32510095.261070.22510128.561070.441
10139.66 1072.5210150.761080.02810161.86 1088.3810172.961095.26810201.091115.457
#Mann= 3 , 0 , 0
9836.907  0.0401       09836.907  0.0401       010201.09  0.0401       0
#XS Ineff= 2 , 0
       0                               0
Bank Sta=9836.907,10201.09
Exp/Cntr=0.3,0.1

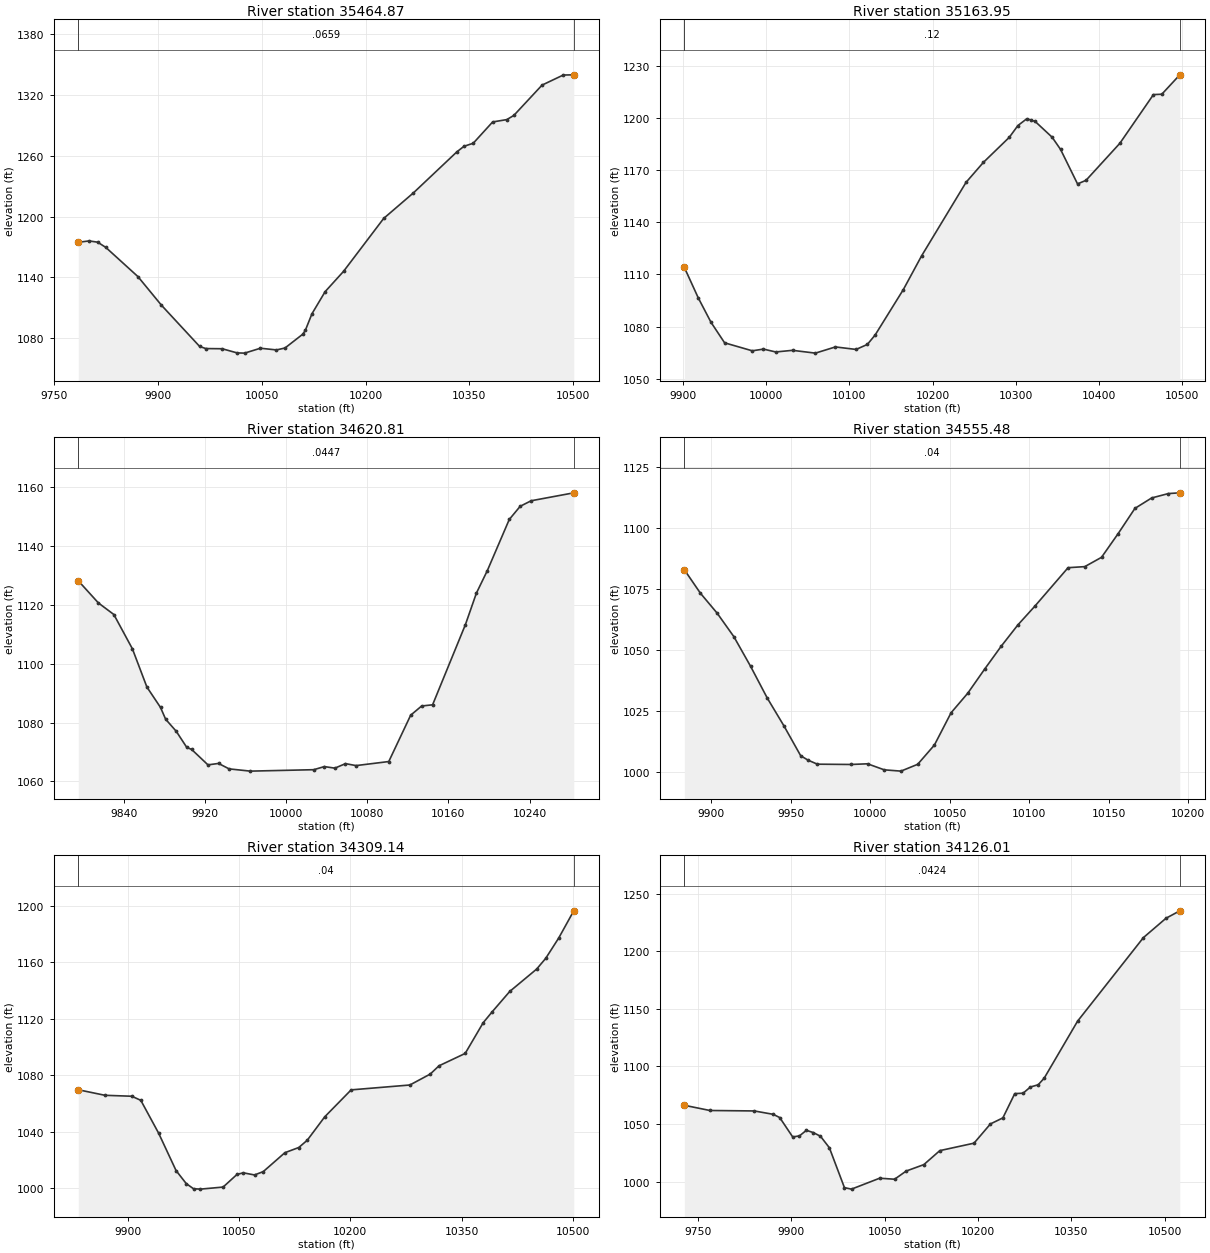
Type RM Length L Ch R = 1 ,35464.87,300.918400,300.918400,300.918400
XS GIS Cut Line= 6
570686.020085216799637.534723514570818.681219896799385.732783441
570869.291344168799327.709573935570922.614957731799291.049504956
570997.975999794799260.461883899571199.899781386 799214.72491621
#Sta/Elev= 30
9784.8571174.675 9800.411176.0149812.8181174.7969824.6251169.5999871.0031140.833
9905.0261112.5699960.2051071.9089969.0611069.8289992.7031069.65210014.311065.551
10025.141065.32210048.031070.15110071.211068.47610083.561070.38310109.321084.061
10112.921087.78510122.521104.17610141.551125.98510168.111145.97310226.151198.217
10269.151223.44610331.961263.93610342.281269.40910355.561272.385 10383.61293.406
10404.031295.71410414.231299.83810455.031329.77310485.631339.69210500.83  1339.9
#Mann= 3 , 0 , 0
9784.857  0.0659       09784.857  0.0659       010500.83  0.0659       0
#XS Ineff= 2 , 0
       0                               0
Bank Sta=9784.857,10500.83
Exp/Cntr=0.3,0.1

Type RM Length L Ch R = 1 ,35163.95,543.145000,543.145000,543.145000
XS GIS Cut Line= 6
570897.784007448 799751.36748324570929.670463832799729.453249102
570995.489442342799647.386558523571087.806490399799587.833686714
571239.616447547799535.597019964571416.436180086799506.092570201
#Sta/Elev= 30
9901.7271113.9739918.5451096.3659933.7421082.4459950.0911070.6389983.3591066.044
9996.8011067.02410011.561065.38210031.721066.31710059.22 1064.71 10083.31068.275
10108.141066.82810121.671069.70710131.011075.11110164.951101.26710186.811120.575
10240.291162.88510261.111174.361 10292.3  1188.810302.691195.58410313.091199.375
10317.891198.83510323.381197.91210343.761188.85510353.951181.79810374.331161.993
10384.521164.076 10425.21185.36410465.541213.35410475.621213.57410497.241224.724
#Mann= 3 , 0 , 0
9901.727    0.12       09901.727    0.12       010497.24    0.12       0
#XS Ineff= 2 , 0
       0                               0
Bank Sta=9901.727,10497.24
Exp/Cntr=0.3,0.1

Type RM Length L Ch R = 1 ,34620.81,65.324300,65.324300,65.324300
XS GIS Cut Line= 4
570868.379614621799755.839345306570936.257072657799800.167481124
570992.338729203799988.750319108 571072.01198855800183.882906809
#Sta/Elev= 30
9794.9931128.1919814.8441120.6519830.0351116.7319848.3241105.0669862.6181092.066
9876.0631085.1189881.1051081.1199891.5381077.0279901.9711071.5219906.7351070.846
9922.8361065.5939933.2691066.0789943.7021064.2289964.5671063.46310027.161063.949
 10037.61065.00610048.031064.47710058.461066.011 10068.91065.34610101.161066.724
10122.761082.48910133.571085.61610144.371086.01910176.771113.32610187.57    1124
10198.371131.67910219.981149.05910230.781153.54510241.58 1155.4210283.581158.117
#Mann= 3 , 0 , 0
9794.993  0.0447       09794.993  0.0447       010283.58  0.0447       0
#XS Ineff= 2 , 0
       0                               0
Bank Sta=9794.993,10283.58
Exp/Cntr=0.3,0.1

Type RM Length L Ch R = 1 ,34555.48,246.336700,246.336700,246.336700
XS GIS Cut Line= 2
570871.150123119799815.405277804570966.732665986800111.849686086
#Sta/Elev= 30
9883.2291082.802 9893.311073.2119903.817 1065.059914.324 1055.439924.8311043.303
9935.3381030.2719945.8441018.8589956.3511006.6519960.9481004.8439966.8581003.184
9987.8721003.0639998.3791003.33910008.891000.87110019.391000.339 10029.9 1003.13
10040.411011.00710050.91 1024.2410061.421032.26710071.931042.04510082.431051.504
10092.941060.24710103.451067.79910124.461083.65210134.971084.08510145.481087.894
10155.981097.64310166.491107.942   101771112.208 10187.51114.003 10194.71114.309
#Mann= 3 , 0 , 0
9883.229    0.04       09883.229    0.04       0 10194.7    0.04       0
#XS Ineff= 2 , 0
       0                               0
Bank Sta=9883.229,10194.7
Exp/Cntr=0.3,0.1

Type RM Length L Ch R = 1 ,34309.14,183.129500,183.129500,183.129500
XS GIS Cut Line= 6
570583.325833156799866.536874535570599.091226512799886.516623043
570641.228585115799948.117192521570690.498966412  800029.2515133
570857.687597796800293.493786239570946.530960426800426.083767725
#Sta/Elev= 30
9833.6641069.603 9869.581065.679 9905.74 1065.019917.855  1062.19941.8331038.829
9965.3251012.2979979.0591003.0569988.818999.4122 9998.12999.137410028.681000.596
10047.311009.513 10055.81010.71510070.981009.18910082.811011.57510111.911024.978
10130.611028.65210141.981033.77510165.651050.46210201.151069.52510280.231072.981
10307.651080.71910319.481086.59210354.751095.36610378.991117.14410390.931124.774
10414.821139.35110450.991155.18310463.161162.75710480.751177.24210500.991196.501
#Mann= 3 , 0 , 0
9833.664    0.04       09833.664    0.04       010500.99    0.04       0
#XS Ineff= 2 , 0
       0                               0
Bank Sta=9833.664,10500.99
Exp/Cntr=0.3,0.1

Type RM Length L Ch R = 1 ,34126.01,309.544000,309.544000,309.544000
XS GIS Cut Line= 6
570448.930651128799894.689806138570474.149977448800032.139180356
570497.256970288800094.656439196570636.517283269800184.291049595
570703.588543546800243.678915767570896.865023875800513.381044711
#Sta/Elev= 30
9728.6961066.2329769.6791061.7149840.848 1061.329871.4121058.3869881.7981055.572
9902.5711038.7919913.4291039.6469924.5961044.5179935.8351042.5129947.1831039.375
9961.4571029.4179985.687994.7373 9997.02993.467810042.191002.94110066.211002.061
10084.891009.17510113.131014.727 10138.81026.87910193.681033.34610220.091050.072
10240.041055.28910259.071076.34610272.591076.74410284.161082.096 10296.71084.019
 10306.31089.71510359.911139.20310465.691211.77410501.89 1228.5410524.071234.995
#Mann= 3 , 0 , 0
9728.696  0.0424       09728.696  0.0424       010524.07  0.0424       0
#XS Ineff= 2 , 0
       0                               0
Bank Sta=9728.696,10524.07
Exp/Cntr=0.3,0.1

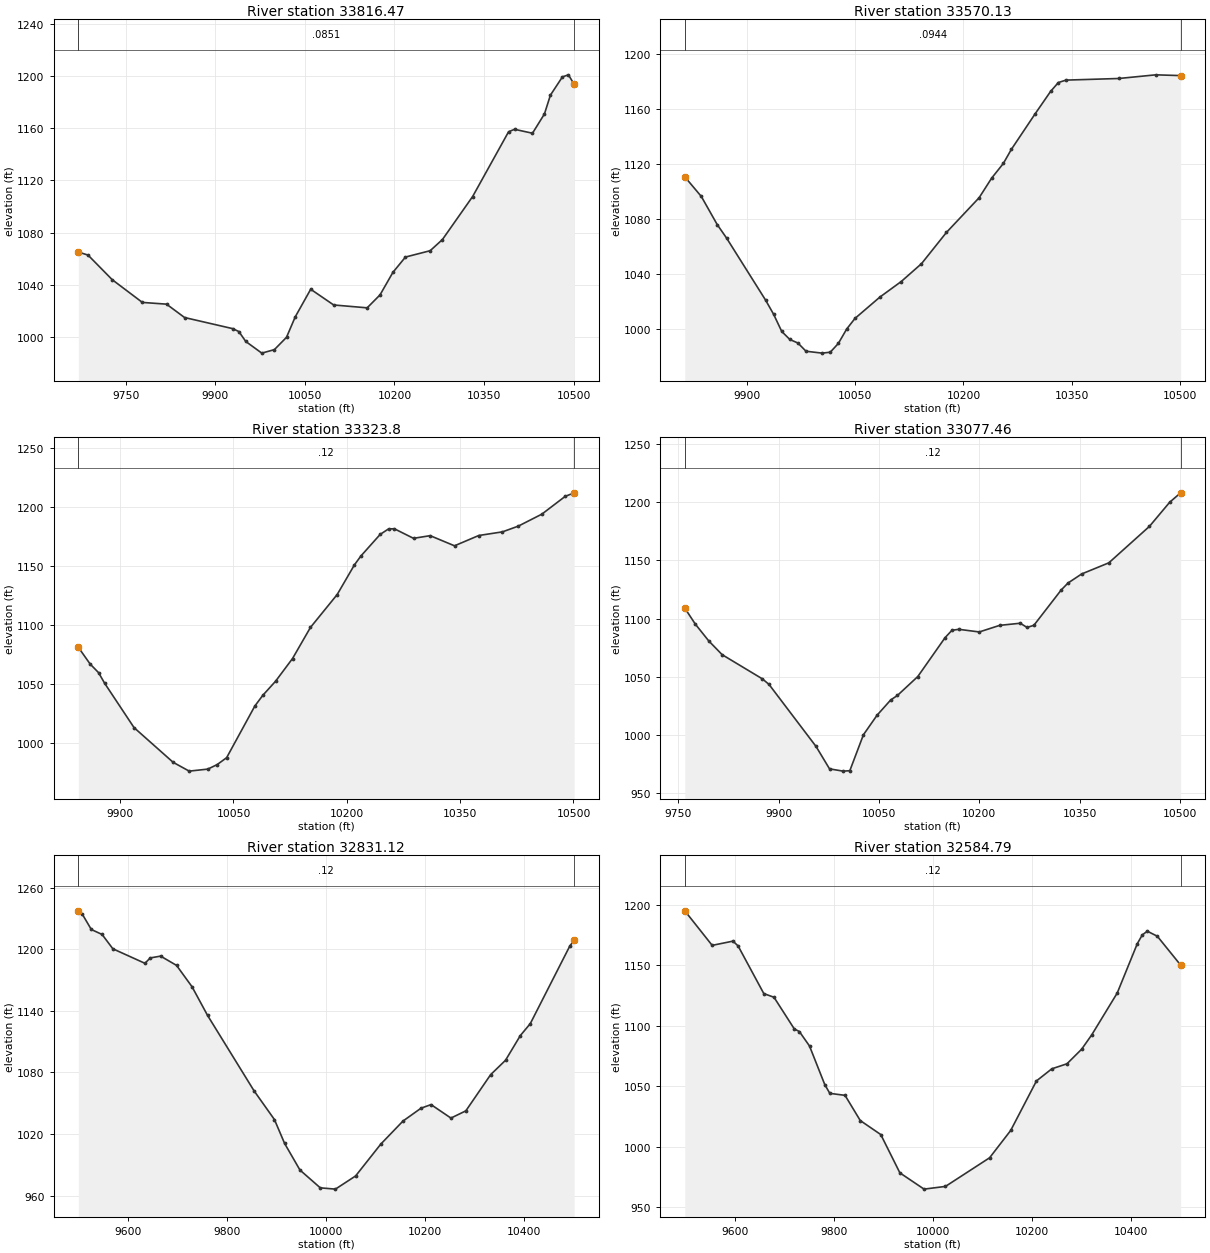
Type RM Length L Ch R = 1 ,33816.47,246.336800,246.336800,246.336800
XS GIS Cut Line= 6
570394.574871021799938.964569305570422.166338728800188.132935259
 570316.96657306800322.242581006570270.638205776800419.402841748
570240.464888037800571.448962718570244.284027683800714.520638535
#Sta/Elev= 30
9670.7621064.9999686.9731062.6849727.4111043.8389777.9581026.3689818.3961025.042
9848.619 1014.78 9929.071006.272  9939.51004.035 9951.05 996.4269977.908987.4712
    9999990.157210019.28999.604910033.97 1015.3610059.781036.46910098.271024.409
 10154.31022.21210175.831032.13710197.371049.396 10218.41061.16510259.791066.036
 10280.31074.588 10330.91107.61210391.05 1157.2710401.051159.15310431.071156.145
10451.091170.929 10461.11185.361 10481.21199.36510491.261200.94510500.841193.679
#Mann= 3 , 0 , 0
9670.762  0.0851       09670.762  0.0851       010500.84  0.0851       0
#XS Ineff= 2 , 0
       0                               0
Bank Sta=9670.762,10500.84
Exp/Cntr=0.3,0.1

Type RM Length L Ch R = 1 ,33570.13,246.336700,246.336700,246.336700
XS GIS Cut Line= 6
570272.119263855799944.161044752570177.313448332800136.698819279
570094.266339784800281.851688378570058.971426545800352.756094909
570019.288717708800460.102589228 569996.53765607800568.963329423
#Sta/Elev= 30
 9814.031110.6199836.9351096.3479858.9181075.9499871.8161066.2099925.9111021.104
9937.1191010.7369948.327998.30329959.535992.47379970.743989.89819981.951983.9293
10004.35982.556410015.56983.232210026.77989.612610038.241000.01110049.761007.751
10084.331023.28510113.881034.57710141.931047.52110176.491070.23510221.77 1095.44
10239.141109.70210255.28 1120.3110266.451130.58810299.18 1156.2510320.821172.692
10331.521179.11410342.07 1180.8810415.211182.05810466.591184.71910500.921184.154
#Mann= 3 , 0 , 0
 9814.03  0.0944       0 9814.03  0.0944       010500.92  0.0944       0
#XS Ineff= 2 , 0
       0                               0
Bank Sta=9814.03,10500.92
Exp/Cntr=0.3,0.1

Type RM Length L Ch R = 1 , 33323.8,246.336800,246.336800,246.336800
XS GIS Cut Line= 6
570090.839099532799820.980862836570062.994853875799872.723007353
569931.794964116800054.697915264569873.881878126800152.692216991
569820.801568942800278.277737563569788.276873783 800396.60419547
#Sta/Elev= 30
9844.6691080.9969860.2811066.8579871.4161059.5589879.5721050.4929918.4021013.034
9970.159983.65619991.407976.199910016.04977.9111 10028.5981.766110040.96987.5832
10078.361031.36910088.961040.45810105.711052.27210128.191071.51610151.871097.792
10187.291125.66910210.111150.76810218.64 1158.2510244.261176.60210255.271181.181
10262.931181.318 10288.31173.22910310.331175.47810342.571166.89810374.641175.612
10406.061178.70610426.95 1183.5410458.191193.699   104891208.70510500.921211.732
#Mann= 3 , 0 , 0
9844.669    0.12       09844.669    0.12       010500.92    0.12       0
#XS Ineff= 2 , 0
       0                               0
Bank Sta=9844.669,10500.92
Exp/Cntr=0.3,0.1

Type RM Length L Ch R = 1 ,33077.46,246.336700,246.336700,246.336700
XS GIS Cut Line= 6
569787.095801063799629.441245524 569793.03079183799718.043678702
569789.602410979799790.381073978569780.634376747799862.609121545
569709.643456907800225.560807029 569689.85716333800361.211411599
#Sta/Elev= 30
9759.9541108.9629775.6081095.2729795.729 1080.819815.759 1068.999875.8071048.243
9885.8181043.4539956.124 990.1819976.277970.96199996.444969.021210006.59969.3818
10026.911000.22910047.231016.95410067.551030.03910077.711033.969 10108.21050.229
10149.02 1083.6510159.22 1089.9110169.431090.75310200.041088.48410230.651094.152
10261.261095.96810271.471092.36510281.671094.19910322.491124.51710332.691130.489
 10353.11138.27410393.691147.819 10454.41179.13410484.641199.82910500.981207.912
#Mann= 3 , 0 , 0
9759.954    0.12       09759.954    0.12       010500.98    0.12       0
#XS Ineff= 2 , 0
       0                               0
Bank Sta=9759.954,10500.98
Exp/Cntr=0.3,0.1

Type RM Length L Ch R = 1 ,32831.12,246.336800,246.336800,246.336800
XS GIS Cut Line= 6
569381.990965771799400.939269506569456.939368729799587.703651198
569530.496179856799853.366860126569575.457037342800099.389012238
 569583.75631422800203.613538417569588.230749047800373.652109682
#Sta/Elev= 30
9499.0631237.3069506.6321234.4159525.2851219.1479547.0811214.3019568.8771200.332
9633.7011186.2219644.3371191.4699665.3641193.2269697.5211184.2049728.9031163.354
9760.2321135.4729854.0451062.195  9895.31034.1739915.9281010.8689946.869985.0431
9987.965 967.70910018.54966.451310059.35979.274810110.371010.34210155.041032.695
10191.531045.21310211.751048.72510251.991035.60610282.081042.63110332.241077.889
10362.251091.84910392.261115.95110412.271127.48810492.291203.16110500.951208.599
#Mann= 3 , 0 , 0
9499.063    0.12       09499.063    0.12       010500.95    0.12       0
#XS Ineff= 2 , 0
       0                               0
Bank Sta=9499.063,10500.95
Exp/Cntr=0.3,0.1

Type RM Length L Ch R = 1 ,32584.79,478.426200,478.426200,478.426200
XS GIS Cut Line= 6
569170.724171847799502.590394074569219.294918531799659.200441892
569276.894872725799901.456699823569356.030317043800067.836248849
569386.359671771800153.210626112569444.121490755800461.427489769
#Sta/Elev= 30
9499.0831194.7779554.3931166.2539596.3771169.7539606.771 1165.799658.7361126.428
9679.303  1123.49720.318 1097.269730.572  1095.1 9751.081083.1359781.8421051.361
9792.0961044.0489822.8571042.4059853.6191021.5989895.0731010.0219933.711978.3788
9982.552964.961210025.76967.199610114.98990.851110157.571013.39210209.671054.313
10240.621064.303 10271.31068.46410300.871080.47210321.371092.36410372.831126.882
10413.371167.609 10423.51174.90710433.63 1177.96 10453.91173.78710500.951149.985
#Mann= 3 , 0 , 0
9499.083    0.12       09499.083    0.12       010500.95    0.12       0
#XS Ineff= 2 , 0
       0                               0
Bank Sta=9499.083,10500.95
Exp/Cntr=0.3,0.1

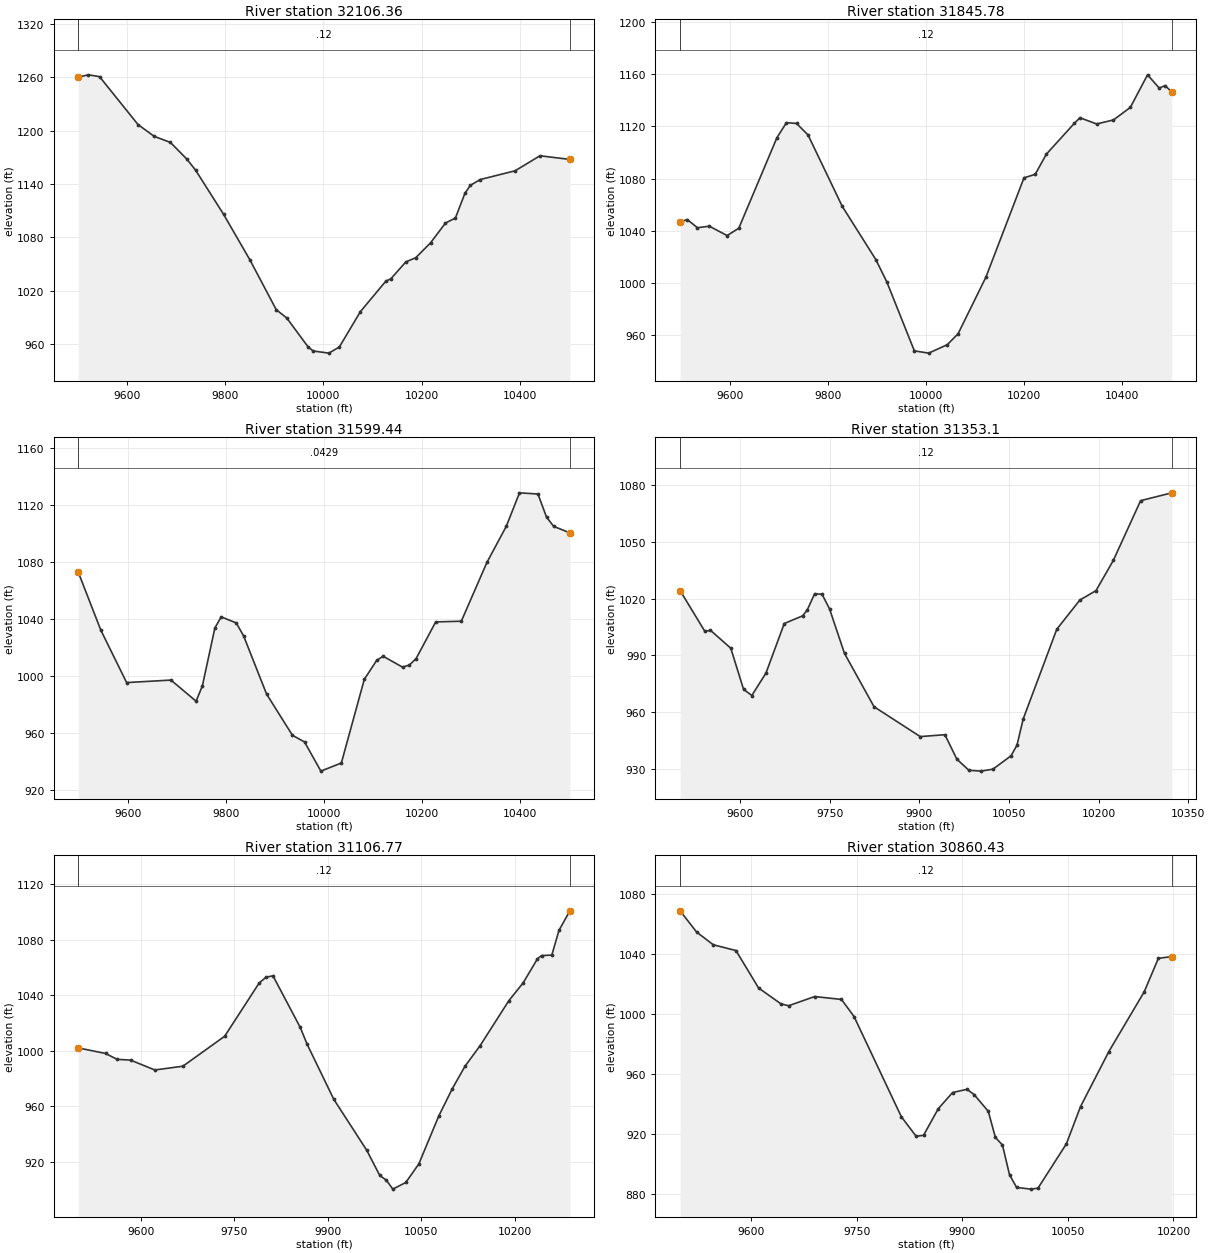
Type RM Length L Ch R = 1 ,32106.36,260.584000,260.584000,260.584000
XS GIS Cut Line= 6
568691.971549482799486.221773497568786.490010303799681.291685186
568916.412031733800013.709048266568936.412194956800093.270357745
568973.572492887800335.654582476569000.059947617800432.862000277
#Sta/Elev= 30
9500.3311260.4419521.4561262.9869543.9561260.9149622.3691207.0229655.3241193.766
9688.2781186.9639721.1641168.5669739.6881155.7269796.7651105.967 9850.391054.737
9904.009998.72969925.457989.36739968.352957.26349979.076952.275310011.21949.8594
10032.63956.792310075.42996.541110127.271030.83210137.491033.50710168.011052.499
10188.211057.19910218.511074.02810248.811096.21710269.011101.87310288.391129.629
10299.311138.58210319.521145.16710390.591154.99610441.341171.91710502.221167.801
#Mann= 3 , 0 , 0
9500.331    0.12       09500.331    0.12       010502.22    0.12       0
#XS Ineff= 2 , 0
       0                               0
Bank Sta=9500.331,10502.22
Exp/Cntr=0.3,0.1

Type RM Length L Ch R = 1 ,31845.78,246.336800,246.336800,246.336800
XS GIS Cut Line= 6
568406.832366048799625.697667638568504.423609795799773.068306933
568582.092704321799902.688816733568736.866967336800209.097663374
 568846.99291701800410.887805537568900.252765109800496.425116869
#Sta/Elev= 30
9499.0261046.7769513.5681048.6829534.4421042.4049558.6141043.5859594.8531036.414
9618.6351042.034 9696.371111.2889715.8261122.8059736.335 1122.16 9759.651113.422
9829.5371058.7039897.8661018.0449920.306 1000.959976.406948.201910005.58946.4838
10043.37952.930710065.41961.268410122.19 1004.6110199.791080.58910222.571083.232
10245.361098.68910302.321122.25910313.711126.53110347.891121.78410382.061124.855
10416.461134.44210451.491159.36210475.37 1149.2310487.321151.13910500.961146.228
#Mann= 3 , 0 , 0
9499.026    0.12       09499.026    0.12       010500.96    0.12       0
#XS Ineff= 2 , 0
       0                               0
Bank Sta=9499.026,10500.96
Exp/Cntr=0.3,0.1

Type RM Length L Ch R = 1 ,31599.44,246.336700,246.336700,246.336700
XS GIS Cut Line= 6
568161.029518171799859.779260054568411.946193992800161.400012069
568469.218434723800208.040158784568540.308509562800232.016513696
 568601.30907786800274.257656265568863.220677719800556.070028728
#Sta/Elev= 30
9499.1531072.917 9545.371031.9139597.951995.10539688.265996.8564 9739.41982.0296
9752.196992.67929777.769 1033.499790.5551041.2369821.2371037.0029836.2341027.903
9883.001987.06349935.804958.05799960.352953.40899993.671932.922210035.39938.6489
10082.15 997.38810107.461010.74210120.491013.59810160.061005.92710173.821007.412
10187.571011.88610227.551037.70110279.751038.18610331.941079.493 10371.41104.855
10398.271128.34310435.851127.50310453.321111.30310467.841104.80210500.861100.235
#Mann= 3 , 0 , 0
9499.153  0.0429       09499.153  0.0429       010500.86  0.0429       0
#XS Ineff= 2 , 0
       0                               0
Bank Sta=9499.153,10500.86
Exp/Cntr=0.3,0.1

Type RM Length L Ch R = 1 , 31353.1,246.336800,246.336800,246.336800
XS GIS Cut Line= 6
568046.330266623 799908.19424549  568272.3532018800184.863071936
568300.240426569800268.590700152568294.437064371800387.889798483
568314.240080156800433.913337313568462.030159153800575.704765789
#Sta/Elev= 30
9499.1951024.3069540.6781002.7179550.1211003.2589584.085993.80799605.466972.0783
9619.303   968.89643.054980.71249673.6381006.8579704.2231010.9039711.9611013.915
9724.4761022.6249736.9911022.2939749.5051014.5289774.535991.01549823.976962.8606
9901.315 947.073 9942.59948.07569962.645935.13499982.703929.274710002.89928.8154
10023.06929.854710053.24936.903110063.27942.533110073.71956.409810129.961003.845
10168.591019.285 10195.61024.24310224.531040.18410270.311071.81910322.531075.959
#Mann= 3 , 0 , 0
9499.195    0.12       09499.195    0.12       010322.53    0.12       0
#XS Ineff= 2 , 0
       0                               0
Bank Sta=9499.195,10322.53
Exp/Cntr=0.3,0.1

Type RM Length L Ch R = 1 ,31106.77,246.336700,246.336700,246.336700
XS GIS Cut Line= 6
567726.023132685800265.888740614 568025.61393254800417.269645429
568118.176025623800454.661847372568231.991167134 800488.66016274
568278.178733917 800507.09587937568440.133949197800597.600975741
#Sta/Elev= 30
 9499.081002.0249543.102998.01699561.709993.78369583.222993.25029622.162986.1294
9667.339988.85379734.3891010.4029789.7971048.7219800.8781052.909 9811.961053.895
9855.711 1016.839866.4971004.9539909.637965.04179962.627928.30919983.499910.2063
9993.935906.870810004.46900.3935 10025.3905.191210046.15918.498910078.21953.0163
10099.74 972.49810120.27988.768610144.681003.68210190.641035.93410213.681048.805
10236.721066.14810243.211068.46210259.761068.83310271.281086.60610288.721100.659
#Mann= 3 , 0 , 0
 9499.08    0.12       0 9499.08    0.12       010288.72    0.12       0
#XS Ineff= 2 , 0
       0                               0
Bank Sta=9499.08,10288.72
Exp/Cntr=0.3,0.1

Type RM Length L Ch R = 1 ,30860.43,246.336800,246.336800,246.336800
XS GIS Cut Line= 6
567660.901508233800546.558310824567932.205065765800650.544388861
568001.939506183800672.267475506568053.138695429800682.784264836
568163.473580164800696.718643001568333.989414659800714.801542095
#Sta/Elev= 30
9499.0651068.9449522.6521054.7579546.2921046.316 9578.421042.4899610.548 1017.56
9642.6761006.8519653.3851005.7339690.2991011.8349728.3511009.9069746.181998.5142
9813.489931.67839834.437918.71989844.911  919.379865.778937.04479886.196947.8815
9906.613950.01129916.794 946.5349936.913935.36599946.972917.98769957.031912.9165
 9967.09 893.066 9977.15884.64439997.366883.519510007.49884.153310047.81913.6611
10067.92938.479110108.14975.148710158.421014.98310178.531037.29710197.631038.457
#Mann= 3 , 0 , 0
9499.065    0.12       09499.065    0.12       010197.63    0.12       0
#XS Ineff= 2 , 0
       0                               0
Bank Sta=9499.065,10197.63
Exp/Cntr=0.3,0.1