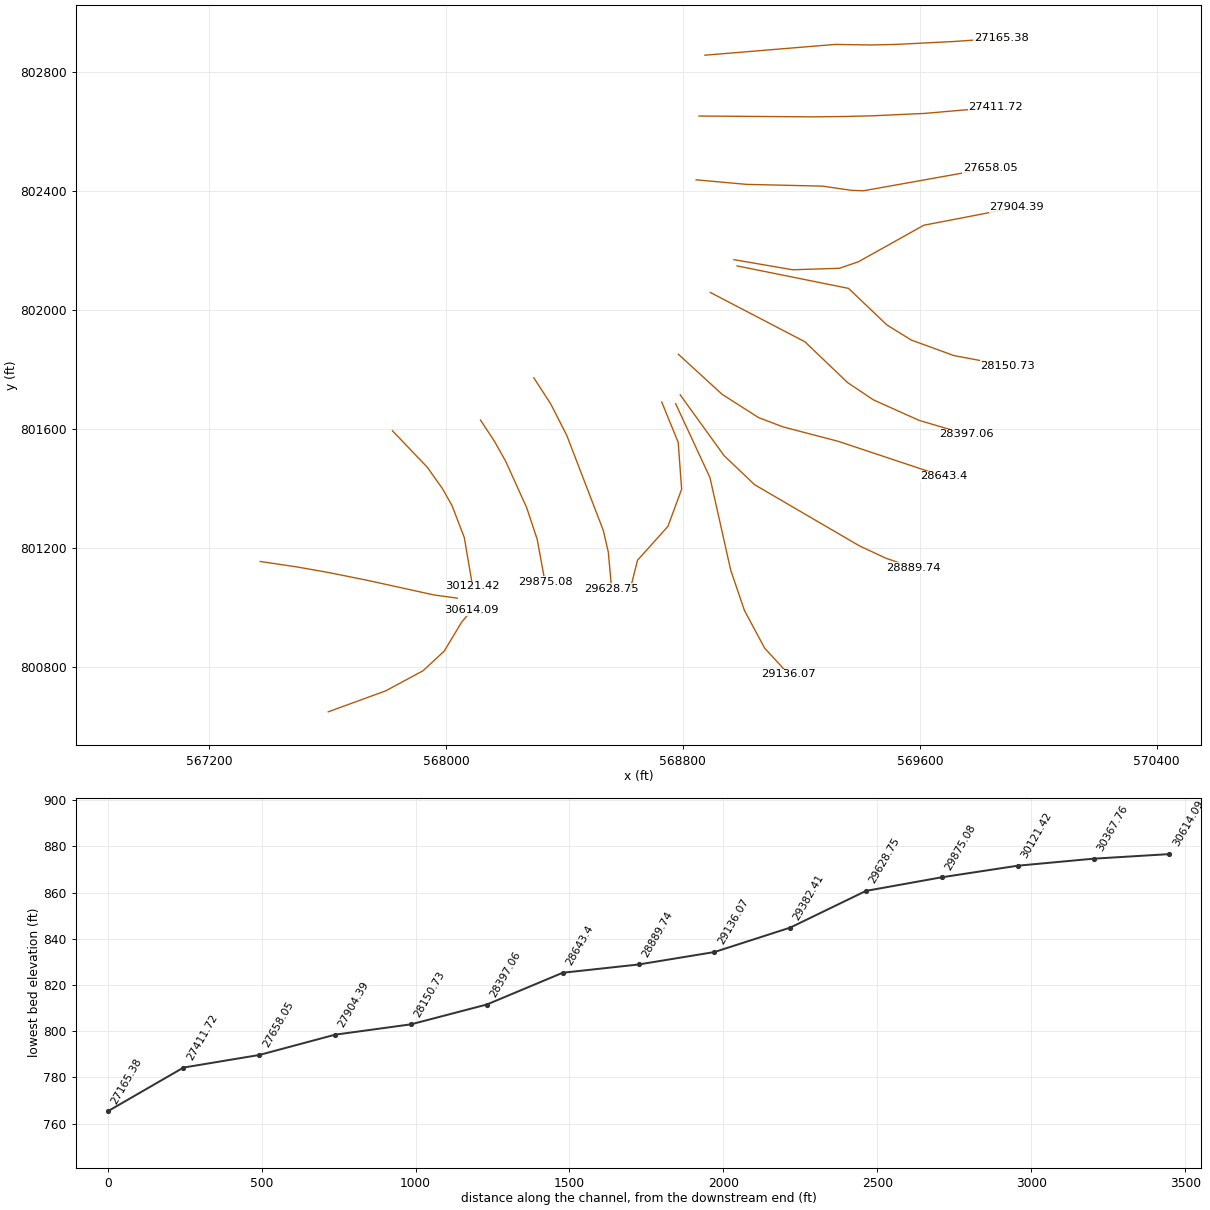
HEC-RAS study 11081_ras.prj: 11081

--- 11081_ras.g01 (geometry) --- (continued)

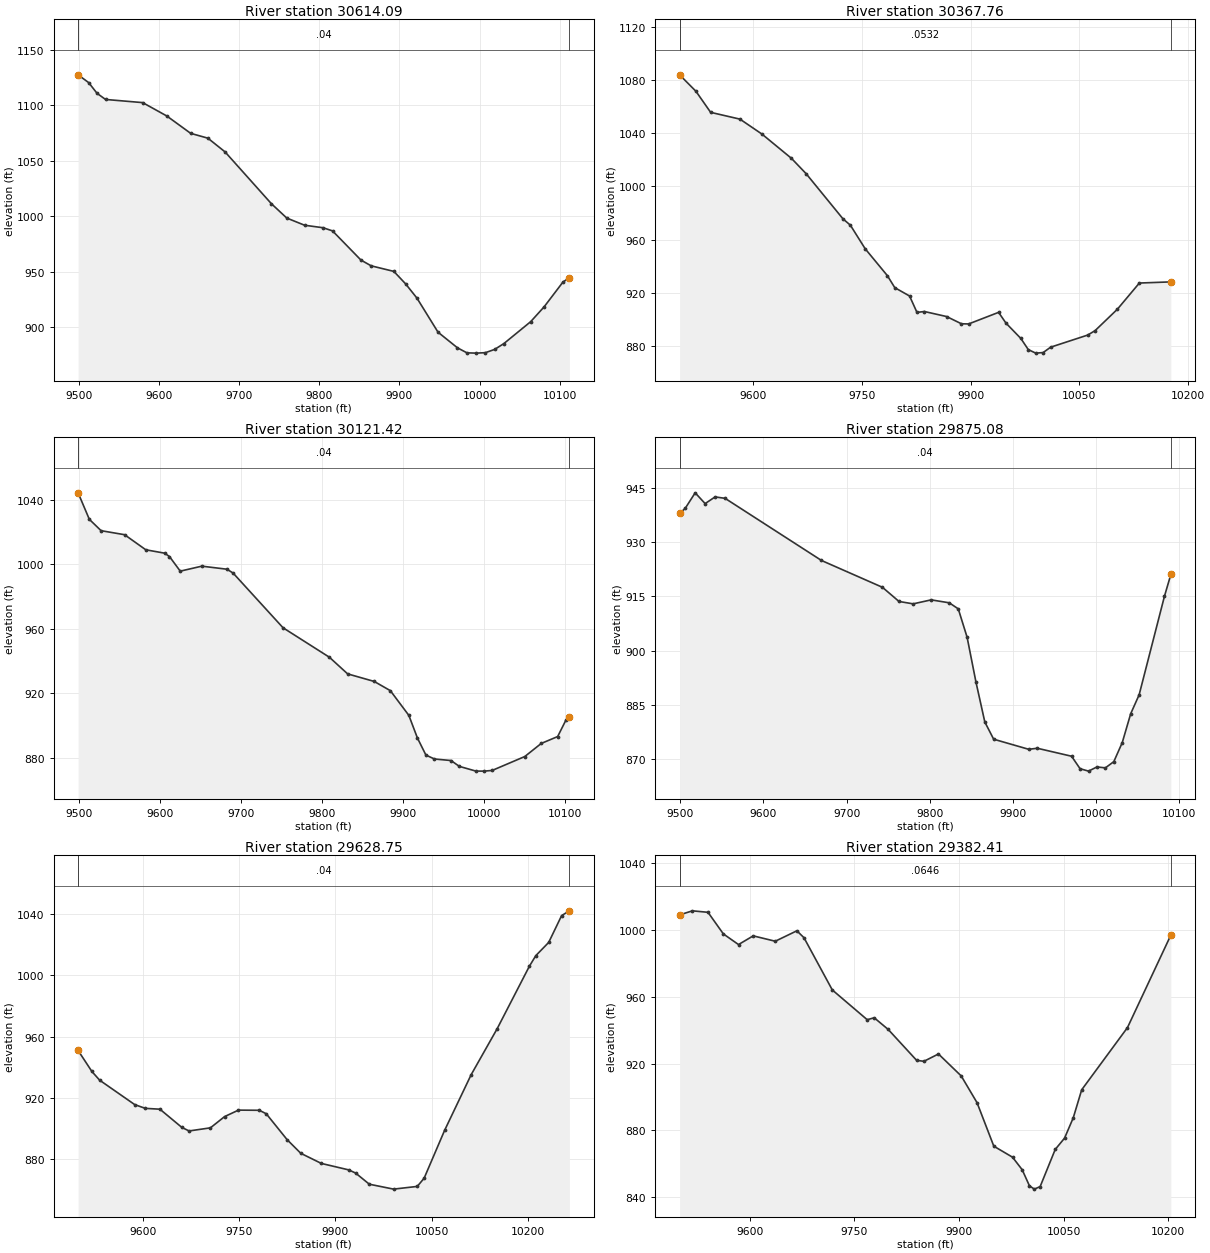
Type RM Length L Ch R = 1 ,30614.09,246.336700,246.336700,246.336700
XS GIS Cut Line= 6
 567602.53700031800649.391424954567796.566597663800719.982666282
567922.447421164 800787.53498144567994.022054913800853.616772969
568052.840731338800950.908131496 568086.07062126800990.413925594
#Sta/Elev= 30
9499.1431127.2479512.2891120.2569522.8361110.5469533.3831105.0679579.6831102.224
9609.7181090.2189639.5621074.555 9661.041070.1989682.5181057.8159740.2641011.181
9759.445998.27139781.647991.80769804.823989.53449816.543986.70079851.966960.4472
9864.705955.24879893.047950.22479907.633939.06289921.846926.18619948.182895.4524
9972.391881.40989984.218 876.8889995.768876.6249 10007.3877.040610018.83879.9896
10030.35885.258310063.82905.008410080.48918.295910104.02940.632110112.03 944.561
#Mann= 3 , 0 , 0
9499.143    0.04       09499.143    0.04       010112.03    0.04       0
#XS Ineff= 2 , 0
       0                               0
Bank Sta=9499.143,10112.03
Exp/Cntr=0.3,0.1

Type RM Length L Ch R = 1 ,30367.76,246.336800,246.336800,246.336800
XS GIS Cut Line= 6
567372.675381323801154.969949997567496.195625156801136.733353635
567603.574881817801117.848146829 567732.74657923801091.950662325
567959.304848978801042.446406961 568038.02191593801031.682993992
#Sta/Elev= 30
9499.0141083.7889521.5811071.4099541.7981055.5969582.2311050.4919612.5571039.246
 9653.121021.0549673.4271009.4839724.194975.54149734.354970.80239754.752953.0966
9785.349932.86989795.548923.85829815.946 917.5679826.145905.25789836.344905.9217
9866.949902.14469887.418 896.6999897.324896.57279938.588905.27759948.822897.1806
9969.291885.66299979.525877.30269989.759874.643610000.01875.065810010.26879.1006
10061.44888.222810071.67891.5847 10102.3907.635110132.58927.3154   10176928.1843
#Mann= 3 , 0 , 0
9499.014  0.0532       09499.014  0.0532       0   10176  0.0532       0
#XS Ineff= 2 , 0
       0                               0
Bank Sta=9499.014,10176
Exp/Cntr=0.3,0.1

Type RM Length L Ch R = 1 ,30121.42,246.336700,246.336700,246.336700
XS GIS Cut Line= 6
567819.160834035801594.555780199567936.762924603801472.012855044
567988.118606891801399.927874679568020.365055685801342.915656725
568061.911554086801235.196035232568089.842175981 801070.91190986
#Sta/Elev= 30
9499.1541044.3189513.0131027.8789527.5171020.8249556.525 1018.339582.7171008.968
9605.9111006.8779611.9311004.7869625.245995.70589651.874 998.8099682.871996.9105
9690.452994.54049752.094960.58549809.324942.29059831.868931.95569864.693927.2612
9884.601921.53939907.438906.19189917.963892.21619928.489881.57339939.008879.1254
9959.487878.18169969.726874.55989990.086871.636210000.18871.604310010.25 872.025
10050.57880.669710070.83 888.77710091.13893.063910101.37903.3298 10105.6905.0067
#Mann= 3 , 0 , 0
9499.154    0.04       09499.154    0.04       0 10105.6    0.04       0
#XS Ineff= 2 , 0
       0                               0
Bank Sta=9499.154,10105.6
Exp/Cntr=0.3,0.1

Type RM Length L Ch R = 1 ,29875.08,246.336800,246.336800,246.336800
XS GIS Cut Line= 6
568116.459156778801630.659316563568163.668860773801559.094880952
568201.471990782801492.090931434568272.378846291801336.123622467
568307.797145206801230.006183847568334.120778367801087.426117446
#Sta/Elev= 30
9499.077937.95759505.857939.37229517.837943.66799529.817940.68469541.797942.5366
9553.776942.14719669.774924.93719743.115917.50799763.038913.58849780.039912.9253
9801.765914.02989823.491 913.213 9834.33 911.5419844.978903.66879855.627891.2567
9866.275880.20959876.924875.44359919.024872.65489929.443872.93649970.627870.7303
9980.849867.27839991.019866.606110001.17867.765510011.32867.509310021.47869.2392
10031.62874.518110041.77882.499910051.92887.747110082.36915.018610090.08921.0826
#Mann= 3 , 0 , 0
9499.077    0.04       09499.077    0.04       010090.08    0.04       0
#XS Ineff= 2 , 0
       0                               0
Bank Sta=9499.077,10090.08
Exp/Cntr=0.3,0.1

Type RM Length L Ch R = 1 ,29628.75,246.336700,246.336700,246.336700
XS GIS Cut Line= 6
568296.462299514801772.808593236568353.491954488801685.067171082
  568407.7298061801579.342571994568531.374786775801258.777511123
568548.144914025801186.168107898568559.250691665801062.907374268
#Sta/Elev= 30
9499.059950.96119520.553937.29049532.623931.62459587.298915.72539603.738913.2907
9626.568912.7412  9660.7900.89319671.977 898.579 9705.24900.60369727.302907.9199
9748.957912.14129781.439912.03239792.267909.76479824.726892.92629846.081884.0231
9878.114 877.4389920.824873.22769931.501 871.1699952.856863.91029990.668860.7122
10027.55862.476110038.23867.799910070.16898.966310111.58935.232610152.07965.1385
10202.271005.81110212.311012.71210232.391021.31810252.471038.74710264.61 1041.87
#Mann= 3 , 0 , 0
9499.059    0.04       09499.059    0.04       010264.61    0.04       0
#XS Ineff= 2 , 0
       0                               0
Bank Sta=9499.059,10264.61
Exp/Cntr=0.3,0.1

Type RM Length L Ch R = 1 ,29382.41,246.336800,246.336800,246.336800
XS GIS Cut Line= 6
568728.383596003801691.513647708568784.085021198801555.676826695
568795.698945627801397.843948589568749.360783279801273.064408243
568646.641201638 801158.96010288568620.229468637801053.655421896
#Sta/Elev= 30
9499.1961009.0729517.6381011.5019539.9731010.614 9561.99997.66989583.703991.3025
9604.819996.50359636.452993.29189667.411999.54119677.629 995.3899718.236964.1098
9768.293946.29369778.333947.44969798.417 940.4569839.126921.97219849.584921.3684
9870.499925.76769903.139912.60149925.821896.59359949.866870.54789976.718863.9427
9990.547856.4496   10001846.784310008.04 844.82110016.33846.347410037.93868.5788
10051.33875.363110063.81887.529410075.92904.320810141.57941.5684 10203.8996.9962
#Mann= 3 , 0 , 0
9499.196  0.0646       09499.196  0.0646       0 10203.8  0.0646       0
#XS Ineff= 2 , 0
       0                               0
Bank Sta=9499.196,10203.8
Exp/Cntr=0.3,0.1

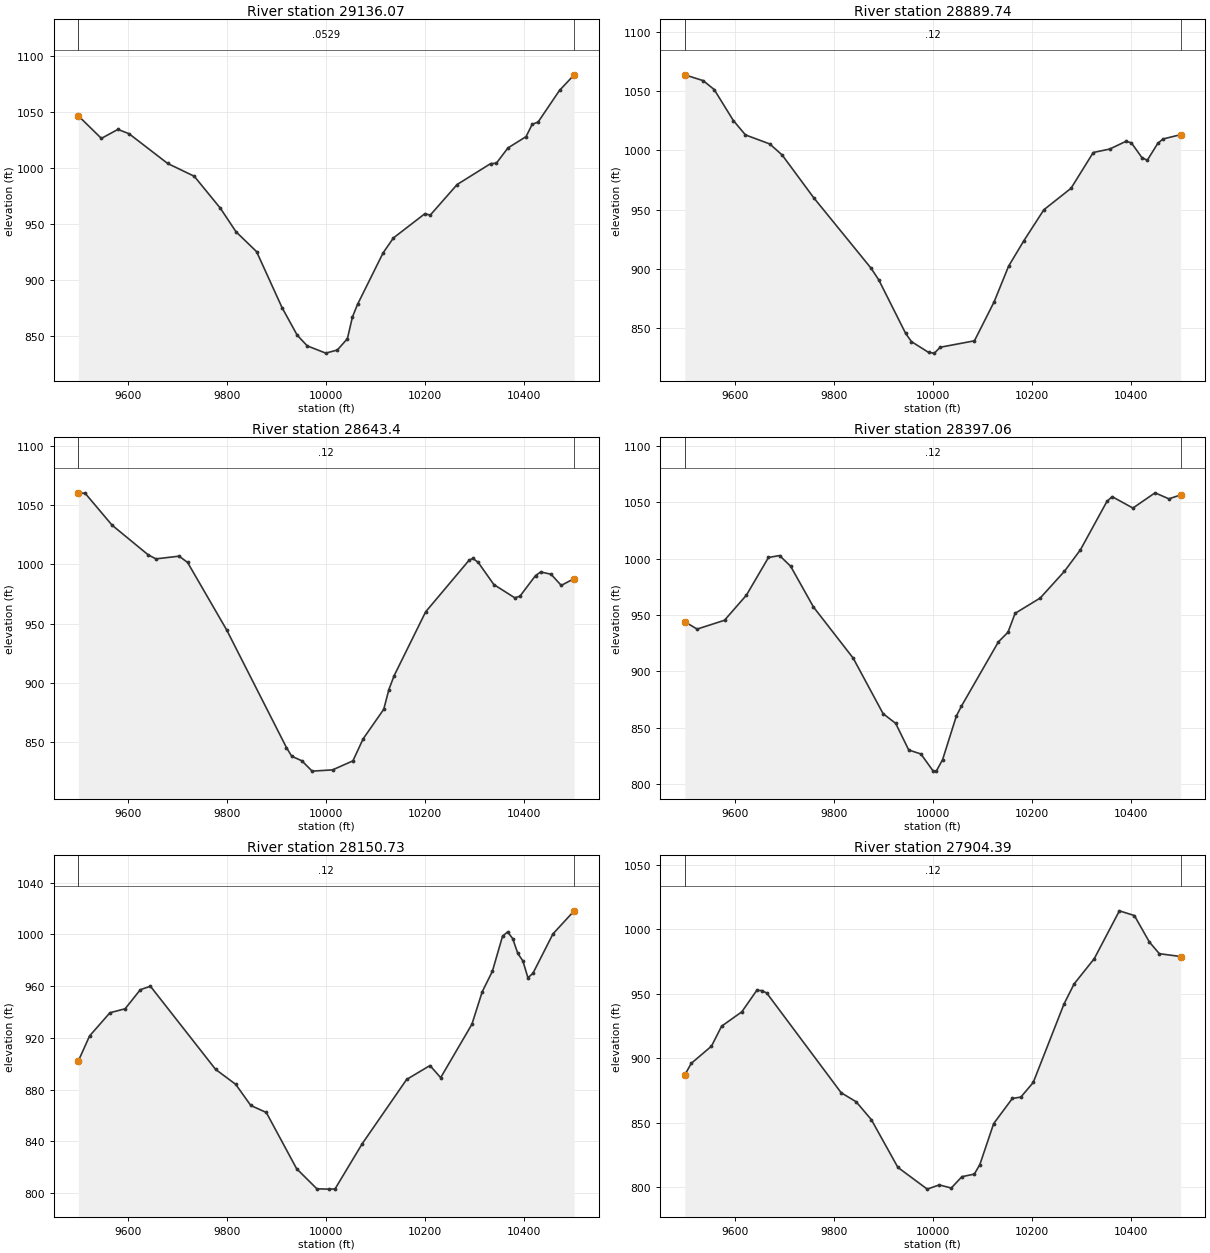
Type RM Length L Ch R = 1 ,29136.07,246.336700,246.336700,246.336700
XS GIS Cut Line= 6
568775.606088144801685.489760745 568891.40450219801437.063405039
568961.294349445801126.277061168569007.931054558800989.974175656
569076.079337988800863.405500895569157.366787132800775.504907637
#Sta/Elev= 30
9499.0541046.5249545.6271026.3329579.0571034.3829601.5391030.4979679.5661003.908
9733.282992.46759786.298963.72069817.634942.81239859.222925.04899910.664874.9865
9941.244850.33339961.575840.7521    9999834.249910022.29837.026610042.66  847.09
10052.92866.586810063.18877.830810114.87923.943810135.76937.303610199.32958.9793
10210.02957.6592 10264.5 985.08910331.971003.72610343.69 1004.1210367.131017.805
10403.711027.913 10416.21039.01110427.91 1040.8810471.321069.277 10500.91083.196
#Mann= 3 , 0 , 0
9499.054  0.0529       09499.054  0.0529       0 10500.9  0.0529       0
#XS Ineff= 2 , 0
       0                               0
Bank Sta=9499.054,10500.9
Exp/Cntr=0.3,0.1

Type RM Length L Ch R = 1 ,28889.74,246.336800,246.336800,246.336800
XS GIS Cut Line= 6
568790.867000314801715.286148977568938.822102888801511.207786559
569042.127322401801413.217296678 569395.74733416801207.708484231
  569486.3783642801165.562990543569579.135205057801134.267868766
#Sta/Elev= 30
9499.0751063.5869536.0941058.7059558.4351051.2079597.2081025.0239621.6541012.902
9670.5811005.3229695.857995.94669759.519959.95459875.402900.51499891.098890.5968
9945.368845.47869957.021 838.5989991.977829.406510003.35828.867910015.22833.8199
10084.36839.2617 10123.9871.938910153.48902.305910184.32923.7453 10224.6949.7801
10279.47 967.87210324.44998.070210357.771001.01110390.621007.52110401.521006.233
10422.96993.649210433.67991.576410454.811005.78410465.27 1009.4510500.971013.139
#Mann= 3 , 0 , 0
9499.075    0.12       09499.075    0.12       010500.97    0.12       0
#XS Ineff= 2 , 0
       0                               0
Bank Sta=9499.075,10500.97
Exp/Cntr=0.3,0.1

Type RM Length L Ch R = 1 , 28643.4,246.336700,246.336700,246.336700
XS GIS Cut Line= 6
568784.829364684801851.838779671568932.625577775801717.062439844
569055.564033026 801638.89694512 569138.37766496801607.575471144
569325.435796857801558.872287667569680.155680662 801441.14236601
#Sta/Elev= 30
9499.0821060.5939513.0591060.1169567.3681033.216 9640.51 1008.07 9655.971004.747
9702.6951007.0499719.8221001.7479799.116944.43629919.655845.18689930.183837.9264
9950.898833.97559971.544825.290610012.78826.342410053.91833.978710074.57852.5987
10116.21877.577510126.61894.286210137.21906.002710200.84 959.95110288.931003.754
10296.281005.10610306.881001.903 10338.7983.039910380.97971.831810391.46973.1826
10422.93990.658210433.42993.6793 10454.2991.766610474.92982.308710500.97988.1032
#Mann= 3 , 0 , 0
9499.082    0.12       09499.082    0.12       010500.97    0.12       0
#XS Ineff= 2 , 0
       0                               0
Bank Sta=9499.082,10500.97
Exp/Cntr=0.3,0.1

Type RM Length L Ch R = 1 ,28397.06,246.336800,246.336800,246.336800
XS GIS Cut Line= 6
568892.542563147802059.841504106569211.819901533801893.994678819
 569356.65867444801756.251331087569443.664514956801698.350570997
569597.009611656801629.840904483 569757.91560487801582.361788373
#Sta/Elev= 30
9499.065944.00359523.927937.49999579.282945.31969623.566967.59229668.1481001.008
9690.4991002.7089712.849993.26129759.064957.06699839.379 911.6739899.771 862.479
9925.128853.90339951.519830.31179976.128826.7639   10001811.556710007.32811.6411
10020.01821.844410047.79860.462410057.96869.157510132.73926.208210152.07934.7103
10166.42951.471510217.24965.060210265.96988.674910298.391007.78910351.911050.672
10362.431054.945 10404.51044.81310449.161058.31910477.22 1052.9810500.851056.491
#Mann= 3 , 0 , 0
9499.065    0.12       09499.065    0.12       010500.85    0.12       0
#XS Ineff= 2 , 0
       0                               0
Bank Sta=9499.065,10500.85
Exp/Cntr=0.3,0.1

Type RM Length L Ch R = 1 ,28150.73,246.336700,246.336700,246.336700
XS GIS Cut Line= 6
568982.969942522802149.090782397569359.419751344802073.475979615
569488.465440456801950.798208712569571.579025443801899.519329105
569715.006665871801847.585514708569897.352961354801813.351400395
#Sta/Elev= 30
9499.174902.12029521.849921.4869 9563.02939.4555 9593.75 942.5359624.363957.2677
9644.763959.99259776.453895.64089816.973 884.1029847.613867.6972 9878.87862.3024
9940.172818.77719981.128 803.21110005.42802.984410017.76803.139310072.62838.0976
10162.42887.861610209.57898.614910231.15 889.23110294.27930.570110315.13955.7534
10335.64971.567810356.16998.714410366.411001.96210376.67996.828710386.93 985.362
10397.18979.599910407.44966.525310417.55969.993910457.991000.46410500.811018.314
#Mann= 3 , 0 , 0
9499.174    0.12       09499.174    0.12       010500.81    0.12       0
#XS Ineff= 2 , 0
       0                               0
Bank Sta=9499.174,10500.81
Exp/Cntr=0.3,0.1

Type RM Length L Ch R = 1 ,27904.39,246.336800,246.336800,246.336800
XS GIS Cut Line= 6
568972.235352736802170.121850564569170.623413624802136.099799198
569328.667752973802141.136952294569392.895573193802163.154426174
569613.368741646802285.865980614569927.545441759802346.141169842
#Sta/Elev= 30
9499.137886.99839512.178895.94269553.042909.28069573.474924.74889614.267  935.85
9644.509952.47639654.589952.3791 9664.67950.45989815.092873.17829845.323 866.214
9876.065 852.3149929.657815.35599988.972798.508810013.31801.768910037.52799.3641
10058.99808.139510084.11810.155510095.29817.552310123.23849.321210160.88868.7458
10178.12869.8388 10203.1881.128910265.14941.830510285.66957.484410326.43977.0726
10377.191014.13410407.521010.466 10437.8989.961410457.98980.922610500.92978.7351
#Mann= 3 , 0 , 0
9499.137    0.12       09499.137    0.12       010500.92    0.12       0
#XS Ineff= 2 , 0
       0                               0
Bank Sta=9499.137,10500.92
Exp/Cntr=0.3,0.1

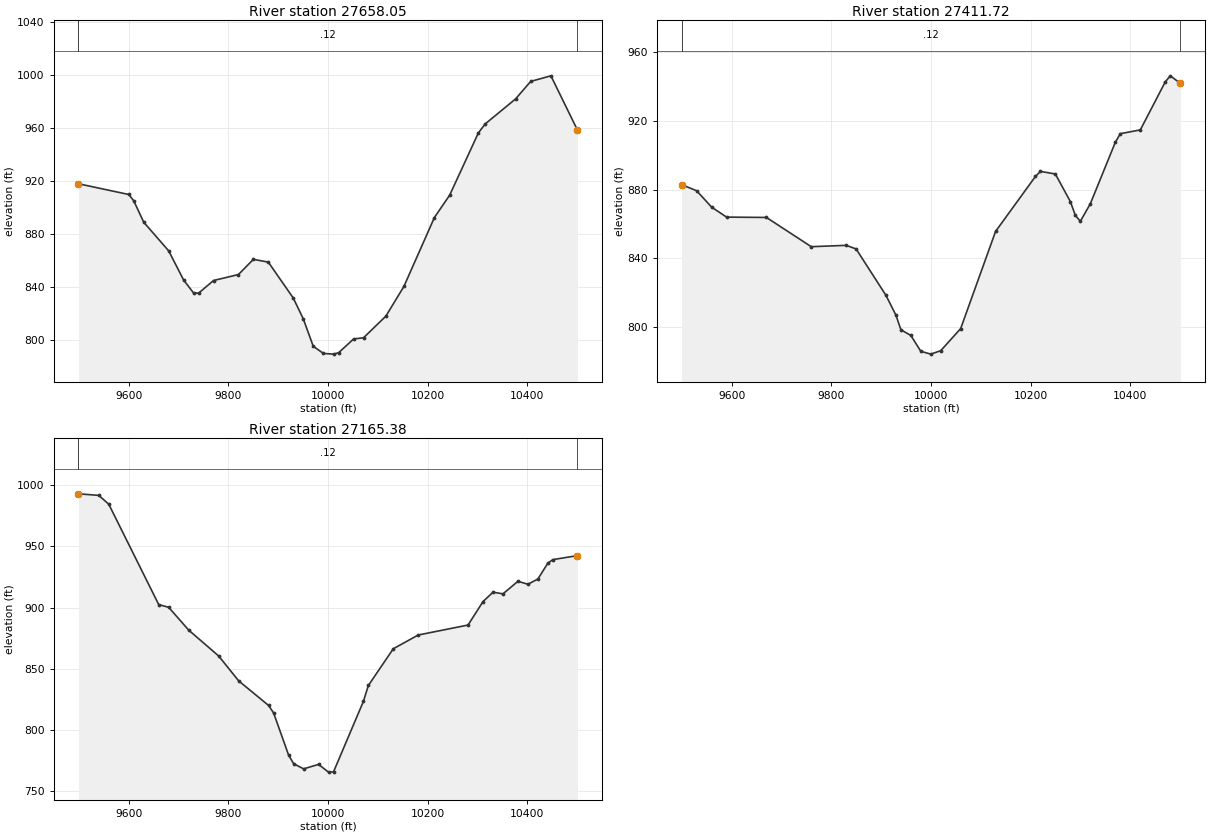
Type RM Length L Ch R = 1 ,27658.05,246.336700,246.336700,246.336700
XS GIS Cut Line= 6
568844.610866715802438.614229748569015.139792974802423.319690251
569272.241284636802417.406838148 569369.80879098802403.120791637
569409.845978914802401.817256161569837.604910136 802477.99764683
#Sta/Elev= 30
9499.061917.97219600.005909.90259610.031905.15649630.076889.01669680.167867.4706
9710.175845.51819730.181835.73489740.183835.62349770.191845.14649820.204849.6326
9850.212 861.086 9880.22858.98829930.248831.97269950.357816.34299970.465795.6431
9990.795790.261910011.13789.727310021.27790.755210051.36801.1158 10071.4802.0511
10116.13 818.27210152.45 840.671 10213.7892.575810244.32909.379510301.98956.2688
10315.78963.055810376.72981.8676 10407.1995.047310447.61999.236310500.89958.4062
#Mann= 3 , 0 , 0
9499.061    0.12       09499.061    0.12       010500.89    0.12       0
#XS Ineff= 2 , 0
       0                               0
Bank Sta=9499.061,10500.89
Exp/Cntr=0.3,0.1

Type RM Length L Ch R = 1 ,27411.72,246.336800,246.336800,246.336800
XS GIS Cut Line= 6
568854.449054789802653.230456217569238.807162841802650.415536045
569354.423754892802651.810294666569443.266600266802654.083442854
569617.801830769 802662.08266626569855.284141928802682.841580985
#Sta/Elev= 30
9499.007882.86419529.558879.23959559.559869.7176 9589.56863.94729669.562863.7496
9759.565846.74539829.566847.53029849.567845.4544 9909.57818.44819929.571806.9513
9939.572798.45799959.573795.12769979.575785.90559999.576784.275810019.58786.2926
 10059.6799.132210129.65855.607510209.73887.582510219.74890.541510249.78889.0201
10279.85872.982610289.89864.952510299.93861.514210320.01871.7366 10370.2907.4816
10380.24912.464410420.39914.663110470.58942.668710480.62946.105510500.98941.6942
#Mann= 3 , 0 , 0
9499.007    0.12       09499.007    0.12       010500.98    0.12       0
#XS Ineff= 2 , 0
       0                               0
Bank Sta=9499.007,10500.98
Exp/Cntr=0.3,0.1

Type RM Length L Ch R = 1 ,27165.38,246.336700,246.336700,246.336700
XS GIS Cut Line= 6
568874.408883526802857.802811228569313.571163903802894.008736961
569437.753758865802892.222310918569520.724199766802894.098856864
569709.373572089802903.573287884569874.203381708802914.753402163
#Sta/Elev= 30
9499.013993.10149539.728991.84649559.789984.62049660.093902.47799680.153900.2122
9720.275881.57919780.472860.4103 9820.63840.04979880.868819.88159890.908813.6992
9921.027779.17819931.067 772.2299951.104768.01119981.113771.652410001.12765.3331
10011.12765.511210071.15823.201310081.15 836.25610131.16866.301810181.21877.5453
10281.33885.717710311.37904.9074 10331.4 912.59610351.44911.239510381.51921.5169
10401.55919.0836 10421.6923.377910441.65936.406910451.67939.261510500.99942.5197
#Mann= 3 , 0 , 0
9499.013    0.12       09499.013    0.12       010500.99    0.12       0
#XS Ineff= 2 , 0
       0                               0
Bank Sta=9499.013,10500.99
Exp/Cntr=0.3,0.1