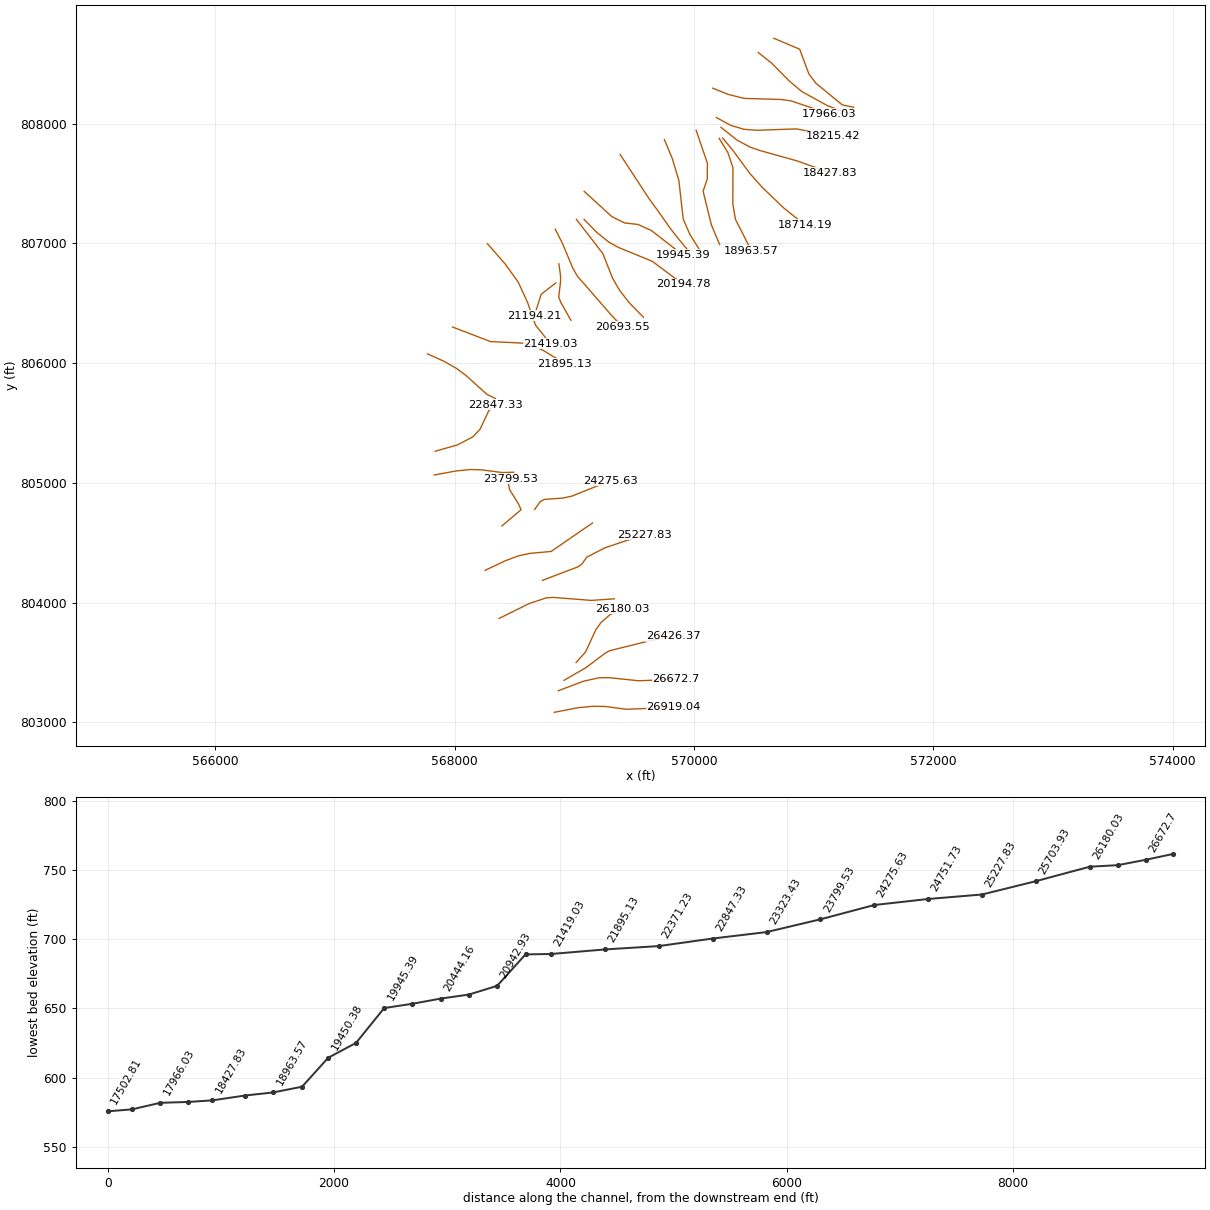
HEC-RAS study 11081_ras.prj: 11081

--- 11081_ras.g01 (geometry) --- (continued)

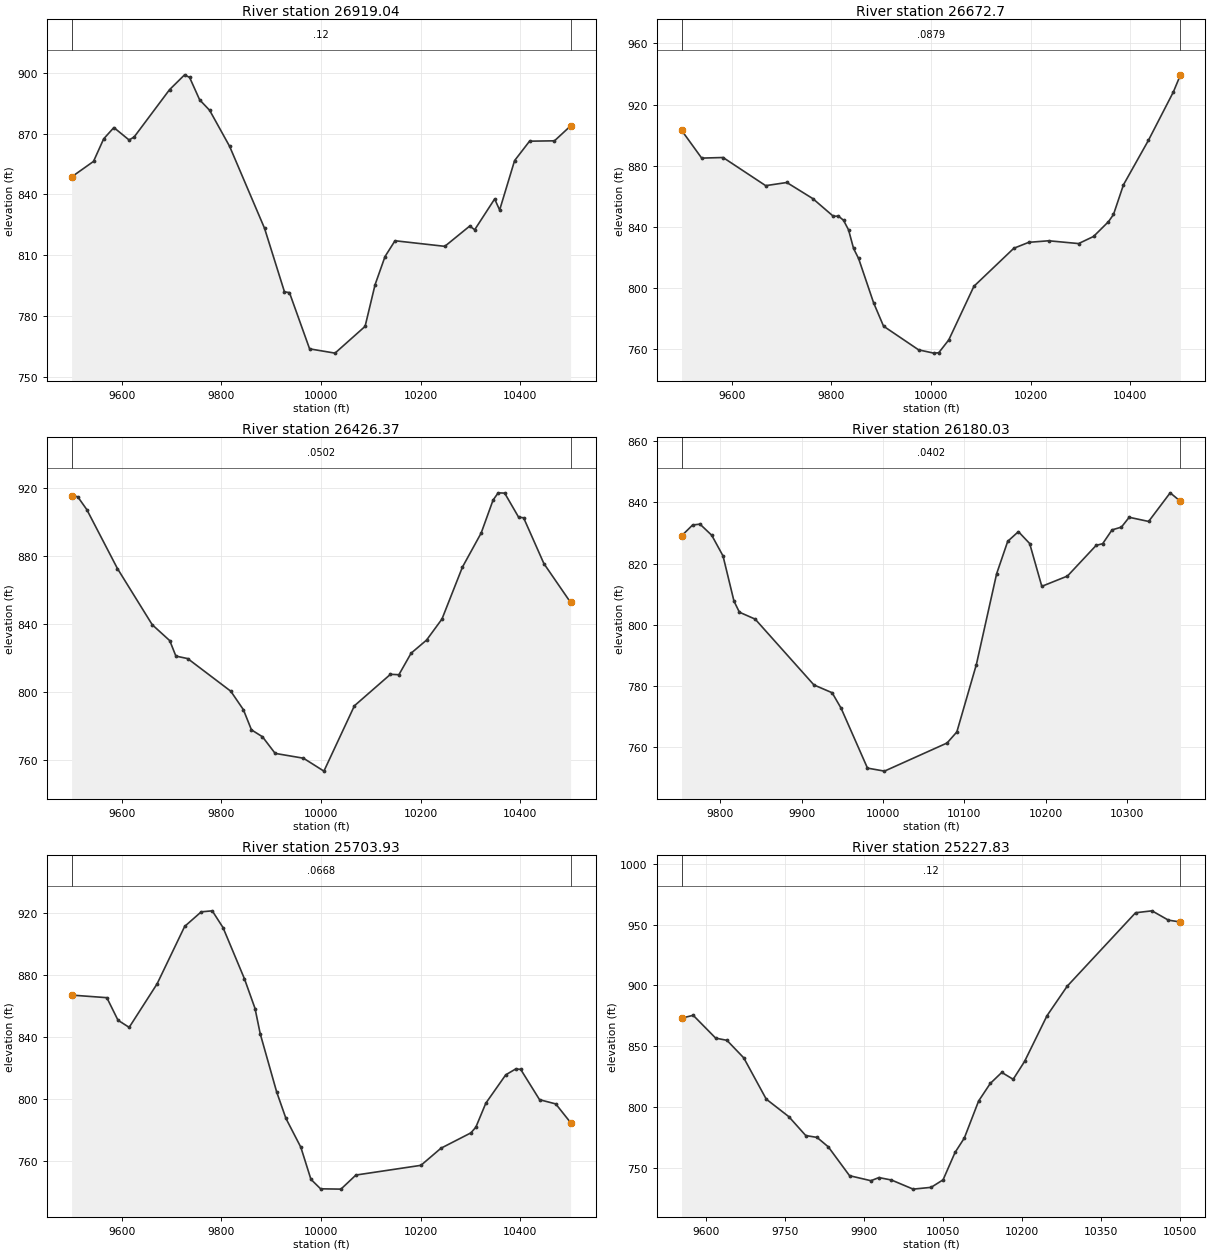
Type RM Length L Ch R = 1 ,26919.04,246.336800,246.336800,246.336800
XS GIS Cut Line= 6
568832.002670242803083.127699209569028.400950552803121.153018379
 569158.35276825803133.736693379569262.278535739803131.733397136
569432.329716474803108.676760078569827.253628811803123.979391644
#Sta/Elev= 30
 9499.06848.55539543.024856.22249563.474867.37879583.924872.9421 9614.49866.8012
 9624.64868.2891 9695.69891.6525 9725.93898.98339736.001897.68839756.144886.6452
9776.274881.43679816.363 863.6419886.401  823.239926.458791.81619936.493791.4274
9976.935763.655210027.98761.544410088.37 774.76110108.38795.314610128.39809.2432
 10148.4817.043310248.44814.282310298.46824.300110308.47822.490210348.52837.6836
10358.53832.224310388.56856.6222 10418.6866.216410468.66866.394710500.95873.7337
#Mann= 3 , 0 , 0
 9499.06    0.12       0 9499.06    0.12       010500.95    0.12       0
#XS Ineff= 2 , 0
       0                               0
Bank Sta=9499.06,10500.95
Exp/Cntr=0.3,0.1

Type RM Length L Ch R = 1 , 26672.7,246.336700,246.336700,246.336700
XS GIS Cut Line= 6
568867.318422142803263.676495868569080.013625426803343.868805013
569209.451728242803372.122246103569289.920494681803372.664726941
569536.586893046803346.738457268569849.234332158 803358.73979365
#Sta/Elev= 30
9499.092903.18049539.586884.92379582.571885.31389668.113866.88899710.521868.9545
9762.711858.41319804.003846.82289814.184846.96939824.365844.23779834.498837.9322
9844.578825.75039854.658819.20639884.721790.26929904.742774.91419975.112 759.412
10005.42757.256610015.53757.499710035.76765.931910086.21801.008710166.37825.9091
10196.39829.790910236.39 830.808 10296.4828.975310326.41833.620410356.45 843.324
10366.47848.012610386.51867.4585 10436.6896.5519 10486.7928.236210500.96939.4402
#Mann= 3 , 0 , 0
9499.092  0.0879       09499.092  0.0879       010500.96  0.0879       0
#XS Ineff= 2 , 0
       0                               0
Bank Sta=9499.092,10500.96
Exp/Cntr=0.3,0.1

Type RM Length L Ch R = 1 ,26426.37,246.336700,246.336700,246.336700
XS GIS Cut Line= 6
568914.200779346803350.440102849569097.004554767803455.906195003
  569258.4283214 803577.16279204569295.261386715803597.739833769
569630.914519641 803680.52279071 569827.59467961803720.155943613
#Sta/Elev= 30
9499.104 915.4199511.395914.74619529.596 907.2099591.065872.55139661.031 839.472
9696.158830.12989708.472821.05299732.209819.57079818.708800.38619844.043789.5097
9860.204777.65959882.357 773.5869907.817763.81219964.621760.980210005.72753.3823
10066.97791.822310139.37810.334810156.26810.081310180.78822.743910211.84830.4663
10242.74842.825610283.93873.433810321.46893.419610345.42912.838510355.66917.0666
10368.68 916.89210396.54902.791410406.72  902.3710447.43875.445810500.97852.6234
#Mann= 3 , 0 , 0
9499.104  0.0502       09499.104  0.0502       010500.97  0.0502       0
#XS Ineff= 2 , 0
       0                               0
Bank Sta=9499.104,10500.97
Exp/Cntr=0.3,0.1

Type RM Length L Ch R = 1 ,26180.03,476.099700,476.099700,476.099700
XS GIS Cut Line= 6
569015.158394331 803499.26577764569095.055901081803588.492326815
 569178.19220176803769.885964455569224.879219212803835.392533614
569302.552144316803901.815714862569401.349943692803949.675031995
#Sta/Elev= 30
9752.471829.06359766.114832.6331 9775.19832.90919789.629829.27149803.476 822.536
9816.943807.79239823.589804.16859842.987801.90829915.234780.4204  9937.6777.8715
9948.666772.80319981.041753.273610001.94752.285310078.88761.468210090.89765.0749
 10114.9787.0897 10139.8816.716610153.45827.312610166.57830.457810180.41826.5794
10195.34 812.60910226.86815.965110262.16825.984710270.13826.523110281.66831.0336
10293.19831.942310302.73 835.14810326.64833.786910353.13843.131310365.77840.3502
#Mann= 3 , 0 , 0
9752.471  0.0402       09752.471  0.0402       010365.77  0.0402       0
#XS Ineff= 2 , 0
       0                               0
Bank Sta=9752.471,10365.77
Exp/Cntr=0.3,0.1

Type RM Length L Ch R = 1 ,25703.93,476.099700,476.099700,476.099700
XS GIS Cut Line= 6
568371.930283052803866.994471878 568625.11333493803992.338620181
568768.052481134804039.337745971568820.537072016804042.909262026
569143.513112265804017.743484629569334.500397404804031.182902382
#Sta/Elev= 30
9499.067866.98139569.794865.31479592.223850.76879614.651846.17369670.722874.2462
9726.128911.29689759.337920.66569781.476921.32249803.145910.47369846.141877.4586
9867.378858.33189877.779842.03499910.763804.55079929.322787.51339959.353768.8412
9979.579748.1813    9999742.056310039.87741.852510069.89750.928910200.46 757.194
10240.65768.220710300.72778.116710310.73781.779510330.74797.261210370.75815.5588
10390.75819.338410400.78819.084510438.68799.523110471.18796.805310500.92784.7875
#Mann= 3 , 0 , 0
9499.067  0.0668       09499.067  0.0668       010500.92  0.0668       0
#XS Ineff= 2 , 0
       0                               0
Bank Sta=9499.067,10500.92
Exp/Cntr=0.3,0.1

Type RM Length L Ch R = 1 ,25227.83,476.099700,476.099700,476.099700
XS GIS Cut Line= 6
568734.205250895804185.149657093569032.663293083804298.807213623
569064.760368246804323.089759811569103.697045104804378.315125941
569255.253652325804456.707429239569586.991839667804567.874052111
#Sta/Elev= 30
9552.644873.0513 9574.85875.43779617.564856.62619638.921854.82319670.957840.3531
9713.671806.3755 9756.54791.94999788.717776.38189810.168 774.838 9831.62767.0613
9872.016743.28789912.636739.15469927.833741.74369951.711739.72219992.864732.2236
10027.02733.690110049.76739.881510072.49 762.40710090.14 774.30610117.28804.7895
10139.45819.282610161.36828.371910183.01 822.70610204.65837.4157 10247.3875.0912
10285.62899.370410415.62959.923110446.85961.503610478.07 953.81910500.96952.2961
#Mann= 3 , 0 , 0
9552.644    0.12       09552.644    0.12       010500.96    0.12       0
#XS Ineff= 2 , 0
       0                               0
Bank Sta=9552.644,10500.96
Exp/Cntr=0.3,0.1

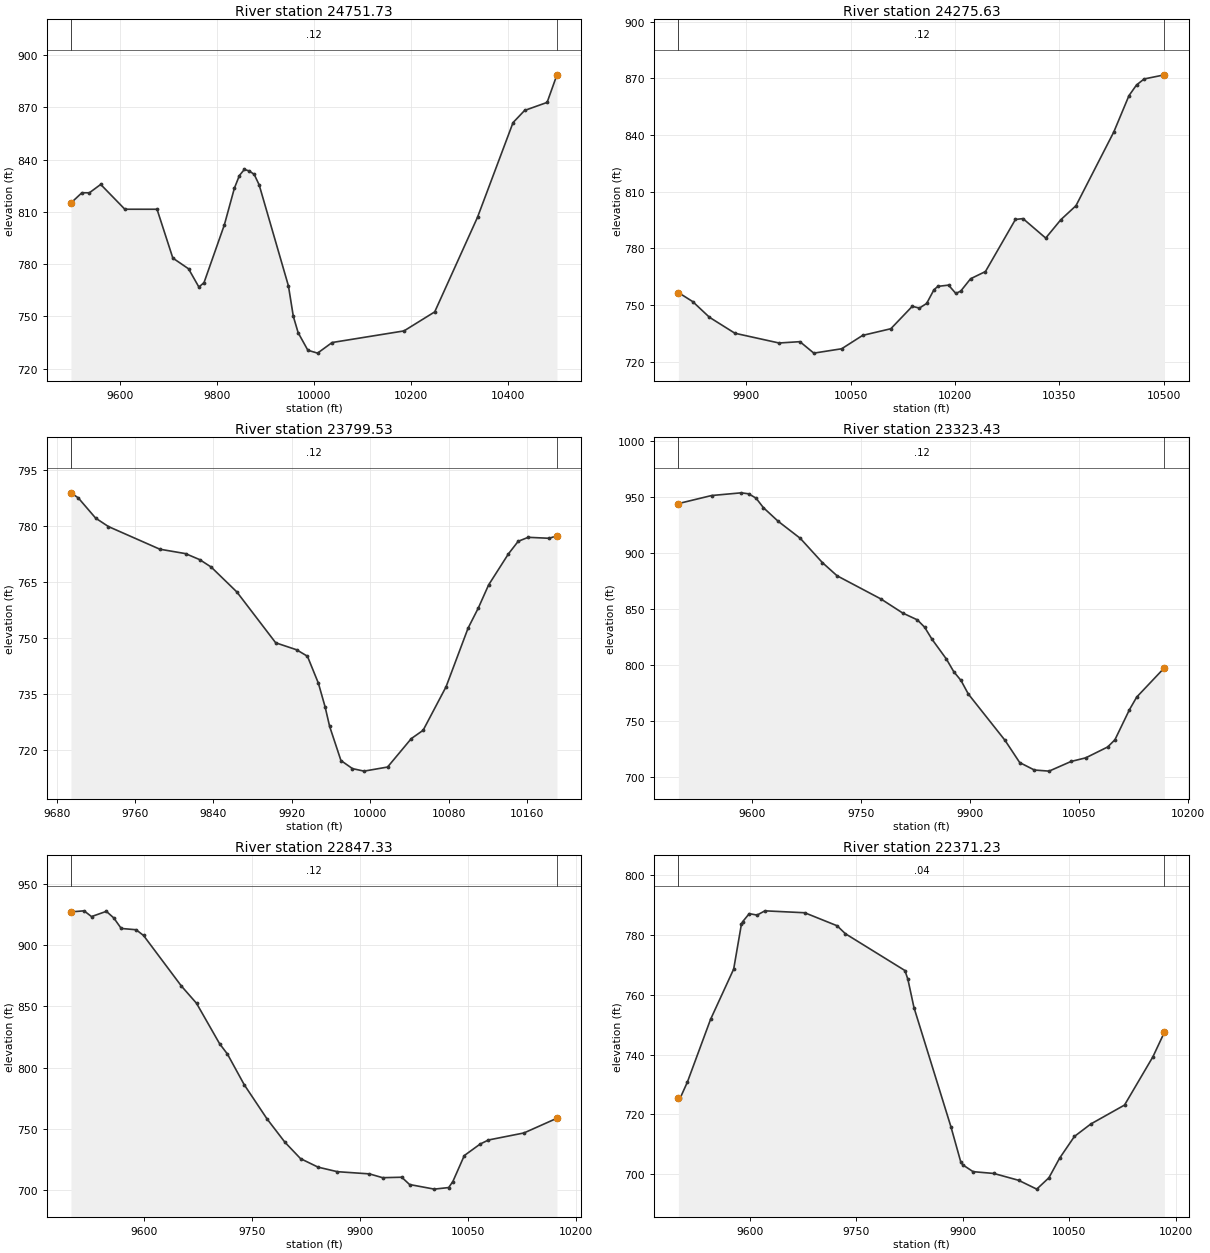
Type RM Length L Ch R = 1 ,24751.73,476.099600,476.099600,476.099600
XS GIS Cut Line= 6
  568254.5971667 804268.81584961568423.567219475804348.653141894
 568535.41034835 804390.32990689568627.919363587804410.370058455
 568806.23371104804426.386316453569152.559909473804664.423980772
#Sta/Elev= 30
9499.075815.11989521.641 820.9829536.959820.93929560.367 825.7469610.122811.5194
9676.482811.5054 9709.08783.50439741.445777.36119762.761766.89519773.305769.3931
9815.281802.5692 9835.95823.60569846.284830.86629856.481834.32669866.643833.4671
9876.804 831.5039886.966825.53139947.371767.53459957.392750.13649967.394740.6883
9987.398730.6441 10007.4728.989610037.41 735.07510185.56741.731910248.88752.6447
10337.11806.915610410.35861.208110434.17868.175610480.58872.789110500.87888.6084
#Mann= 3 , 0 , 0
9499.075    0.12       09499.075    0.12       010500.87    0.12       0
#XS Ineff= 2 , 0
       0                               0
Bank Sta=9499.075,10500.87
Exp/Cntr=0.3,0.1

Type RM Length L Ch R = 1 ,24275.63,476.099700,476.099700,476.099700
XS GIS Cut Line= 6
568668.777876419804777.848292779568716.730340837804843.192881845
568748.630094349804860.681508225568905.100798394 804872.44094801
568982.039018739804889.145069178569301.810521446805017.854986844
#Sta/Elev= 30
9802.223756.68159822.818751.89289846.833743.61199883.482735.15329946.891 729.999
9976.907730.70439996.918724.637810036.95726.9468 10067.1734.026310107.63 737.543
10138.46 749.40410148.76748.476810159.13750.929410169.62758.173110175.28 759.965
10190.62760.622310201.11756.199210208.18 757.49210222.29763.997210243.66767.8068
10286.77795.372210297.65795.8169 10330.3785.518710352.06795.239410373.83802.6506
10428.24841.692910450.01860.884110460.89866.534810471.77869.694510500.95871.8931
#Mann= 3 , 0 , 0
9802.223    0.12       09802.223    0.12       010500.95    0.12       0
#XS Ineff= 2 , 0
       0                               0
Bank Sta=9802.223,10500.95
Exp/Cntr=0.3,0.1

Type RM Length L Ch R = 1 ,23799.53,476.099700,476.099700,476.099700
XS GIS Cut Line= 6
568395.787774771804640.211039051568555.256094515804775.039797887
568532.914455742804825.207973003568459.567821115804942.015856385
568450.635708004804985.107363909568464.394021899805032.224104777
#Sta/Elev= 30
9694.646 788.9759702.063787.62539719.805782.1925  9732.9779.91939785.281773.8507
9811.471772.6666 9825.97771.04999837.662  769.069863.852762.37969903.473748.7371
9924.754746.86919935.834745.1349 9947.04 737.8789953.858731.54479958.479726.3118
9970.017717.15029981.799714.97669993.582714.308310017.58715.405310041.75723.0299
10053.83725.264410077.26736.952310099.68 752.66610110.23758.126910120.62 764.261
10140.75772.560210150.81775.971810161.05777.039710182.42776.780110190.34777.4492
#Mann= 3 , 0 , 0
9694.646    0.12       09694.646    0.12       010190.34    0.12       0
#XS Ineff= 2 , 0
       0                               0
Bank Sta=9694.646,10190.34
Exp/Cntr=0.3,0.1

Type RM Length L Ch R = 1 ,23323.43,476.099600,476.099600,476.099600
XS GIS Cut Line= 6
567830.290461659805065.052624539568008.453003883805098.075378001
568134.639837861805110.787964299568224.218821019805108.277638659
568398.663780272805085.196052089 568493.00999704805088.127705708
#Sta/Elev= 30
9499.054943.93159544.608 951.1089585.364953.52399595.553952.64559605.742948.7909
9615.896940.29139636.185928.12239666.617912.88639696.954891.26229717.126879.5003
9777.426858.79519807.504846.18139827.504840.13269837.505833.59479847.506822.9792
9867.538805.06279877.554793.88569887.569786.00239897.591773.93359948.066732.5614
9968.255712.73429988.445 706.07510008.62705.098210038.85713.7228   10059716.9506
10089.11726.639110099.12733.061610119.13759.977510129.13771.242910167.16797.3481
#Mann= 3 , 0 , 0
9499.054    0.12       09499.054    0.12       010167.16    0.12       0
#XS Ineff= 2 , 0
       0                               0
Bank Sta=9499.054,10167.16
Exp/Cntr=0.3,0.1

Type RM Length L Ch R = 1 ,22847.33,476.099700,476.099700,476.099700
XS GIS Cut Line= 6
567837.346813368805263.172610848568022.992041706805316.168230002
568152.008279782805383.244584722 568212.94481098805447.555928766
568284.881439738805600.545673893568342.611289311805650.370583047
#Sta/Elev= 30
9499.191 927.3499517.393928.23259527.704  923.529548.326927.81669558.637 922.387
9568.948 913.802 9589.57912.75019599.881908.07669652.379866.72119673.434852.5634
9705.469819.47369716.373810.98699739.606785.94869771.179758.04169796.057738.8872
9817.806725.41419842.184 718.4369868.852714.73869913.475712.92779931.639 709.819
9958.262710.19039969.119 704.22410003.42700.454910023.39701.7387 10029.2706.6966
10045.09727.933410067.17737.380910078.66740.676510127.85746.427510173.67758.4814
#Mann= 3 , 0 , 0
9499.191    0.12       09499.191    0.12       010173.67    0.12       0
#XS Ineff= 2 , 0
       0                               0
Bank Sta=9499.191,10173.67
Exp/Cntr=0.3,0.1

Type RM Length L Ch R = 1 ,22371.23,476.099700,476.099700,476.099700
XS GIS Cut Line= 6
567773.363518897806076.084906925 567907.09644904806016.551092538
568018.408005423805953.187185399568094.579279504805895.966413508
568270.833175672805737.524554159568340.483503114805703.928100005
#Sta/Elev= 30
9499.074725.52749501.837725.61529511.727730.83479544.347751.79939576.968768.6466
9587.841783.62899589.765784.54349598.878787.1934 9609.95786.71549621.022788.1397
9677.115787.4953 9722.68783.14689734.417780.47839818.342768.15559822.492765.2212
9831.054755.78649883.202715.84049896.882 704.226 9899.67703.16049914.324700.8537
9943.633 700.2429978.512697.962310004.11695.002210021.26698.803510036.21705.3193
10057.23712.644510080.36716.809410127.82723.1386 10167.8739.285510184.02747.5071
#Mann= 3 , 0 , 0
9499.074    0.04       09499.074    0.04       010184.02    0.04       0
#XS Ineff= 2 , 0
       0                               0
Bank Sta=9499.074,10184.02
Exp/Cntr=0.3,0.1

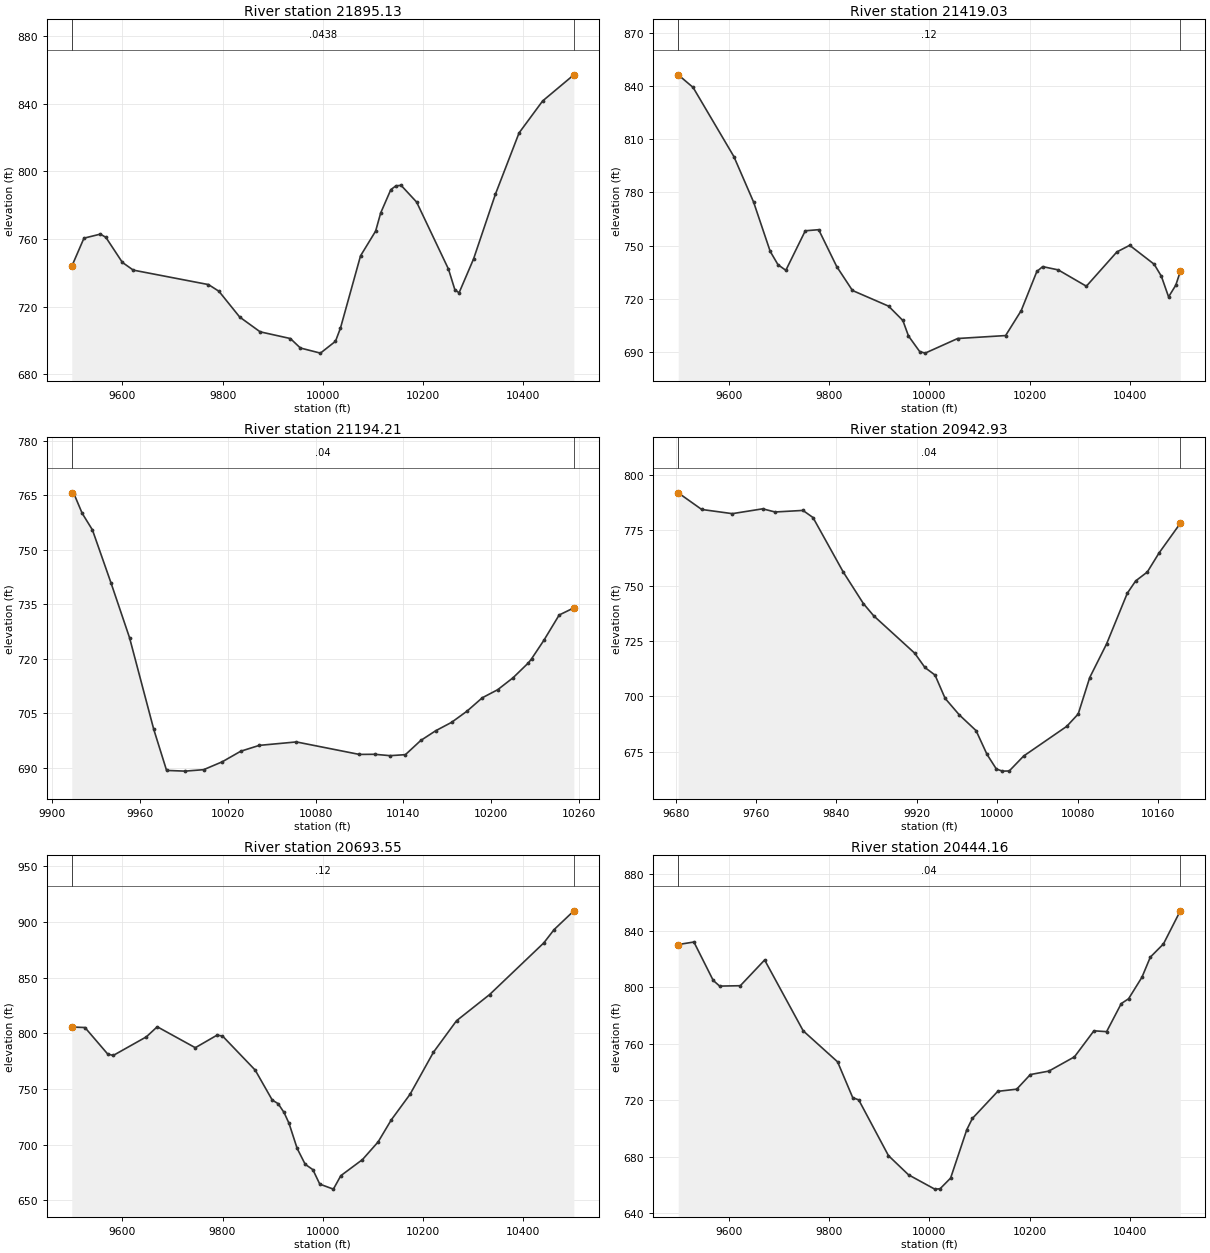
Type RM Length L Ch R = 1 ,21895.13,476.099600,476.099600,476.099600
XS GIS Cut Line= 6
567982.795249109806300.586975572568300.722699797806178.733930921
568556.250670656806166.973120187568644.941327773806149.151071322
568747.855428455806101.334778674568917.936249666805995.956617205
#Sta/Elev= 30
9499.083743.8996 9523.39760.5552 9556.23762.95679567.177761.01749600.017746.2353
9621.794 741.6629771.837733.10639792.747729.15039834.169713.90249874.914705.1719
9935.244701.19879955.246 695.5989995.248692.570610025.25699.569210035.25707.4175
10075.27750.116110105.38 764.74510115.48775.482110135.67789.250710145.89791.5082
10156.22 791.78210187.16781.907510250.69742.286110263.52730.021510271.86728.2459
10300.79 748.27510344.49 786.64810391.55 822.793 10438.6841.701410500.87 857.151
#Mann= 3 , 0 , 0
9499.083  0.0438       09499.083  0.0438       010500.87  0.0438       0
#XS Ineff= 2 , 0
       0                               0
Bank Sta=9499.083,10500.87
Exp/Cntr=0.3,0.1

Type RM Length L Ch R = 1 ,21419.03,224.828500,224.828500,224.828500
XS GIS Cut Line= 6
 568273.32507298806996.889892663568421.790079571806827.502691107
568531.118297916806676.095374856568608.510460945806508.018991908
568676.050828681806315.770430322568801.281860629 806160.48046479
#Sta/Elev= 30
9499.055846.43219528.729839.30329610.065800.29069649.415774.59339682.582746.7343
9698.174739.18759713.766736.06269752.594758.37239779.319758.98689815.342738.1418
9846.692724.66179918.776715.81869947.284707.71729958.506698.96079980.839690.1776
9991.756689.286710056.65697.541310152.29699.205610183.45713.311610214.61735.3809
10226.28 738.13810257.33 736.28210313.44727.068210374.35746.432910399.87750.1696
10448.74739.476410463.12732.692510477.49721.039810491.87727.6607 10500.9735.4258
#Mann= 3 , 0 , 0
9499.055    0.12       09499.055    0.12       0 10500.9    0.12       0
#XS Ineff= 2 , 0
       0                               0
Bank Sta=9499.055,10500.9
Exp/Cntr=0.3,0.1

Type RM Length L Ch R = 1 ,21194.21,251.271200,251.271200,251.271200
XS GIS Cut Line= 3
568846.141838849806669.359318346568723.545027137806574.151156053
568666.159285456806395.472824082
#Sta/Elev= 30
9913.515 765.6639914.961 765.4439920.622760.02799927.622755.45249940.284740.8806
9952.945725.78669969.534700.47629978.268689.20139990.929689.005610003.59689.4067
10016.25691.569510028.91694.488110041.57696.0975 10066.9697.047910109.86 693.609
10120.36693.643810130.87693.265510141.37693.538310151.87697.454510162.09700.1356
10172.88702.437210183.38705.505410193.88709.209610204.39711.430110214.89714.7225
10225.39718.8291 10227.5719.9255 10235.9725.0167 10246.4732.017710256.41733.9682
#Mann= 3 , 0 , 0
9913.515    0.04       09913.515    0.04       010256.41    0.04       0
#XS Ineff= 2 , 0
       0                10066.69       0
Bank Sta=9913.515,10256.41
Exp/Cntr=0.3,0.1

Type RM Length L Ch R = 1 ,20942.93,249.385500,249.385500,249.385500
XS GIS Cut Line= 6
568870.851601353806827.953361366568884.772303895806732.707104592
568885.520447196806681.530835295568869.672500388806550.942452615
568888.476759365806504.170065503568971.512491288806356.742597795
#Sta/Elev= 30
9682.627791.88229705.948784.37529736.409782.48439766.581784.66589778.945783.2378
9806.655783.94439816.656780.73239846.725 756.1589866.852741.84689877.039736.3841
9917.787719.52439927.964713.06059938.004 709.6539948.044699.12729962.182691.6622
9978.833684.57789989.699673.8619    9999667.250710005.05666.296510011.81666.3719
10026.18673.120910068.98686.497910080.41692.086410091.85708.5137 10108.6723.6749
10129.21746.5675 10137.6752.156610149.11756.139610160.73764.693410181.95778.1159
#Mann= 3 , 0 , 0
9682.627    0.04       09682.627    0.04       010181.95    0.04       0
#XS Ineff= 2 , 0
       0                               0
Bank Sta=9682.627,10181.95
Exp/Cntr=0.3,0.1

Type RM Length L Ch R = 1 ,20693.55,249.385600,249.385600,249.385600
XS GIS Cut Line= 6
568840.414299418807118.200085918568898.568208681807004.283707799
568988.618696995806790.341513044569025.596552325806725.602058817
569311.224314769806397.760601711569402.728657797806302.636504005
#Sta/Elev= 30
9499.117805.60339525.438805.15159570.663781.4181 9581.78780.03569647.966796.7897
9669.665805.83679745.613787.01959789.012 798.2959799.862797.54819865.171766.8916
9899.143740.02279910.926 736.748 9922.71728.83359932.656  719.06 9948.86696.5452
9964.893682.32659980.247677.48069994.005664.491910021.14660.006810035.96672.0776
10079.15686.521210110.43 702.41510136.52722.0953 10174.1745.174310220.81782.9585
10266.97811.285610332.88834.744210441.04 881.17210461.76 893.18510500.97909.9564
#Mann= 3 , 0 , 0
9499.117    0.12       09499.117    0.12       010500.97    0.12       0
#XS Ineff= 2 , 0
       0                               0
Bank Sta=9499.117,10500.97
Exp/Cntr=0.3,0.1

Type RM Length L Ch R = 1 ,20444.16,249.385500,249.385500,249.385500
XS GIS Cut Line= 6
569017.405394166807199.388158494 569238.02686899806915.079670696
569318.832238192806710.890711154569375.705402721806610.634962946
569459.421627696806503.058638469569578.265035403806381.778174905
#Sta/Elev= 30
9499.049830.35789530.336832.13999568.823804.95579581.651800.9174 9622.92801.1832
9671.454819.41429748.427769.21689817.035747.25789847.268721.8662 9859.21720.3085
9918.533680.8214 9958.56 667.23910010.91657.097510021.38657.315510042.54664.9076
10074.87699.234910085.91707.132410136.66726.364410174.44727.898610201.62738.2524
10238.64740.709210289.68750.806510328.53769.247210353.82768.639710383.07788.5294
10397.69791.955410424.32807.177610441.05821.4263 10467.3830.8114 10500.9854.2326
#Mann= 3 , 0 , 0
9499.049    0.04       09499.049    0.04       0 10500.9    0.04       0
#XS Ineff= 2 , 0
       0                               0
Bank Sta=9499.049,10500.9
Exp/Cntr=0.3,0.1

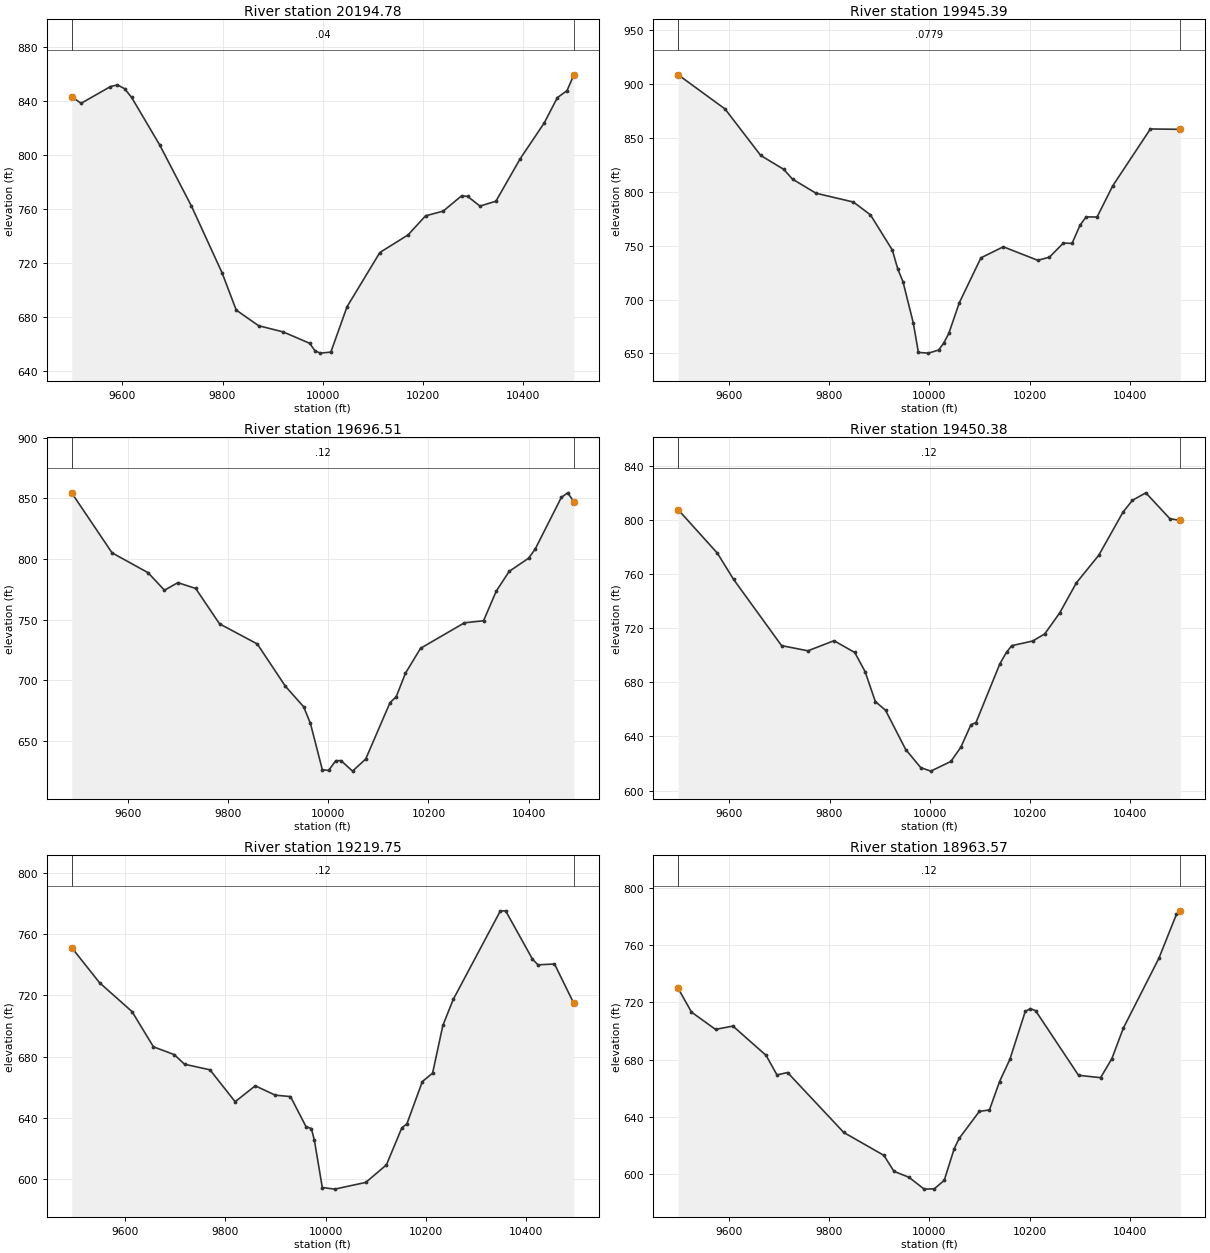
Type RM Length L Ch R = 1 ,20194.78,249.385600,249.385600,249.385600
XS GIS Cut Line= 6
569082.328483204807198.999150758569186.267670998807092.051059155
569289.316790099807009.389996451569369.114052904 806965.10647049
569651.130922332806849.723317829569910.271297226806656.233932759
#Sta/Elev= 30
9499.118 843.181 9517.85838.42099576.245850.79199590.299852.05019604.353849.2547
9618.407 842.8389674.428807.64399737.889762.31979798.875712.99769827.294685.2528
9871.856673.67859920.874669.09139973.733660.66369984.305655.18549994.877653.3668
10016.07654.124710048.37687.709510113.87727.893910170.13740.924410205.02755.0462
10240.36758.583610276.97769.891210289.17  769.43 10313.6762.286610345.43765.9001
10393.71797.247110441.95823.936110468.02842.605210487.28847.756410500.95859.5011
#Mann= 3 , 0 , 0
9499.118    0.04       09499.118    0.04       010500.95    0.04       0
#XS Ineff= 2 , 0
       0                               0
Bank Sta=9499.118,10500.95
Exp/Cntr=0.3,0.1

Type RM Length L Ch R = 1 ,19945.39,248.881200,248.881200,248.881200
XS GIS Cut Line= 6
569082.586224102807433.323160154569313.780573106 807222.74117447
569419.133524449 807169.99886763569531.484870723807157.036858585
569645.023066399807106.097561685569905.169234244806903.867655664
#Sta/Elev= 30
9499.173908.30789592.501876.6656 9663.76833.5322 9709.67820.66549727.136811.5949
9774.106798.52589848.559790.3683 9882.68778.45739926.313745.80129936.976728.4747
9947.467 716.596 9968.09678.3012 9978.25650.94889998.377650.281410018.58653.1594
10028.72659.504110038.87668.487710059.92 697.06810103.01738.636410147.67748.8682
10216.45 736.33410239.67739.267110267.45752.328510284.79752.016610300.62768.8063
10312.86776.619310334.68776.451310365.92805.375710441.03858.119510500.75 857.782
#Mann= 3 , 0 , 0
9499.173  0.0779       09499.173  0.0779       010500.75  0.0779       0
#XS Ineff= 2 , 0
       0                               0
Bank Sta=9499.173,10500.75
Exp/Cntr=0.3,0.1

Type RM Length L Ch R = 1 ,19696.51,246.131600,246.131600,246.131600
XS GIS Cut Line= 6
569382.903481803807741.712803248 569627.69039023807367.773832524
569699.107019628807270.973962555569803.917273042807121.488370364
569872.103953586807034.953277248 569962.83064715806925.762981244
#Sta/Elev= 30
9488.108854.31179568.507805.01929640.365788.64369673.122774.19059699.773780.4448
9735.418 775.6419782.944746.53169858.292729.93049914.297695.14489950.912678.1238
9964.328664.52899988.122626.323910000.56625.672710014.88633.683110025.45633.7928
10048.47625.123110074.75635.139110123.29681.636810135.43686.304410154.01705.7964
10184.12726.330510271.67747.343710309.86749.029510335.33773.537510361.06789.7261
10400.06800.667410413.06 808.22110465.07850.636610477.83854.453310490.08847.0651
#Mann= 3 , 0 , 0
9488.108    0.12       09488.108    0.12       010490.08    0.12       0
#XS Ineff= 2 , 0
       0                               0
Bank Sta=9488.108,10490.08
Exp/Cntr=0.3,0.1

Type RM Length L Ch R = 1 ,19450.38,230.632200,230.632200,230.632200
XS GIS Cut Line= 6
569752.625140252807866.177483087569818.943444444807707.286104027
569873.791624248807524.419899362569910.106511884807203.110277217
569966.624856107807072.225275143570057.874580244806927.728155805
#Sta/Elev= 30
9498.075807.66099576.175775.57589608.376756.26469704.286   707.29756.881703.3724
9808.864710.83629850.328702.11489870.923687.98249891.363665.84369911.684659.4263
9951.961630.36359981.977616.976210001.98614.392710041.99621.529810062.02632.1091
10082.06648.701810092.09650.262610139.87693.810110153.17702.361410163.51707.1698
10205.46710.625110229.32715.861410259.19731.3741 10292.5753.647110337.24774.0834
10385.56 805.94710404.39814.678110431.09820.188410479.13801.035910499.87799.7816
#Mann= 3 , 0 , 0
9498.075    0.12       09498.075    0.12       010499.87    0.12       0
#XS Ineff= 2 , 0
       0                               0
Bank Sta=9498.075,10499.87
Exp/Cntr=0.3,0.1

Type RM Length L Ch R = 1 ,19219.75,256.173800,256.173800,256.173800
XS GIS Cut Line= 6
570018.395316483807943.026623501570112.331690764807667.784361671
570110.964863203807535.202393192570076.321116962 807434.42701916
570145.081100082807154.820581786570214.060610367806990.566079457
#Sta/Elev= 30
 9493.44750.99839548.893728.13899613.695709.31749656.393686.33189697.869681.2603
9718.536 674.9639769.139671.32929819.385650.52319859.428660.89579899.511654.7932
9929.803653.87839960.826634.24299971.483633.01199977.458625.39249993.258594.5604
10018.04593.502310080.01597.884610121.18609.337410151.88633.448510162.11636.1377
10192.81663.667910213.27669.132410233.74700.246110254.43717.219510348.39 774.937
10359.01775.0397 10412.6743.508110423.57739.7993 10456.5740.3736 10495.1714.6326
#Mann= 3 , 0 , 0
 9493.44    0.12       0 9493.44    0.12       0 10495.1    0.12       0
#XS Ineff= 2 , 0
       0                               0
Bank Sta=9493.44,10495.1
Exp/Cntr=0.3,0.1

Type RM Length L Ch R = 1 ,18963.57,249.385500,249.385500,249.385500
XS GIS Cut Line= 6
570209.831213912807876.413872792570282.310363313807760.257076742
570325.877400358807630.201072506570324.568665668807327.780179204
570346.273579665807199.949696431570479.402772607806939.483462035
#Sta/Elev= 30
9499.108 729.6559525.562713.14979573.466701.05579608.237703.37359674.433682.8796
9696.117669.20779717.208670.90599829.404628.97589909.467612.97369929.519601.8081
9959.658597.63339989.797589.373210009.81589.568810029.81 595.48610049.81617.7536
10059.81624.922410099.88643.736610120.01644.734510140.22664.575410160.69680.0128
10191.51713.638710201.78715.6105 10212.2714.082510297.82668.944510341.81667.2996
10364.28 680.58410387.29702.026610458.01 750.70310492.99781.400610500.86783.9518
#Mann= 3 , 0 , 0
9499.108    0.12       09499.108    0.12       010500.86    0.12       0
#XS Ineff= 2 , 0
       0                               0
Bank Sta=9499.108,10500.86
Exp/Cntr=0.3,0.1

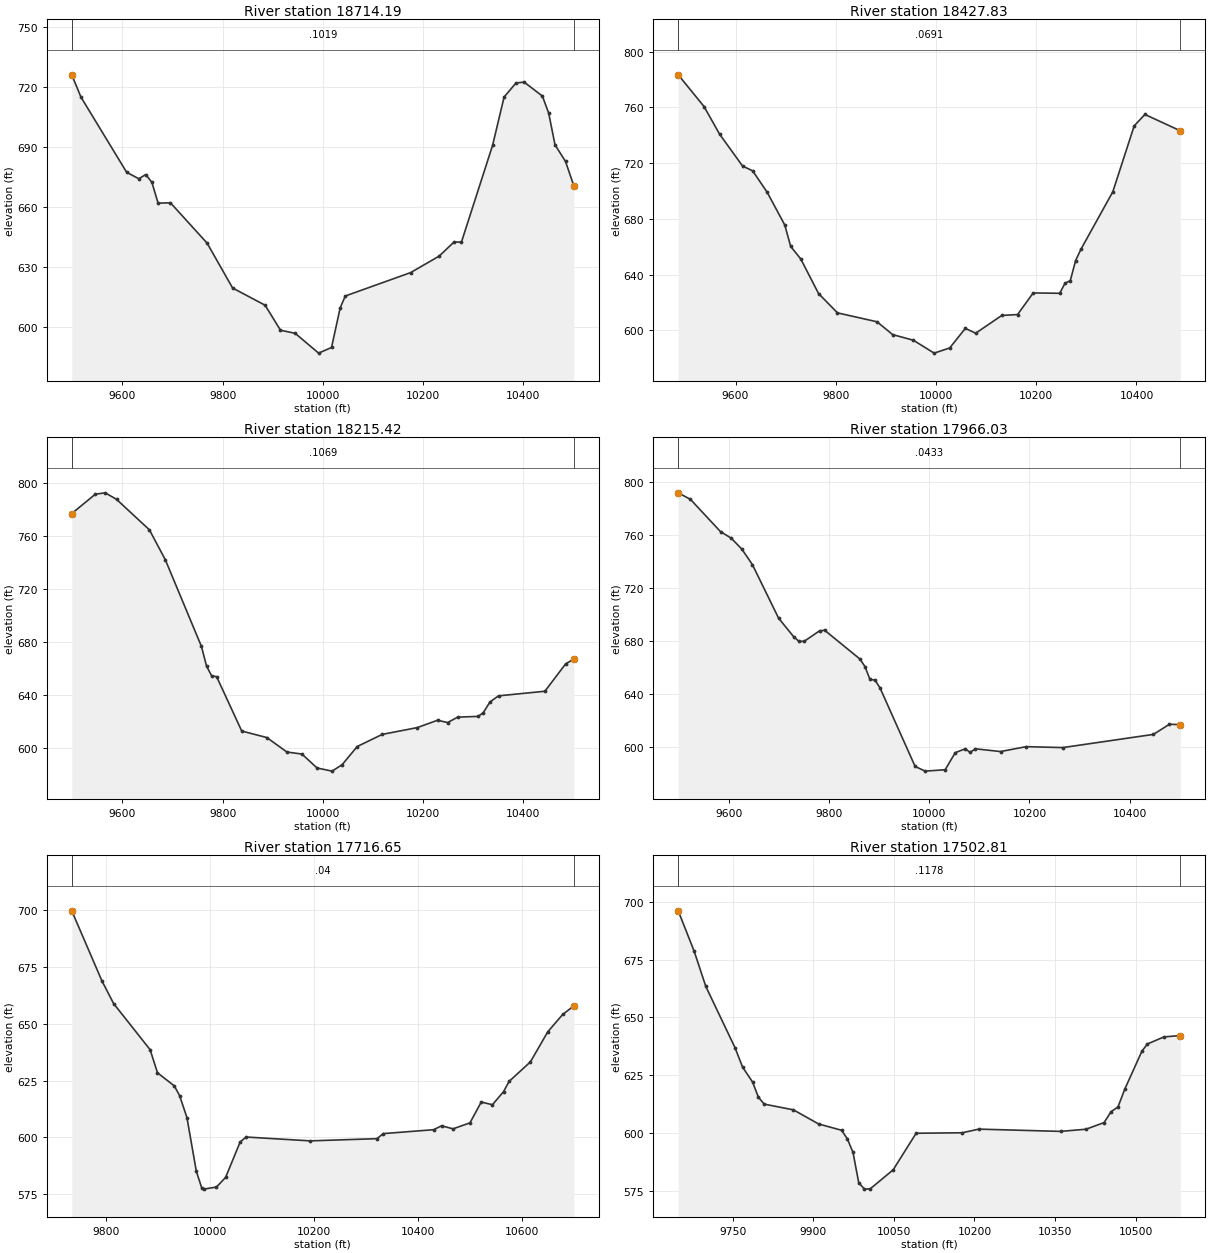
Type RM Length L Ch R = 1 ,18714.19,286.354000,286.354000,286.354000
XS GIS Cut Line= 6
570239.431525059807878.909937283 570327.02376843807773.458875322
570466.495940762807583.499609344570570.298598128807466.847077222
570748.468712666807296.146485956570924.928113112807154.950661184
#Sta/Elev= 30
9499.047726.30569517.439715.13849608.514677.59019632.924674.33629646.597676.4374
9658.943672.54679671.289662.13559695.982662.31449769.112642.14289820.005619.6993
9884.877611.09119915.556598.5811 9944.76597.06169991.594587.134710017.39  589.96
 10034.7609.8194 10044.9  615.7110175.13627.394110232.21635.654810261.78642.6947
10276.65642.676810338.86691.108210361.75715.200210385.51722.235310401.82722.6684
10438.17 715.66810450.74707.157710463.31 691.32810484.34682.974110500.93670.7783
#Mann= 3 , 0 , 0
9499.047  0.1019       09499.047  0.1019       010500.93  0.1019       0
#XS Ineff= 2 , 0
       0                               0
Bank Sta=9499.047,10500.93
Exp/Cntr=0.3,0.1

Type RM Length L Ch R = 1 ,18427.83,212.417100,212.417100,212.417100
XS GIS Cut Line= 6
570225.686524334807968.148046461570358.700482236807862.311511384
 570468.61743434807803.096911614570552.929945601807774.071896372
570865.317308758 807686.61476402571141.233516333807587.620328548
#Sta/Elev= 30
9485.623783.32729537.088760.5933 9568.14740.76789613.941717.92849634.215714.4283
9663.086699.09129698.255675.55179709.979660.24749730.122651.21559765.606626.4303
9803.358612.54489882.407606.14399913.456596.96849954.854592.90869996.293583.6624
10027.39587.383610058.49601.399610079.23597.957810131.35610.714110162.68611.3253
10194.01626.860710246.86626.588510257.43633.7575   10268635.712610278.58650.0582
10289.15658.150210352.79699.411310395.48746.701310416.82  754.9110487.51743.1708
#Mann= 3 , 0 , 0
9485.623  0.0691       09485.623  0.0691       010487.51  0.0691       0
#XS Ineff= 2 , 0
       0                               0
Bank Sta=9485.623,10487.51
Exp/Cntr=0.3,0.1

Type RM Length L Ch R = 1 ,18215.42,249.385600,249.385600,249.385600
XS GIS Cut Line= 6
570188.031098722808049.670223454570308.194640387807984.040822311
 570418.31836386807951.604325393570525.807093692807943.354556533
570856.704989675807955.027466497571160.802718311807894.891952202
#Sta/Elev= 30
9499.101776.91419546.129791.49699565.832792.53369588.411787.62939654.012764.6057
9685.808741.99669757.925676.57739768.013661.81029778.101654.50089788.188653.7675
9838.276 612.7639888.312607.86399928.369596.93219958.445595.40669988.522584.8893
10018.58582.519110038.61587.384710068.66601.0845 10118.7610.248610188.74615.3877
10228.97620.911910249.08619.162610269.23623.281310309.86623.813210320.02626.5302
10333.74634.750810350.61639.319910443.16642.800810484.59 663.49210500.95667.0127
#Mann= 3 , 0 , 0
9499.101  0.1069       09499.101  0.1069       010500.95  0.1069       0
#XS Ineff= 2 , 0
       0                               0
Bank Sta=9499.101,10500.95
Exp/Cntr=0.3,0.1

Type RM Length L Ch R = 1 ,17966.03,249.385500,249.385500,249.385500
XS GIS Cut Line= 6
570157.321532399808294.837836539570285.250349395808243.413501145
570418.206853767 808209.87021422570731.065374986808200.395371276
570812.537258809808188.654717002571125.373245391808082.060866855
#Sta/Elev= 30
9499.075 792.0529523.457787.12939583.417762.75459604.749757.84559626.081749.5126
 9647.18737.75679699.316697.40519730.021683.11389740.253679.81439750.485679.9169
 9781.09687.85299791.189688.26999861.647666.53849871.672660.84269881.696651.1359
9891.721650.66149901.727644.71159971.747585.43529991.759581.879710031.78582.9205
10051.79595.803810071.79  598.75 10081.8595.980710091.82 598.75210142.24596.6646
10193.45600.363110266.49599.6548 10447.3609.621610479.25617.280810500.95616.9592
#Mann= 3 , 0 , 0
9499.075  0.0433       09499.075  0.0433       010500.95  0.0433       0
#XS Ineff= 2 , 0
       0                               0
Bank Sta=9499.075,10500.95
Exp/Cntr=0.3,0.1

Type RM Length L Ch R = 1 ,17716.65,213.838600,213.838600,213.838600
XS GIS Cut Line= 6
570537.896700442808592.292799846570646.974861324 808505.98969999
570798.116669089808353.426919073570901.347477287 808266.90842624
571115.400694519808149.127539456 571332.66584003808068.524559915
#Sta/Elev= 30
 9733.82699.78549791.802668.91949814.222658.9487 9884.48   638.69898.644628.4176
9930.994622.64799941.135618.37439955.298 608.6679973.357584.98959983.625577.7572
9987.477577.164810012.03578.084410029.63582.341910057.65597.955810069.14600.1213
10192.19598.427310320.74599.397110332.67601.6235 10429.5603.3459 10444.9605.0628
10466.93603.730610499.47606.363510521.16615.536510542.66  614.36   10564620.0886
10574.67624.622910615.64 633.21110649.18646.509510677.96 654.16610699.22657.8836
#Mann= 3 , 0 , 0
 9733.82    0.04       0 9733.82    0.04       010699.22    0.04       0
#XS Ineff= 2 , 0
       0                               0
Bank Sta=9733.82,10699.22
Exp/Cntr=0.3,0.1

Type RM Length L Ch R = 1 ,17502.81,89.260900,89.260900,89.260900
XS GIS Cut Line= 6
570667.729639465808711.655340554570883.191708505808620.364296302
570960.448652953808413.767074093571019.650041908808335.989296302
571238.400041848808156.128185168 571334.80008027808135.397420362
#Sta/Elev= 30
9648.814696.08069678.431678.62329700.152663.36299754.455636.90899768.404628.5598
9787.037622.08549797.897615.51829808.758612.50139863.061610.03779909.898603.9326
9952.603601.20279963.279 597.5869973.956591.63879984.632578.53789995.308575.7493
10005.98575.866510048.69584.0951 10091.4599.909310177.24600.119310208.06601.6934
10360.15600.715410407.38601.649810441.09604.516610454.04609.205710466.98  611.29
10479.93619.156310511.54635.416710521.77638.509510552.45641.558310582.94642.1612
#Mann= 3 , 0 , 0
9648.814  0.1178       09648.814  0.1178       010582.94  0.1178       0
#XS Ineff= 2 , 0
       0                               0
Bank Sta=9648.814,10582.94
Exp/Cntr=0.3,0.1