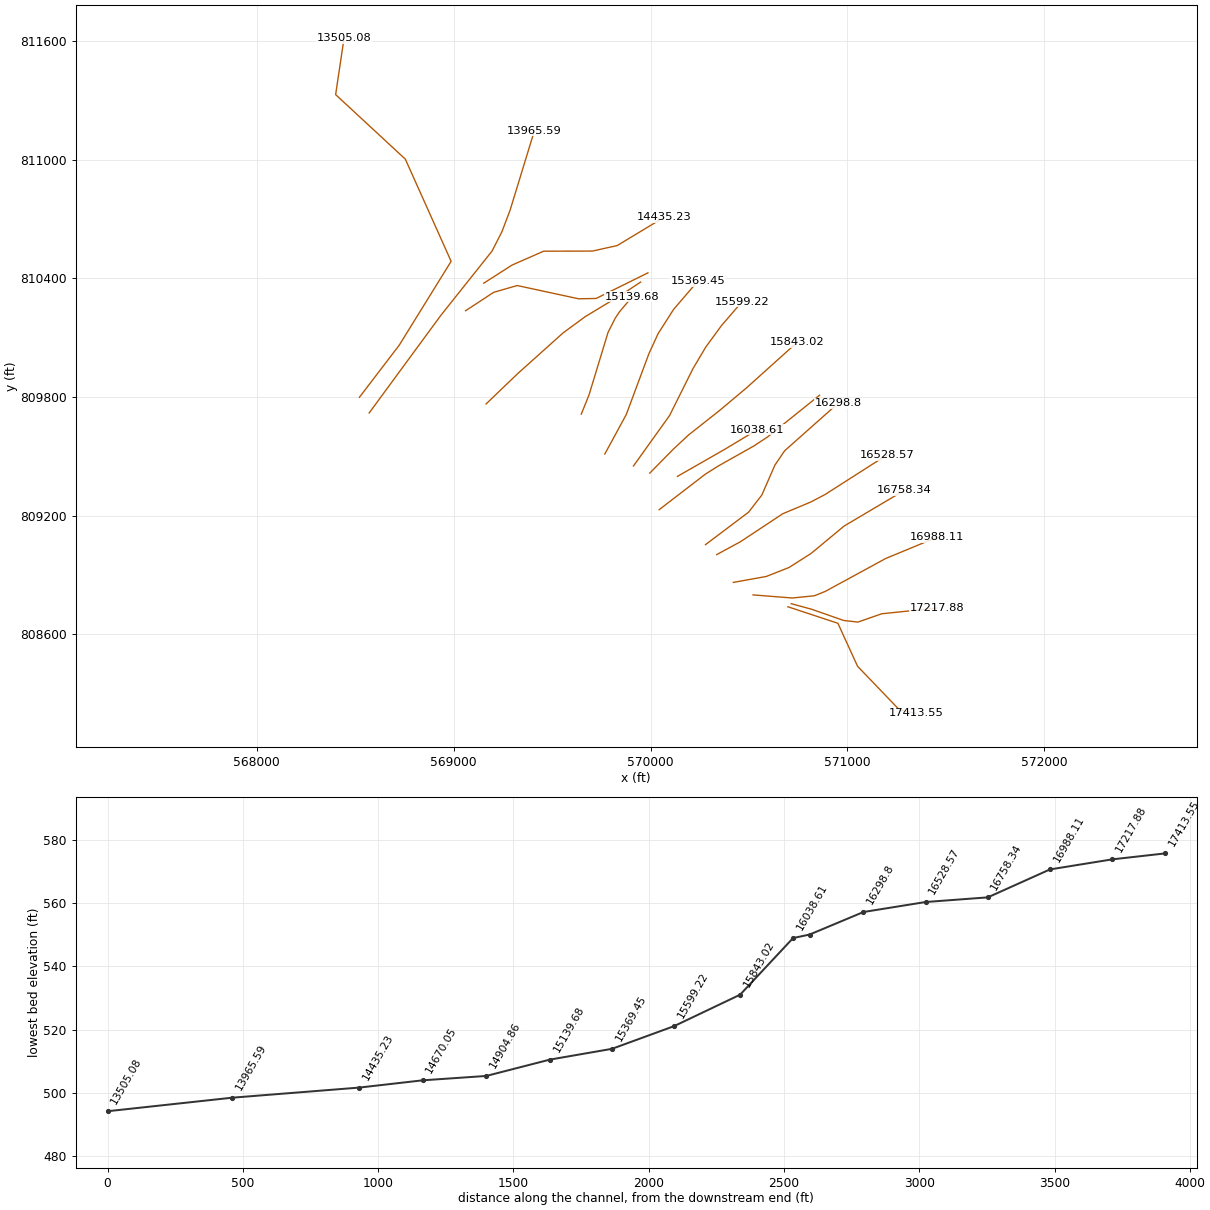
HEC-RAS study 11081_ras.prj: 11081

--- 11081_ras.g01 (geometry) --- (continued)

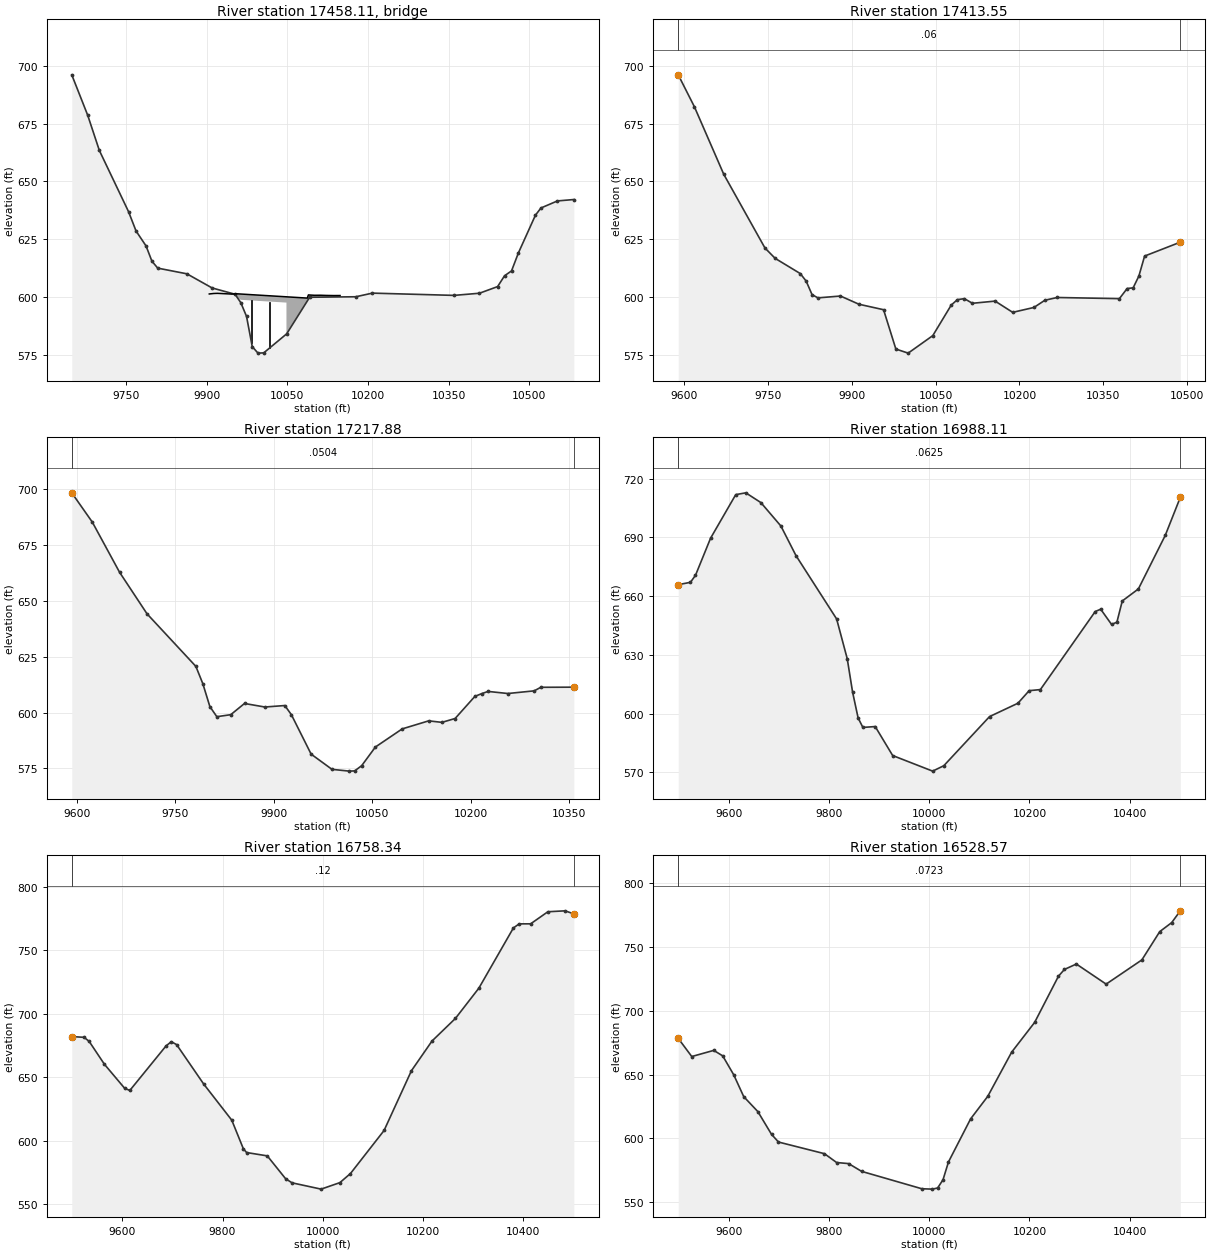
Type RM Length L Ch R = 3 ,17458.11,,,
BEGIN DESCRIPTION:
END DESCRIPTION:
Bridge Culvert--1,0,-1,-1, 0
Deck Dist Width WeirC Skew NumUp NumDn MinLoCord MaxHiCord MaxSubmerge Is_Ogee
32.655400,23.950100,2.6,0, 23, 23, , , 0.95, 0, 0,0,,
 9904.68 9913.04 9919.71 9924.04 9935.04 9943.71 9946.04 9951.77 9951.77 9956.43
10048.2310048.2310087.0310087.7210089.0510100.0510111.0510111.7210122.0510133.05
10135.7210144.0510147.99
  601.33  601.54  601.60  601.55  601.42  601.32  601.27  601.34  601.34  601.40
  600.10  600.10  599.55  600.03  600.92  600.76  600.78  600.78  600.70  600.65
  600.64  600.65  600.66
 -398.67 -398.46 -398.40 -398.45 -398.58 -398.68 -398.73 -398.66  598.84  598.90
  597.60 -399.90 -400.45 -399.97 -399.08 -399.24 -399.22 -399.22 -399.30 -399.35
 -399.36 -399.35 -399.34
 9904.68 9913.04 9919.71 9924.04 9935.04 9943.71 9946.04 9951.77 9951.77 9956.43
10048.2310048.2310087.0310087.7210089.0510100.0510111.0510111.7210122.0510133.05
10135.7210144.0510147.99
  601.33  601.54  601.60  601.55  601.42  601.32  601.27  601.34  601.34  601.40
  600.10  600.10  599.55  600.03  600.92  600.76  600.78  600.78  600.70  600.65
  600.64  600.65  600.66
 -398.67 -398.46 -398.40 -398.45 -398.58 -398.68 -398.73 -398.66  598.84  598.90
  597.60 -399.90 -400.45 -399.97 -399.08 -399.24 -399.22 -399.22 -399.30 -399.35
 -399.36 -399.35 -399.34
Pier Skew, UpSta & Num, DnSta & Num=  ,9983.42, 2 ,9983.42, 2 , 0 , 0 , 0 ,,
    3.00    3.00
 -398.99  601.01
    3.00    3.00
 -398.99  601.01
Pier Skew, UpSta & Num, DnSta & Num=  ,10016.58, 2 ,10016.58, 2 , 0 , 0 , 0 ,,
    3.00    3.00
 -399.46  600.54
    3.00    3.00
 -399.46  600.54
BR Coef=-1 , 0 , 0 ,, 0 ,,,0.8,0,1,0,
WSPro=,,,, 1 ,,,, 0 ,,,, 0 ,,,,-1 ,-1 ,-1 , 0 , 0 , 0 , 0 , 0
BC Design=,, 0 ,, 0 ,,,,,,

Type RM Length L Ch R = 1 ,17413.55,195.671600,195.671600,195.671600
XS GIS Cut Line= 5
 570697.63578347 808739.14969875570951.768097401808655.607351869
571051.768097401808437.899018511571263.400041848808218.454574093
571347.323102385808199.741638511
#Sta/Elev= 30
9589.796696.08679618.601682.32049671.233653.04689744.918621.15459763.189  616.67
9808.077610.09389818.604606.8368 9829.13600.97919839.657599.58979879.985600.3801
9912.998596.82829957.016594.46069979.025577.442710001.03575.678310045.05583.2505
10078.07 596.47310089.07598.819310101.54599.244410115.95597.242410156.48598.1884
10187.97593.323310225.95595.4406 10245.6 598.56910267.62599.747610378.77599.2486
10392.66 603.63210403.39603.921510413.64609.033910423.88617.672210487.74 623.689
#Mann= 3 , 0 , 0
9589.796    0.06       09589.796    0.06       010487.74    0.06       0
#XS Ineff= 2 , 0
       0                               0
Bank Sta=9589.796,10487.74
Exp/Cntr=0.3,0.1

Type RM Length L Ch R = 1 ,17217.88,229.769000,229.769000,229.769000
XS GIS Cut Line= 6
570714.571873955808754.719975486 570817.86506474808726.713776723
570980.906196386 808669.89547725571053.417972505808661.602174744
571174.707607538808703.750972494571455.151119739808732.416262239
#Sta/Elev= 30
 9592.18698.29199623.471685.18959664.985662.7567 9706.82 644.1589781.236620.6391
9791.866612.84889802.497602.68749813.128598.14189834.322599.04759855.267604.0566
9886.252602.47629916.676603.13549926.681599.02929956.768581.38989988.517574.5884
10014.95573.795310023.07573.895710033.77576.247810054.64584.579310095.44592.6889
10135.79 596.28610155.91595.611610176.03597.335910206.19607.236410216.23608.4206
10226.26609.450510256.37608.516810296.51609.707510306.55611.296610356.88611.3526
#Mann= 3 , 0 , 0
 9592.18  0.0504       0 9592.18  0.0504       010356.88  0.0504       0
#XS Ineff= 2 , 0
       0                               0
Bank Sta=9592.18,10356.88
Exp/Cntr=0.3,0.1

Type RM Length L Ch R = 1 ,16988.11,229.768900,229.768900,229.768900
XS GIS Cut Line= 6
570520.700823468808799.196450447570720.147822942808783.415569162
 570832.81077962 808794.82821026570887.498806755808816.806387004
571194.883459787 808983.40397674571453.034292742809089.901860947
#Sta/Elev= 30
9499.097665.8116 9523.49 667.0229533.529670.59579563.645689.54549613.839711.7859
9633.916712.70719663.974707.73449704.038695.73469734.042680.66079815.152648.3175
9836.349627.98019847.021610.94479858.053597.74449867.564592.9293 9892.16593.3798
9926.989578.582110006.78570.620910029.03 573.381 10120.3598.464210176.92  605.28
10199.33   611.710221.75612.252910331.17652.107710342.11653.2885 10363.7645.5329
10374.42646.662810385.14657.4975 10417.3663.6368 10470.9690.973710500.96710.4039
#Mann= 3 , 0 , 0
9499.097  0.0625       09499.097  0.0625       010500.96  0.0625       0
#XS Ineff= 2 , 0
       0                               0
Bank Sta=9499.097,10500.96
Exp/Cntr=0.3,0.1

Type RM Length L Ch R = 1 ,16758.34,229.768900,229.768900,229.768900
XS GIS Cut Line= 6
570420.589962238808862.369778167570587.849675046808892.391918879
 570704.04526937808938.031654812570816.192264093809009.346711725
570983.462155308809147.598141294 571290.20263701809328.468873037
#Sta/Elev= 30
 9499.15681.92289523.817 681.3399533.923678.09639564.239660.14569604.733641.1712
9614.993639.51179687.268674.57749697.794677.90179708.319675.60159762.382644.5595
9818.444616.08779841.559593.54559848.017590.61789889.292587.97839925.785570.0182
9938.582566.7683 9996.69561.7971 10034.1566.9109 10055.2 574.058 10122.3607.9821
10176.92655.053610217.93678.413410264.68696.232510311.42720.047610380.36767.4807
10391.82770.674110414.75770.716710449.14 780.22210483.53780.950310500.96778.5304
#Mann= 3 , 0 , 0
 9499.15    0.12       0 9499.15    0.12       010500.96    0.12       0
#XS Ineff= 2 , 0
       0                               0
Bank Sta=9499.15,10500.96
Exp/Cntr=0.3,0.1

Type RM Length L Ch R = 1 ,16528.57,229.769000,229.769000,229.769000
XS GIS Cut Line= 6
570336.232894284809003.067595585570456.777865755 809068.19974282
570671.966079639 809209.92946323570814.765600644809269.412618432
570886.969570704809307.218438472571199.515873335809506.277202278
#Sta/Elev= 30
9499.106678.28969526.083664.0713 9569.97668.88479587.914664.57059609.866649.7525
9629.814632.68359657.961620.99899685.209603.22549699.174597.17019790.862588.0585
9815.152 581.1429839.074580.3037 9865.07574.2179 9985.16560.623510006.24560.3293
10016.72561.226710027.49 567.69510038.31581.5616 10082.5615.278710116.73632.9203
10164.48667.522210210.29690.773710257.84726.928810269.73732.209510293.51736.4445
10352.95720.725610424.27739.675610459.94761.806110483.71768.826810500.97778.0701
#Mann= 3 , 0 , 0
9499.106  0.0723       09499.106  0.0723       010500.97  0.0723       0
#XS Ineff= 2 , 0
       0                               0
Bank Sta=9499.106,10500.97
Exp/Cntr=0.3,0.1

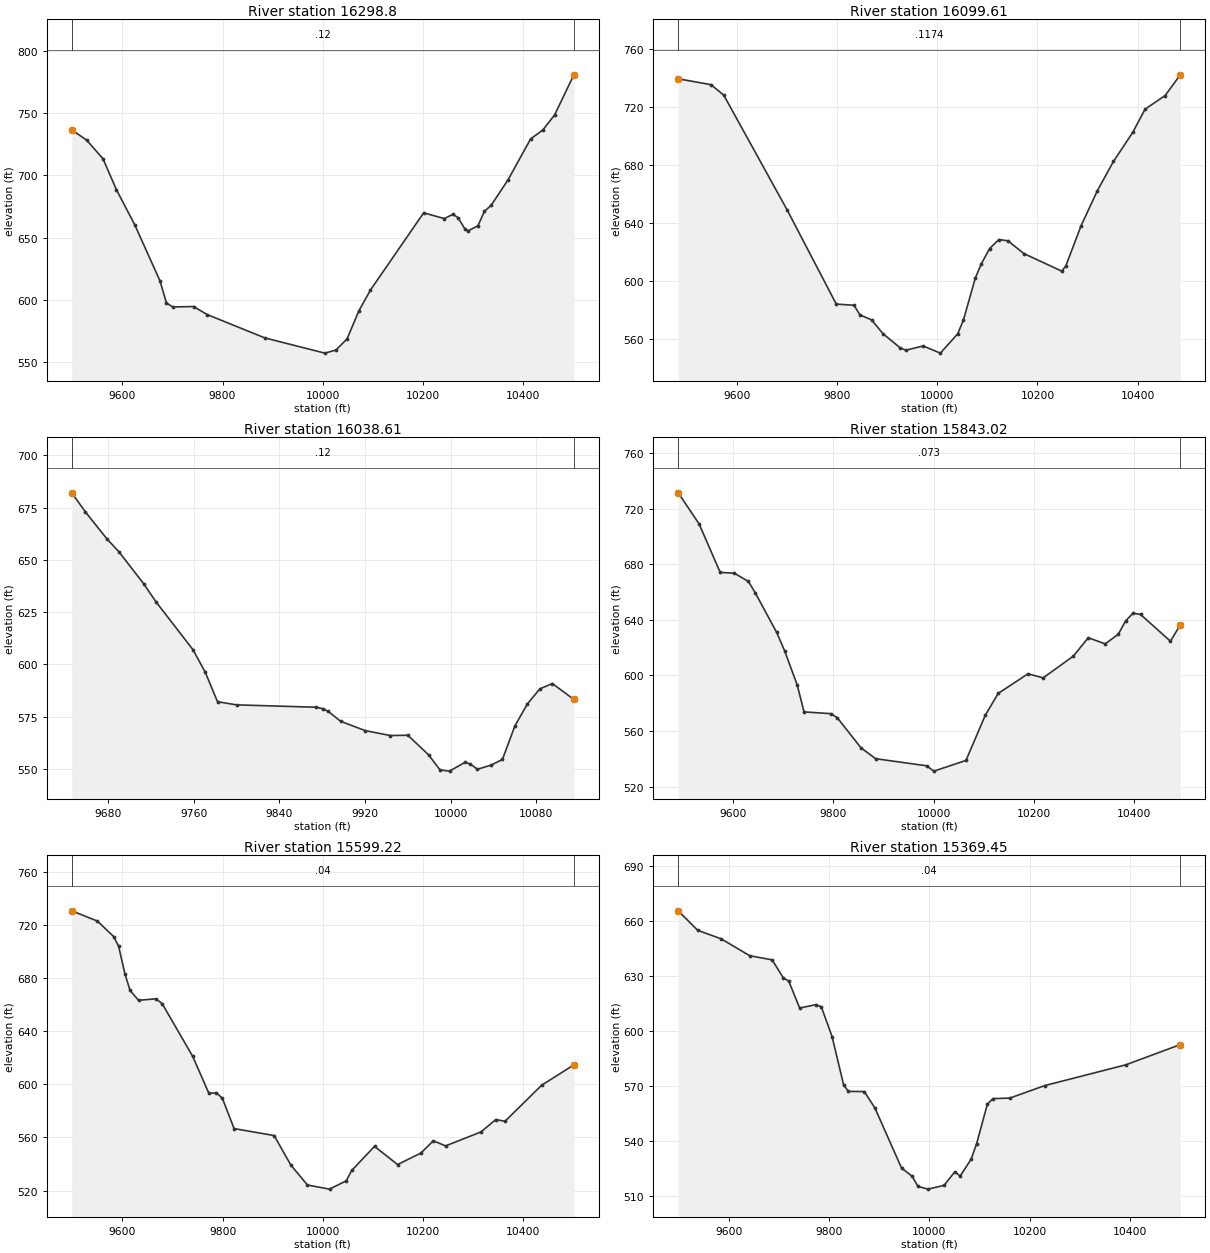
Type RM Length L Ch R = 1 , 16298.8,199.193100,199.193100,199.193100
XS GIS Cut Line= 6
570279.189610161 809053.38021579570498.143860072809217.790182062
570565.250679013809304.171807598570631.763285715809455.749855587
570681.097623734 809528.21890259570953.185391359809768.915016318
#Sta/Elev= 30
9499.181736.66759529.099728.2503 9561.56713.34779588.306688.49499624.706660.4336
 9675.26615.1597 9688.06597.48499700.965594.2696 9742.16594.61759769.623588.1218
9884.436569.404910004.07 557.17310026.28559.656410048.49 568.62410071.81591.0182
10095.18607.923410201.26669.927210242.54665.301710259.63668.7541   10270665.9523
10283.17657.219310289.84655.431510309.47659.507310322.63671.164210336.01 676.013
10369.53696.397610414.67729.318310439.16736.567610462.66 748.70210500.91780.8462
#Mann= 3 , 0 , 0
9499.181    0.12       09499.181    0.12       010500.91    0.12       0
#XS Ineff= 2 , 0
       0                               0
Bank Sta=9499.181,10500.91
Exp/Cntr=0.3,0.1

Type RM Length L Ch R = 1 ,16099.61,61.000500,61.000500,61.000500
XS GIS Cut Line= 6
570043.643060094809230.136751613570277.905279725809409.570877442
570343.600480546809450.943563598570525.116605992809552.800082875
570594.116084406809598.002232412570858.498199418809809.347027894
#Sta/Elev= 30
9483.244739.58229548.632735.52399574.096728.27359700.842648.81179798.591583.9316
9834.044583.11879845.862576.46069869.053573.03559891.908563.45749926.389553.6506
9937.619552.07069971.903555.007710006.36550.050910040.97563.4092 10052.5573.0389
10075.99601.817710087.95611.661410104.69622.298810122.94628.530510141.18627.6602
10172.96618.8431 10248.6606.683910256.46  610.1110287.27 638.15410319.84662.4016
10351.73682.453510390.41702.6677 10414.9718.624710454.87728.015510485.17742.3255
#Mann= 3 , 0 , 0
9483.244  0.1174       09483.244  0.1174       010485.17  0.1174       0
#XS Ineff= 2 , 0
       0                               0
Bank Sta=9483.244,10485.17
Exp/Cntr=0.3,0.1

Type RM Length L Ch R = 1 ,16038.61,195.586600,195.586600,195.586600
XS GIS Cut Line= 3
570136.660054743809398.720415697570376.990281671809535.741269082
570542.285279423809634.700774297
#Sta/Elev= 30
9645.896682.01899658.575672.93169678.765 659.983 9690.03653.79599713.052638.5844
9724.563 629.9299759.096607.07289770.608596.30169782.119582.14459799.906580.6254
9874.207579.49489880.666578.77369885.719577.4719 9897.23572.75659920.252568.3059
9943.533565.96999960.036  566.099979.504556.69569990.154549.50879998.971548.9417
10013.46553.145710018.44552.329710025.12549.841110037.91551.835110048.43554.5186
10060.08570.542710071.74581.0545 10083.4588.271810095.05590.8347 10115.2583.2309
#Mann= 3 , 0 , 0
9645.896    0.12       09645.896    0.12       0 10115.2    0.12       0
#XS Ineff= 2 , 0
       0                               0
Bank Sta=9645.896,10115.2
Exp/Cntr=0.3,0.1

Type RM Length L Ch R = 1 ,15843.02,243.799200,243.799200,243.799200
XS GIS Cut Line= 6
569996.140269362809415.366278916570115.724404207809536.333638278
570192.303514655809607.529624703570351.304678986809732.726533337
570487.408392626809846.454575079570746.179423718810078.213440544
#Sta/Elev= 30
9490.256731.33349531.925 708.9439573.979674.07639602.233673.47139630.356 667.548
9644.417659.06039686.673630.91019702.455 617.7339727.635593.1239 9741.29573.6888
9794.443572.43369807.453569.56339855.032547.80489884.228540.0072  9985.7534.9041
10000.42531.063410064.44  538.7510103.06571.319210128.81587.002610188.14601.0936
10218.52598.177710278.73613.824110308.54627.056910342.23622.658210368.16629.4512
10383.06639.144210397.96644.789410412.87643.791910472.48624.553310492.18636.3169
#Mann= 3 , 0 , 0
9490.256   0.073       09490.256   0.073       010492.18   0.073       0
#XS Ineff= 2 , 0
       0                               0
Bank Sta=9490.256,10492.18
Exp/Cntr=0.3,0.1

Type RM Length L Ch R = 1 ,15599.22,229.769000,229.769000,229.769000
XS GIS Cut Line= 6
569913.325780764809451.567426842570096.367173783 809706.12443978
570215.478601453809943.673370363570280.637647358810053.022149215
 570360.37031712810161.768029133570465.168226037810282.711713364
#Sta/Elev= 30
9499.054730.50389550.206722.80199582.505711.16749592.573703.85749605.176 682.998
9615.446670.6071 9632.29663.17579667.312664.3286  9679.5 660.6569740.234621.1131
9772.809593.12389787.834 593.6269799.661 589.3679822.953566.69369902.876561.4492
9936.281539.19339969.372524.233910013.39521.142810046.63527.358810057.82535.2186
10103.19553.324710149.21539.632210195.48548.222910220.62557.504810244.98553.6712
10315.58564.146910345.13573.482310363.64572.209910436.63599.269210500.96614.6168
#Mann= 3 , 0 , 0
9499.054    0.04       09499.054    0.04       010500.96    0.04       0
#XS Ineff= 2 , 0
       0                               0
Bank Sta=9499.054,10500.96
Exp/Cntr=0.3,0.1

Type RM Length L Ch R = 1 ,15369.45,229.768900,229.768900,229.768900
XS GIS Cut Line= 6
569767.653785527 809511.79536265 569876.44727253809711.138948426
569991.458502181810018.812078875570038.440459672810121.062027975
570117.451733809810244.058167328570239.639944743810385.685860439
#Sta/Elev= 30
9499.057665.35399537.909654.75889584.713650.11829641.696640.9465 9686.47638.6777
9708.558628.96059719.602627.10189741.338 612.4879773.708614.30999784.498613.1962
9806.078596.87759829.028570.76939838.447567.13999870.369567.03369891.572558.0577
 9944.58525.47979965.784520.96939977.484515.42459997.589513.966510029.54516.0202
10050.86523.392810061.65521.097610083.41530.212210094.28538.528910116.05560.3005
10127.22563.192710160.72563.492410230.07570.266510392.33581.603510500.92 592.601
#Mann= 3 , 0 , 0
9499.057    0.04       09499.057    0.04       010500.92    0.04       0
#XS Ineff= 2 , 0
       0                               0
Bank Sta=9499.057,10500.92
Exp/Cntr=0.3,0.1

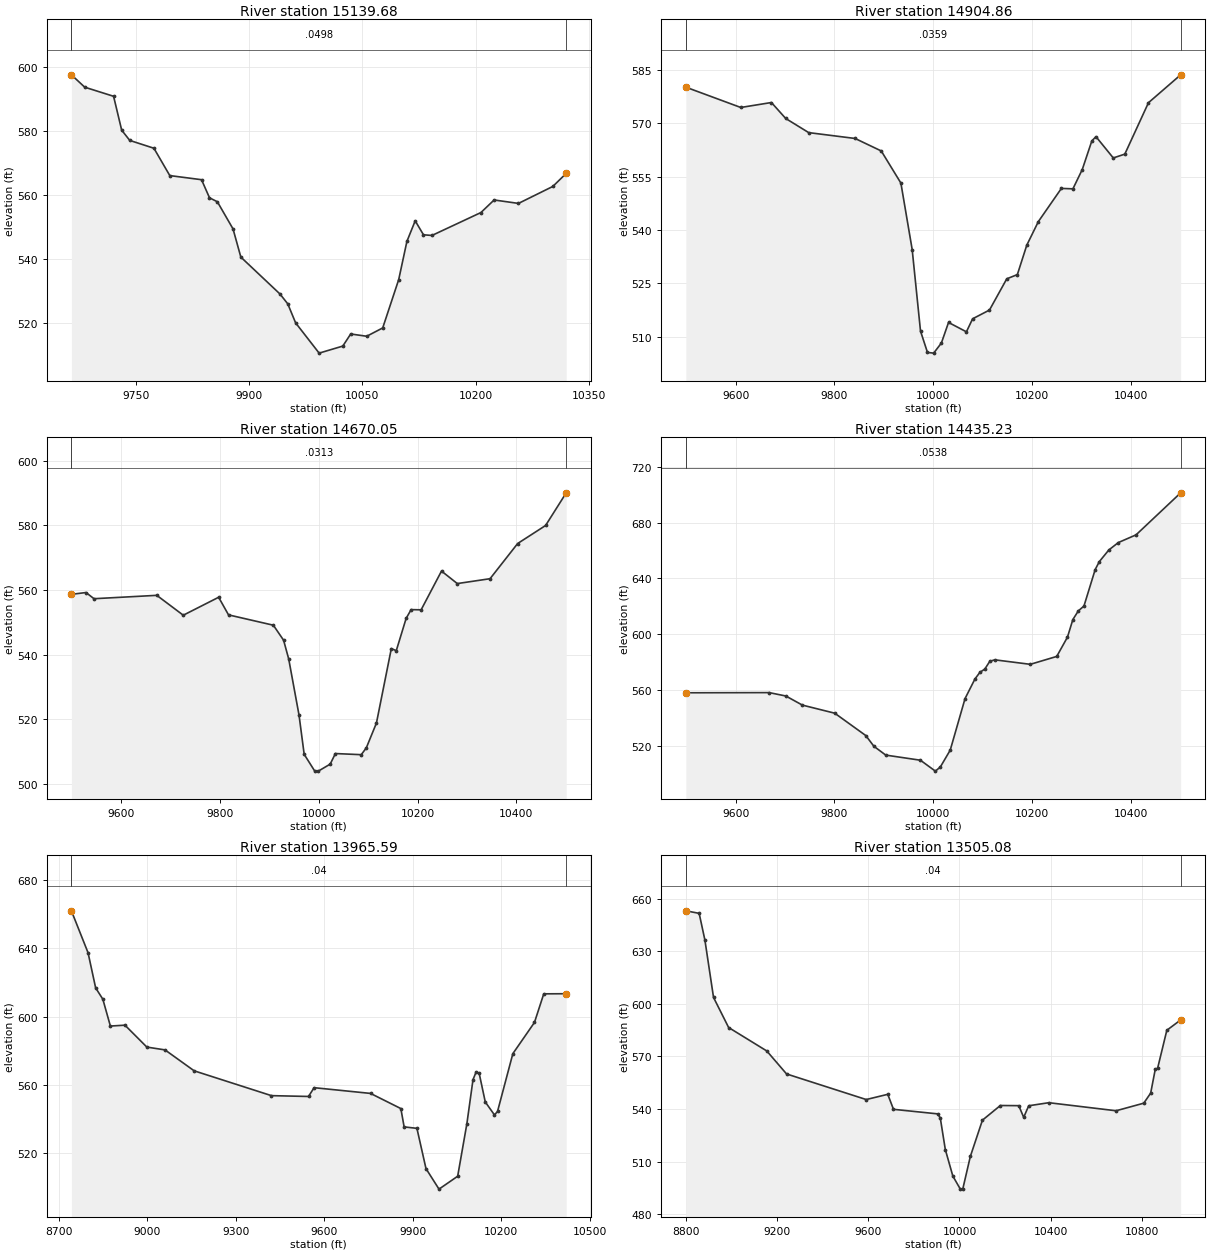
Type RM Length L Ch R = 1 ,15139.68,234.818300,234.818300,234.818300
XS GIS Cut Line= 6
569648.048053357809713.644541638569687.236369699809810.119923585
569784.090626649810127.019303556569820.684095279 810199.29648986
569842.492241438810231.748121487569906.953253847810307.540001826
#Sta/Elev= 30
9664.521597.66249682.187  593.799720.384590.94739731.102580.3542  9741.8577.1338
9773.806574.68659794.837566.1276  9836.9564.83749847.416559.17969857.866557.9245
9878.587549.43999888.948540.61279940.752529.06959951.112525.97569961.473520.0383
9992.643 510.55910023.99512.766910034.47516.551610055.66515.840310076.85518.4427
10098.04533.579310108.92545.550110119.88551.968410130.84 547.59310142.09547.3911
10206.92554.5566 10224.4558.491810256.67557.419410302.12562.722610319.91566.8158
#Mann= 3 , 0 , 0
9664.521  0.0498       09664.521  0.0498       010319.91  0.0498       0
#XS Ineff= 2 , 0
       0                               0
Bank Sta=9664.521,10319.91
Exp/Cntr=0.3,0.1

Type RM Length L Ch R = 1 ,14904.86,234.818400,234.818400,234.818400
XS GIS Cut Line= 6
569164.594080229809765.343862024569325.244682975809918.764260241
569556.531343082810125.326260862569668.632226081 810207.17613428
569857.882818958810321.181313536569949.369869325810381.794918619
#Sta/Elev= 30
 9499.05580.09369610.232574.39179672.302575.78679701.261571.29999747.772567.3331
9841.719565.68899894.701562.17939934.437553.16659957.304534.50429974.174511.6032
9988.247505.600710000.81505.403210016.44508.238210030.92514.017410067.12511.3866
10079.66515.0449 10113.8517.499610148.83526.273810170.26527.458310189.37535.7258
10212.72542.330910259.42 551.66310282.77551.5428 10301.7556.968910321.08565.0073
10329.46 566.19810364.49 560.21610387.84561.293410435.73575.731910500.95583.5619
#Mann= 3 , 0 , 0
 9499.05  0.0359       0 9499.05  0.0359       010500.95  0.0359       0
#XS Ineff= 2 , 0
       0                               0
Bank Sta=9499.05,10500.95
Exp/Cntr=0.3,0.1

Type RM Length L Ch R = 1 ,14670.05,234.818300,234.818300,234.818300
XS GIS Cut Line= 6
569060.433116876810236.876390722569203.266331906810330.052944151
569322.617868644 810364.30061536569634.893220812810297.244611821
569723.672417386810298.913491735 569986.61708502810428.486456927
#Sta/Elev= 30
 9499.15558.69899528.654559.25749544.933557.34669672.023558.38899725.605552.2411
9797.199557.79389817.205552.34869907.975549.15039928.708544.50469939.074538.6998
9959.884521.4096  9970.4509.21349991.434504.1147    9999504.021310023.04  506.19
10033.58509.458210085.93 509.10710096.19511.2236 10116.7518.910110146.79541.9239
10156.82541.272210176.85551.292310186.87553.967910207.13553.914210248.38565.8958
10280.35562.029110346.67 563.53410402.55574.418210459.08579.990610500.86590.0945
#Mann= 3 , 0 , 0
 9499.15  0.0313       0 9499.15  0.0313       010500.86  0.0313       0
#XS Ineff= 2 , 0
       0                               0
Bank Sta=9499.15,10500.86
Exp/Cntr=0.3,0.1

Type RM Length L Ch R = 1 ,14435.23,469.636700,469.636700,469.636700
XS GIS Cut Line= 6
569152.920046785810376.270755811569296.369785137810467.823592835
569457.144666257810538.112377756569705.098902705810538.703315066
569830.397671764810566.489930883570067.572034369810708.792319518
#Sta/Elev= 30
9499.103557.93559667.854558.05449701.552555.6159 9735.04549.08419800.526543.2886
9863.388527.24229879.832519.53949903.818513.22369974.019509.550910004.21501.7275
10014.26504.670610034.33516.790210064.34553.786910084.36567.818910094.37572.5816
10104.43574.981610114.49580.532410124.58581.573910196.46578.345810249.95584.0081
10271.72597.863110282.61610.464510293.71616.684110305.08620.157910327.83 646.348
10336.22652.039910355.45660.390610374.63665.686710410.57671.231310500.89701.3737
#Mann= 3 , 0 , 0
9499.103  0.0538       09499.103  0.0538       010500.89  0.0538       0
#XS Ineff= 2 , 0
       0                               0
Bank Sta=9499.103,10500.89
Exp/Cntr=0.3,0.1

Type RM Length L Ch R = 1 ,13965.59,460.507500,460.507500,460.507500
XS GIS Cut Line= 6
568570.592550496809719.700479982568934.261399851810212.800073372
569194.831806104810538.746272992569244.879027106810636.234355504
569286.681555847810746.164730437569409.776260133 811146.82125616
#Sta/Elev= 30
8743.433662.12318799.824637.4949 8825.57616.8274 8849.95610.1737  8875.5594.3951
8924.985594.90188999.028582.03619060.729580.36879159.453568.06899421.301553.4822
9546.929553.00019565.917558.16299757.144554.7948 9859.86 545.8869870.999535.1065
9914.313534.2667 9945.06  510.599989.124498.5324 10052.4506.103810083.59536.9458
10104.36562.863310114.75567.327210125.14566.737610145.91549.796410177.08542.1402
10187.46544.1845 10239.4578.164110312.63596.510110344.15 613.32810420.27613.3918
#Mann= 3 , 0 , 0
8743.433    0.04       08743.433    0.04       010420.27    0.04       0
#XS Ineff= 2 , 0
       0                               0
Bank Sta=8743.433,10420.27
Exp/Cntr=0.3,0.1

Type RM Length L Ch R = 1 ,13505.08,186.480900,186.480900,186.480900
XS GIS Cut Line= 6
 568520.90282661809798.798407789568723.033298165810062.131731257
568986.958778799810486.820527822568754.283298105811003.798397928
568400.247313172811330.301410347568442.820480734811615.009468496
#Sta/Elev= 30
8800.891653.03458859.134651.60068884.347636.35678922.166603.61538988.277586.4693
9155.528573.08359242.198559.96779591.272545.36939685.708548.34919710.743539.7887
9905.031537.18519915.997534.7604 9937.93516.82699970.828501.730410003.73494.2582
10014.69494.476410047.59512.909410100.59533.608310179.18541.965110259.73541.8781
10281.43535.221410303.37541.817410391.59543.567210686.21538.963310807.54543.2918
10837.87 549.036 10858.1562.701610868.21563.175210908.65 584.89110969.33590.7935
#Mann= 3 , 0 , 0
8800.891    0.04       08800.891    0.04       010969.33    0.04       0
#XS Ineff= 2 , 0
       0                               0
Bank Sta=8800.891,10969.33
Exp/Cntr=0.3,0.1