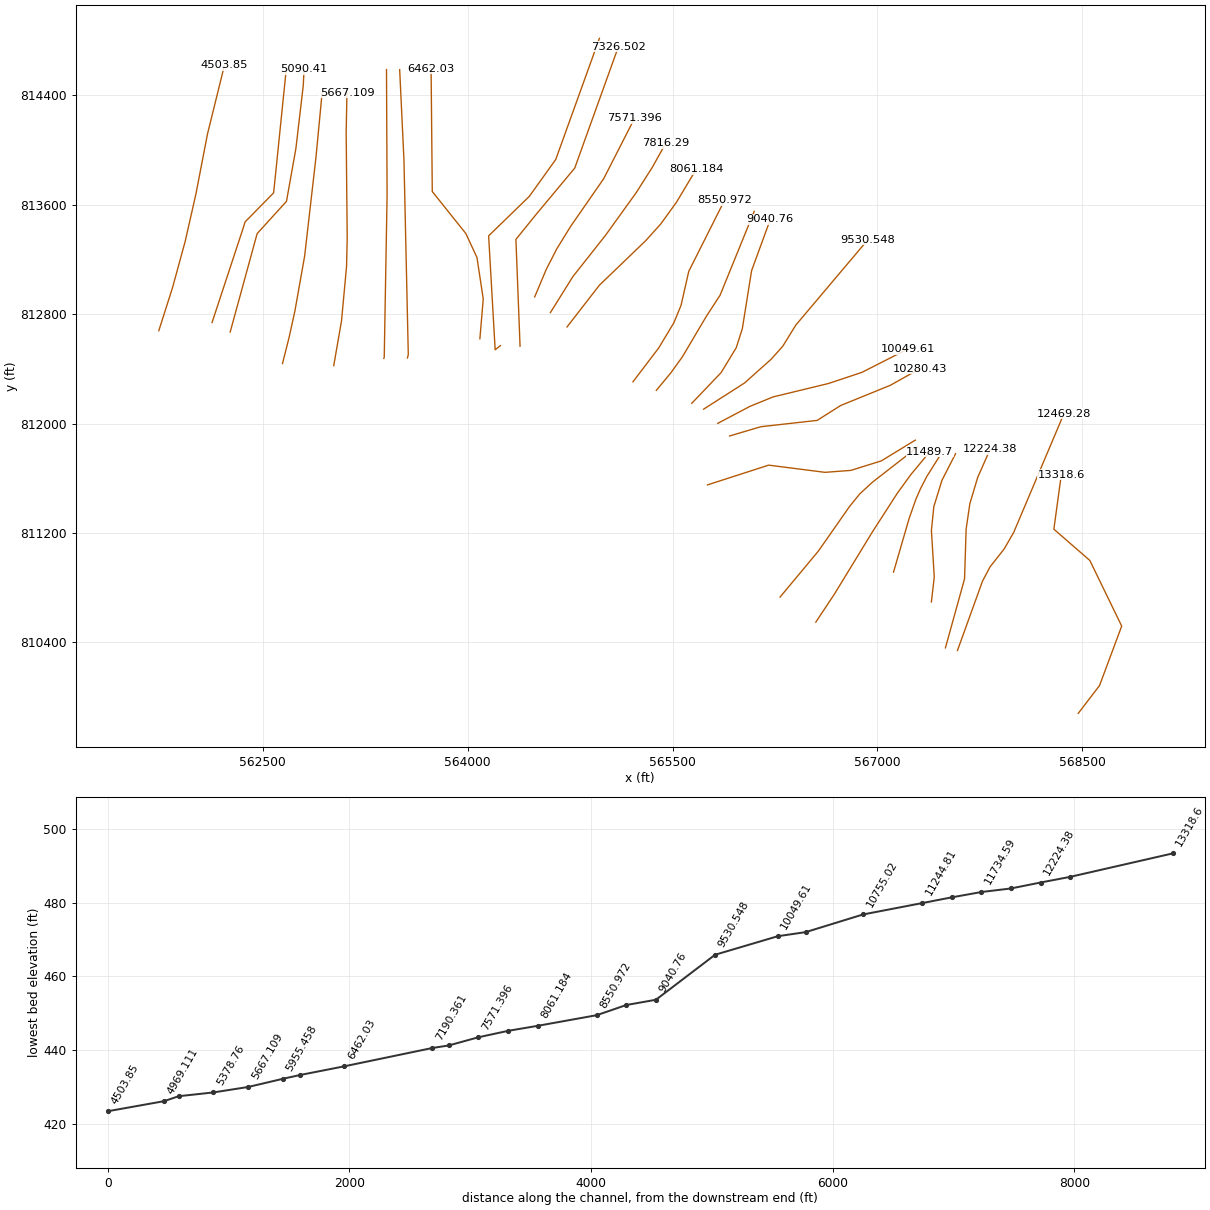
HEC-RAS study 11081_ras.prj: 11081

--- 11081_ras.g01 (geometry) --- (continued)

Type RM Length L Ch R = 3 ,13423.96,,,
BEGIN DESCRIPTION:
END DESCRIPTION:
Bridge Culvert--1,0,-1,-1, 0
Deck Dist Width WeirC Skew NumUp NumDn MinLoCord MaxHiCord MaxSubmerge Is_Ogee
76.016100,34.448700,2.6,0, 37, 37, , , 0.95, 0, 0,0,,
 9617.35 9638.36 9660.65 9690.62 9754.89 9802.21 9824.44 9857.79 9884.96 9935.20
 9935.2010064.8010064.8010113.4810117.1510133.3710150.0010186.9110199.2110260.73
10322.7910348.7410367.2410426.5110441.3310457.1610467.4410471.4510495.2610505.21
10522.0910544.9110557.3210569.7410582.1510606.9710635.88
  543.62  542.20  540.93  539.03  535.68  533.46  532.63  532.18  532.01  530.84
  530.84  527.84  527.84  526.69  526.66  526.22  526.10  526.31  526.46  527.59
  529.42  529.85  530.43  531.75  532.22  532.54  532.81  533.00  533.52  533.87
  534.30  534.60  535.00  535.17  535.44  536.13  536.43
 -456.38 -457.80 -459.07 -460.97 -464.32 -466.54 -467.37 -467.82 -467.99 -469.16
  527.84  524.84 -472.16 -473.31 -473.34 -473.78 -473.90 -473.69 -473.54 -472.41
 -470.58 -470.15 -469.57 -468.25 -467.78 -467.46 -467.19 -467.00 -466.48 -466.13
 -465.70 -465.40 -465.00 -464.83 -464.56 -463.87 -463.57
 9617.35 9638.36 9660.65 9690.62 9754.89 9802.21 9824.44 9857.79 9884.96 9935.20
 9935.2010064.8010064.8010113.4810117.1510133.3710150.0010186.9110199.2110260.73
10322.7910348.7410367.2410426.5110441.3310457.1610467.4410471.4510495.2610505.21
10522.0910544.9110557.3210569.7410582.1510606.9710635.88
  543.62  542.20  540.93  539.03  535.68  533.46  532.63  532.18  532.01  530.84
  530.84  527.84  527.84  526.69  526.66  526.22  526.10  526.31  526.46  527.59
  529.42  529.85  530.43  531.75  532.22  532.54  532.81  533.00  533.52  533.87
  534.30  534.60  535.00  535.17  535.44  536.13  536.43
 -456.38 -457.80 -459.07 -460.97 -464.32 -466.54 -467.37 -467.82 -467.99 -469.16
  527.84  524.84 -472.16 -473.31 -473.34 -473.78 -473.90 -473.69 -473.54 -472.41
 -470.58 -470.15 -469.57 -468.25 -467.78 -467.46 -467.19 -467.00 -466.48 -466.13
 -465.70 -465.40 -465.00 -464.83 -464.56 -463.87 -463.57
Pier Skew, UpSta & Num, DnSta & Num=  ,9977.90, 2 ,9977.90, 2 , 0 , 0 , 0 ,,
    3.00    3.00
 -470.14  529.86
    3.00    3.00
 -470.14  529.86
Pier Skew, UpSta & Num, DnSta & Num=  ,10022.10, 2 ,10022.10, 2 , 0 , 0 , 0 ,,
    3.00    3.00
 -471.17  528.83
    3.00    3.00
 -471.17  528.83
BR Coef=-1 , 0 , 0 ,, 0 ,,,0.8,0,1,0,
WSPro=,,,, 1 ,,,, 0 ,,,, 0 ,,,,-1 ,-1 ,-1 , 0 , 0 , 0 , 0 , 0
BC Design=,, 0 ,, 0 ,,,,,,

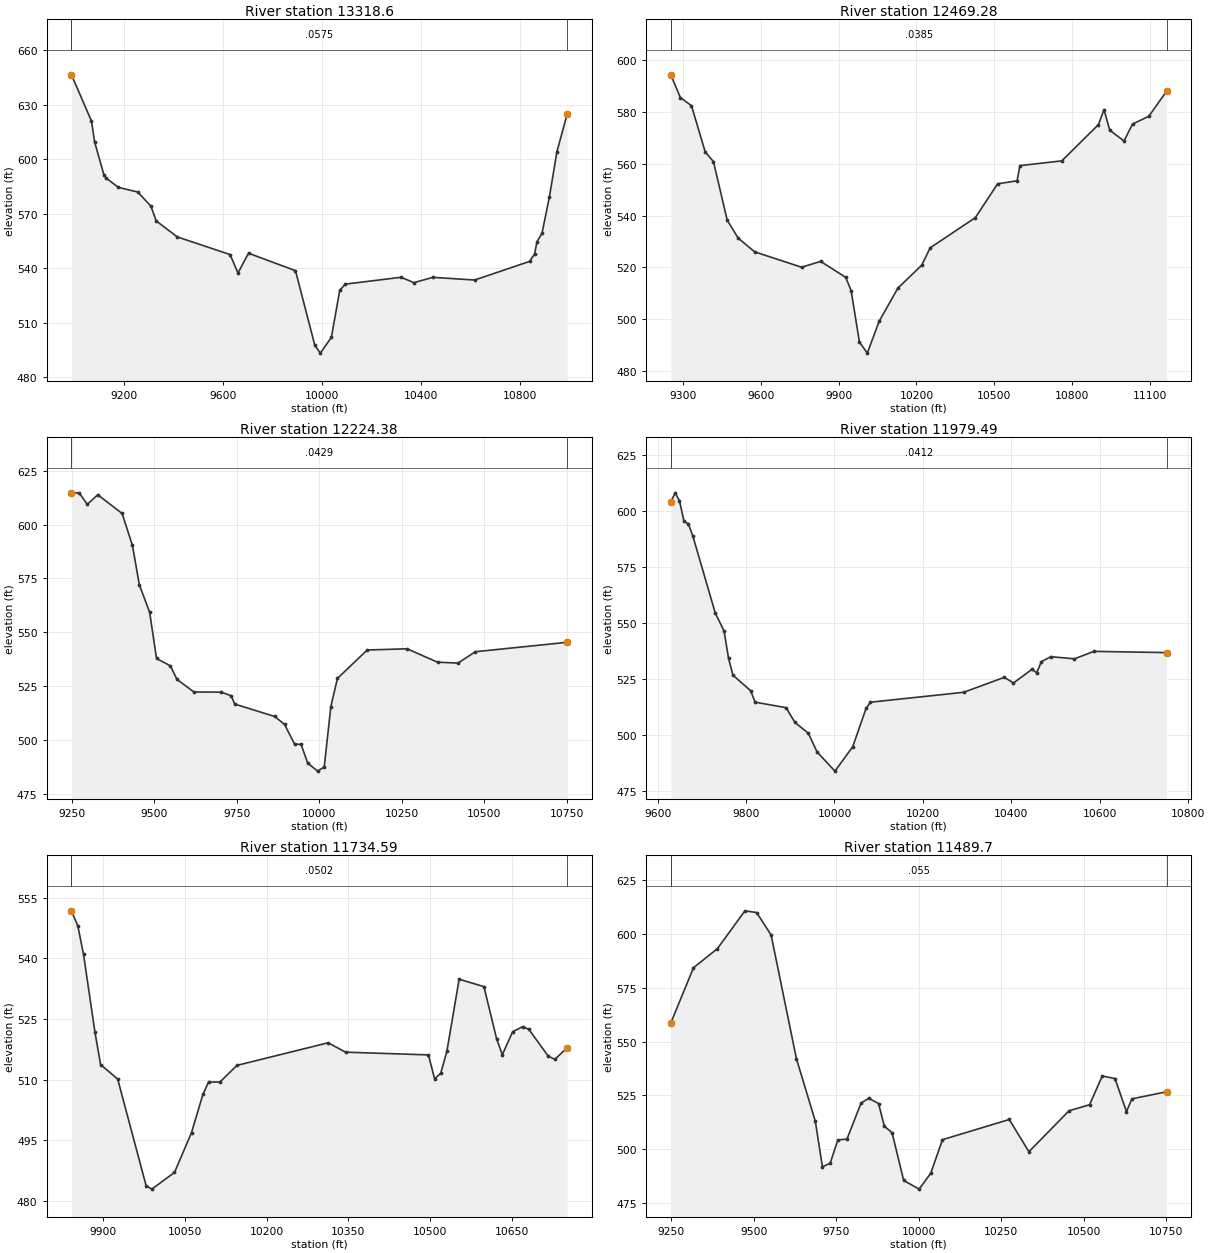
Type RM Length L Ch R = 1 , 13318.6,849.324700,849.324700,849.324700
XS GIS Cut Line= 6
568469.469658861809880.671613581568625.290242523810083.659509048
568787.790242553810519.076175734568554.575045675 810999.02895017
568291.153571278811227.859725893568345.700442225811625.652760401
#Sta/Elev= 30
8985.491646.45969066.588621.02989079.194  609.519117.014591.31499125.955589.6223
9175.223 584.5239253.495581.96219306.863574.19749328.211566.0791  9413.6557.2645
9627.075547.54639659.096 537.4139701.791548.2868 9891.65538.68429969.912497.6031
9992.273493.305910036.99502.038710070.54527.7753 10092.9531.269710318.76535.0399
10370.94532.090210447.18535.017510616.17533.533610838.23543.757210858.42547.7991
10868.51554.5939 10888.7559.237410918.98579.470710949.26604.256110990.29624.6792
#Mann= 3 , 0 , 0
8985.491  0.0575       08985.491  0.0575       010990.29  0.0575       0
#XS Ineff= 2 , 0
       0                               0
Bank Sta=8985.491,10990.29
Exp/Cntr=0.3,0.1

Type RM Length L Ch R = 1 ,12469.28,244.894100,244.894100,244.894100
XS GIS Cut Line= 6
567585.517000176810340.606926172567768.967334365810848.157155073
567824.067693093810952.350370195567927.213465114811082.923364937
 567997.69095076811205.247332792568364.884511835812072.721773329
#Sta/Elev= 30
9254.401594.3139 9291.11585.52419333.792 582.4119386.684564.5732 9418.42560.8376
9471.313538.24019513.627531.32159577.099526.01529758.048520.08389830.802522.3422
9927.624516.17859948.543510.98759980.299491.229810010.66486.9511 10056.3499.2228
10128.33512.017110219.72520.830510252.82527.582110426.52539.216610512.26552.2646
10587.28553.4353   10598  559.28 10759.4561.115810900.05575.071310921.97580.8938
 10943.9572.944110998.72568.805611031.62575.310911094.53 578.35311162.41587.9475
#Mann= 3 , 0 , 0
9254.401  0.0385       09254.401  0.0385       011162.41  0.0385       0
#XS Ineff= 2 , 0
       0                               0
Bank Sta=9254.401,11162.41
Exp/Cntr=0.3,0.1

Type RM Length L Ch R = 1 ,12224.38,244.894000,244.894000,244.894000
XS GIS Cut Line= 6
567497.303008625810359.670691001567637.422416699810864.612776518
567649.053843544811229.462582942567676.489003282811415.498552974
567733.670088077811606.511651187567824.010955589811810.956332317
#Sta/Elev= 30
9249.084614.78869272.772 614.7389297.015609.40949328.736613.89249402.593605.1954
9433.888590.30719454.752572.06489486.048559.20799506.911537.78029548.438534.3943
 9569.06528.04719620.106522.20339702.746522.15079733.331520.43589743.526516.6121
 9864.82510.8363 9894.89507.1172 9924.93498.0239 9944.93497.82589964.935489.1677
 9994.99485.422510015.03 487.37510035.05515.457110055.07528.534610145.14541.7234
 10266.1542.2908 10358.3536.061310420.39  535.6510472.87540.923910750.88545.2973
#Mann= 3 , 0 , 0
9249.084  0.0429       09249.084  0.0429       010750.88  0.0429       0
#XS Ineff= 2 , 0
       0                               0
Bank Sta=9249.084,10750.88
Exp/Cntr=0.3,0.1

Type RM Length L Ch R = 1 ,11979.49,244.894100,244.894100,244.894100
XS GIS Cut Line= 6
567394.681962968810695.805927044567415.682888402810878.237688763
567394.789165315811218.321753627567412.592108233811393.138604404
 567471.90563785 811585.29099811567571.549855992811779.751174393
#Sta/Elev= 30
9630.047604.16969639.812608.13059649.572 604.5479659.678595.47869669.784594.2162
 9679.89588.73849730.404554.49859750.455546.34129760.481534.23179770.506526.6728
9810.609519.70669820.617514.60829890.632512.16349910.672 505.5429940.734500.7949
 9960.82492.344710001.07 483.812 10041.3494.698110071.48511.812910081.49 514.604
10292.24519.028910384.16525.705710404.79523.180410446.67529.291710457.32527.7736
10467.97532.709910489.28534.937610542.82533.979210586.54537.307110750.89536.7546
#Mann= 3 , 0 , 0
9630.047  0.0412       09630.047  0.0412       010750.89  0.0412       0
#XS Ineff= 2 , 0
       0                               0
Bank Sta=9630.047,10750.89
Exp/Cntr=0.3,0.1

Type RM Length L Ch R = 1 ,11734.59,244.894100,244.894100,244.894100
XS GIS Cut Line= 6
567117.431801463810913.805217488567231.066946089811304.098176325
567281.163754283811446.838866589567314.711972048811523.649817541
567361.249851604811613.611855238567449.471341133  811753.8051525
#Sta/Elev= 30
9842.335551.7948 9854.06548.05259864.487541.00369885.339 521.7899895.766513.6964
9927.045510.12229979.176483.71859989.603482.845510031.22486.973510062.44496.8437
10083.26506.293710093.66509.370610114.48509.3749 10145.7513.500310312.96519.1044
10344.76516.780510496.75 516.10110508.01510.182510519.27511.552210530.53516.9735
10553.04 534.85510598.46533.012810621.65520.1323 10632.2516.149810651.21521.8537
10669.52523.086910680.74522.446410716.55515.752810728.49 515.01310750.94517.8356
#Mann= 3 , 0 , 0
9842.335  0.0502       09842.335  0.0502       010750.94  0.0502       0
#XS Ineff= 2 , 0
       0                               0
Bank Sta=9842.335,10750.94
Exp/Cntr=0.3,0.1

Type RM Length L Ch R = 1 , 11489.7,244.894100,244.894100,244.894100
XS GIS Cut Line= 6
566548.682419634 810548.27074197566684.288216529810752.270686099
566964.652927855811210.790842232567144.889235704 811490.11988449
567243.786177912811626.400210079567383.442869337811794.669564236
#Sta/Elev= 30
9249.024558.75339317.606584.38289390.143 593.2899473.461610.86869508.927610.0868
9552.812599.62849629.409542.14759686.856512.93129708.267491.80259731.719493.4276
9755.171504.33589782.602504.66839825.526521.47649848.978523.64999878.348521.2366
9895.881510.68399919.333507.67249954.511485.440210001.38 481.40710036.46488.7704
10072.16504.406410274.48513.803910333.98498.794910455.52517.848910518.03520.6803
10556.21534.0386 10594.8532.844910629.62517.5011 10646.3523.414110750.98526.6897
#Mann= 3 , 0 , 0
9249.024   0.055       09249.024   0.055       010750.98   0.055       0
#XS Ineff= 2 , 0
       09860.073        10291.48       0
Bank Sta=9249.024,10750.98
Exp/Cntr=0.3,0.1

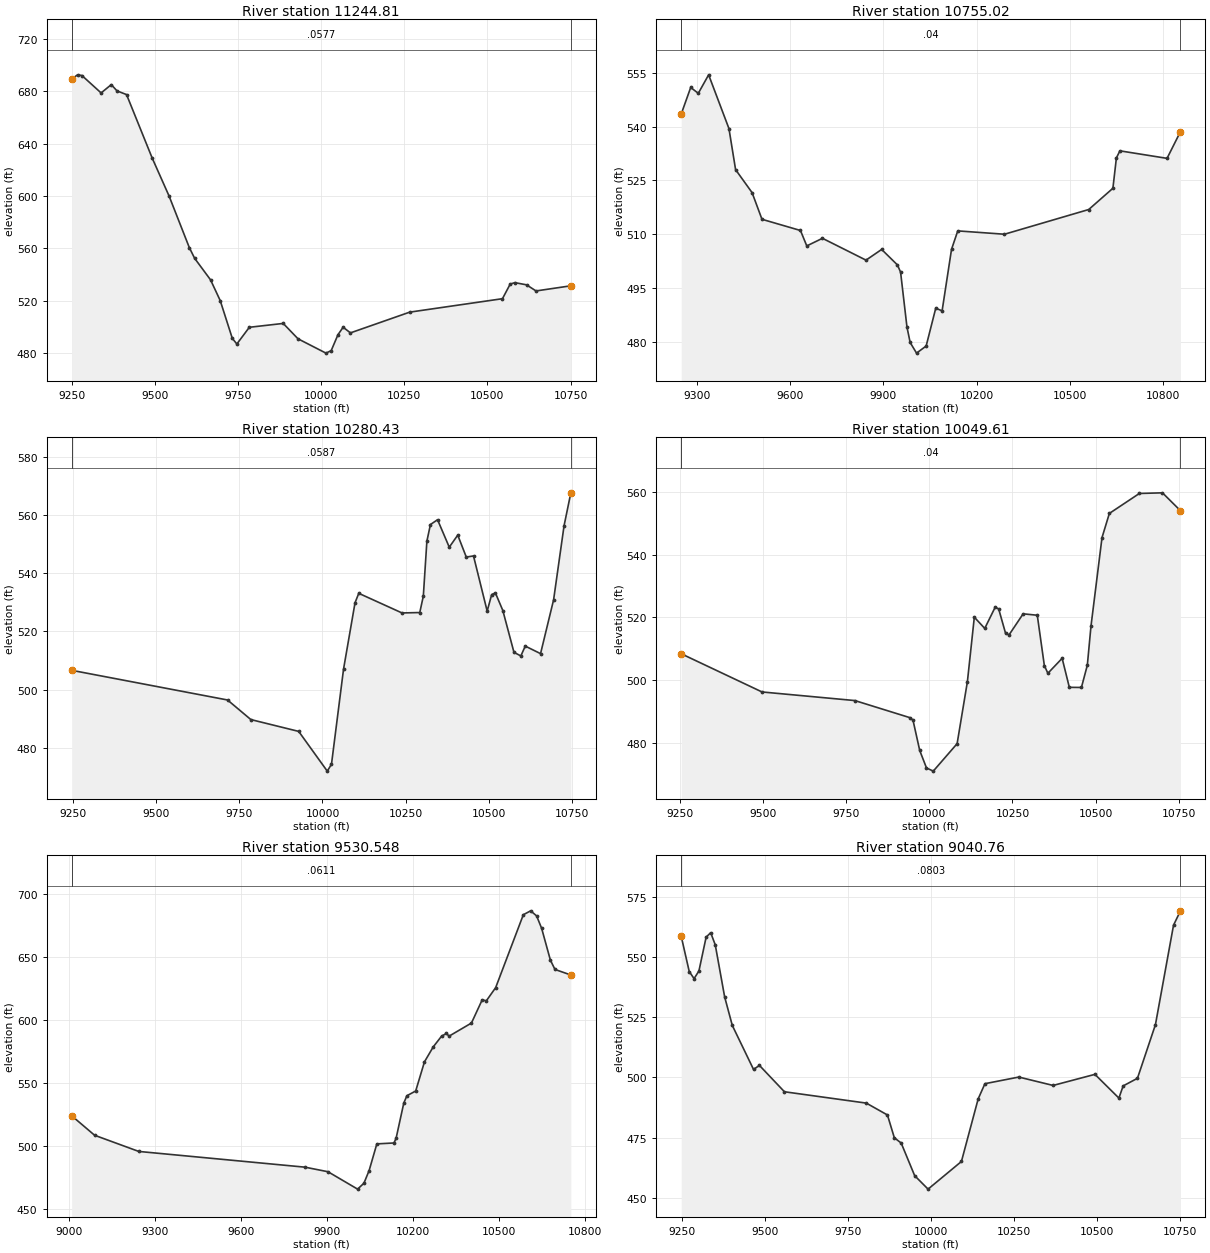
Type RM Length L Ch R = 1 ,11244.81,489.788100,489.788100,489.788100
XS GIS Cut Line= 6
566287.049510079810731.529882101566566.639008932811066.634024782
566797.281075004811396.147434639566871.890702255 811487.41900994
  566963.8015565811572.082551054567295.559861825811829.622160162
#Sta/Elev= 30
9249.037689.27599266.828692.53779280.036692.00339337.744678.70149368.359685.0507
9385.699680.22769414.282677.44759491.488 628.881 9542.24599.8924 9603.15 560.482
9619.102552.32029666.958535.86079696.015520.03879732.528491.06819746.174 486.838
9783.654499.59729885.619502.54599930.127490.795510014.21479.850310029.95 481.766
10050.34493.926210065.83 499.64310087.86495.324310266.19511.172910545.24521.4519
10568.48532.630710582.63533.713610617.71532.039110646.15527.370610750.93 531.299
#Mann= 3 , 0 , 0
9249.037  0.0577       09249.037  0.0577       010750.93  0.0577       0
#XS Ineff= 2 , 0
       09840.191                       0
Bank Sta=9249.037,10750.93
Exp/Cntr=0.3,0.1

Type RM Length L Ch R = 1 ,10755.02,474.590600,474.590600,474.590600
XS GIS Cut Line= 6
565755.546707094 811551.74268423566203.436751306 811696.18392688
 566616.21565181811643.612447917566805.204634339811657.903557152
567028.083029389811727.374371767567276.951731265811879.100799024
#Sta/Elev= 30
9249.095543.5237 9279.59550.92589304.009549.29739337.322554.45459402.752539.4566
9424.147527.9844 9477.24521.57289509.096514.12899633.089510.99919653.403506.6934
9703.899508.81889844.189502.72329894.521505.71129945.305 501.3939955.508499.3785
9976.061 484.0439986.338479.735310006.91476.766710037.83478.746910068.75489.3087
10089.23488.569310119.56505.735710139.67510.890110290.15509.958210561.45516.8561
10639.27522.784110650.57531.270410661.86533.235510813.64531.138510856.84538.5974
#Mann= 3 , 0 , 0
9249.095    0.04       09249.095    0.04       010856.84    0.04       0
#XS Ineff= 2 , 0
       0                               0
Bank Sta=9249.095,10856.84
Exp/Cntr=0.3,0.1

Type RM Length L Ch R = 1 ,10280.43,230.817900,230.817900,230.817900
XS GIS Cut Line= 6
565917.624173856811909.593150095566147.142150443811977.438615518
566558.550122394812023.561886673566731.071300254812132.734353571
567092.828589784812279.648224764567312.289591488812402.465778975
#Sta/Elev= 30
9245.348506.60849714.355496.41519784.502489.69079928.438485.627610014.38471.9837
10027.04474.333410063.45507.096110097.93529.816510109.14533.0445 10239.2 526.304
10292.66526.443910303.36532.083710314.05550.954810324.74556.661910346.13558.3201
10381.37548.894710406.91553.028710432.56545.4964 10454.3545.881410495.41526.9354
10509.01532.608210520.18533.175910542.52527.142210576.04512.773410596.75511.5394
10609.97514.9191   10656 512.33310695.27530.823910726.74556.261310747.12 567.555
#Mann= 3 , 0 , 0
9245.348  0.0587       09245.348  0.0587       010747.12  0.0587       0
#XS Ineff= 2 , 0
       0                               0
Bank Sta=9245.348,10747.12
Exp/Cntr=0.3,0.1

Type RM Length L Ch R = 1 ,10049.61,519.061900,519.061900,519.061900
XS GIS Cut Line= 6
565830.432484098812001.680320819566066.507937088 812126.20579717
566236.013770098812195.216940468566641.003013936812293.285895408
566886.588261146812375.056159519567221.210863544812544.879879055
#Sta/Elev= 30
9253.463508.39129496.494496.18379775.874493.43129940.388488.00279950.574487.2352
9970.944477.48319991.315471.891810011.71470.878110083.45479.659510114.36499.4568
10135.19520.081710166.59516.496610197.99523.280610208.45522.725610229.38514.8736
10239.85514.456710282.11521.159610324.62520.705410345.88504.618410356.51502.1513
 10399.4506.938810421.05497.661610457.46497.6192 10475.2504.735710486.19517.2324
10519.36545.524610541.47553.2497 10631.7559.626310701.25559.832810755.35554.1233
#Mann= 3 , 0 , 0
9253.463    0.04       09253.463    0.04       010755.35    0.04       0
#XS Ineff= 2 , 0
       0                               0
Bank Sta=9253.463,10755.35
Exp/Cntr=0.3,0.1

Type RM Length L Ch R = 1 ,9530.548,489.788100,489.788100,489.788100
XS GIS Cut Line= 6
565727.427641958 812105.69787015566025.935488403812296.457156628
566219.875649512812469.104685679566306.519367397812565.691685811
566402.186767876812720.591981918566929.590621352813344.619027287
#Sta/Elev= 30
9007.698523.99679087.889508.53299242.167 495.7099822.746483.24749902.997479.6268
10006.32465.855710028.48470.558810046.62480.605610073.49501.6905 10133.3502.4167
10140.66506.033710167.53533.962610178.46539.848110209.16543.571510239.86566.7173
10270.56578.563510299.36 586.97610316.61589.193710325.73587.0272 10403.9597.4253
10441.45 615.83210455.84615.017710488.48625.482110585.06683.218410610.66686.3091
10631.49682.273610649.06672.397210679.55647.261310695.57639.866310750.98635.4829
#Mann= 3 , 0 , 0
9007.698  0.0611       09007.698  0.0611       010750.98  0.0611       0
#XS Ineff= 2 , 0
       0                               0
Bank Sta=9007.698,10750.98
Exp/Cntr=0.3,0.1

Type RM Length L Ch R = 1 , 9040.76,244.894100,244.894100,244.894100
XS GIS Cut Line= 6
 565640.47461485812148.519493337565855.281491131812372.787293618
565966.103709189812554.944031808566010.628308098812694.064767263
566078.520264116 813118.74258288566215.773774775813494.124582951
#Sta/Elev= 30
9249.104558.58039273.147543.99559287.736541.04169302.325544.22549323.989558.2599
9337.723560.10469351.457555.06189379.705 533.4559402.763521.59349466.534 503.366
9484.411505.01049559.553494.0801  9805.9489.36849869.465484.43649890.207474.9693
9910.738472.80439951.354459.24889991.672453.661810092.04465.142410142.45491.1377
10162.72497.430110264.63 500.182 10367.8 496.70410493.63501.303610565.76491.4542
10578.61 496.51210621.57499.670210675.69 521.93610730.12563.229110750.94569.1852
#Mann= 3 , 0 , 0
9249.104  0.0803       09249.104  0.0803       010750.94  0.0803       0
#XS Ineff= 2 , 0
       0                               0
Bank Sta=9249.104,10750.94
Exp/Cntr=0.3,0.1

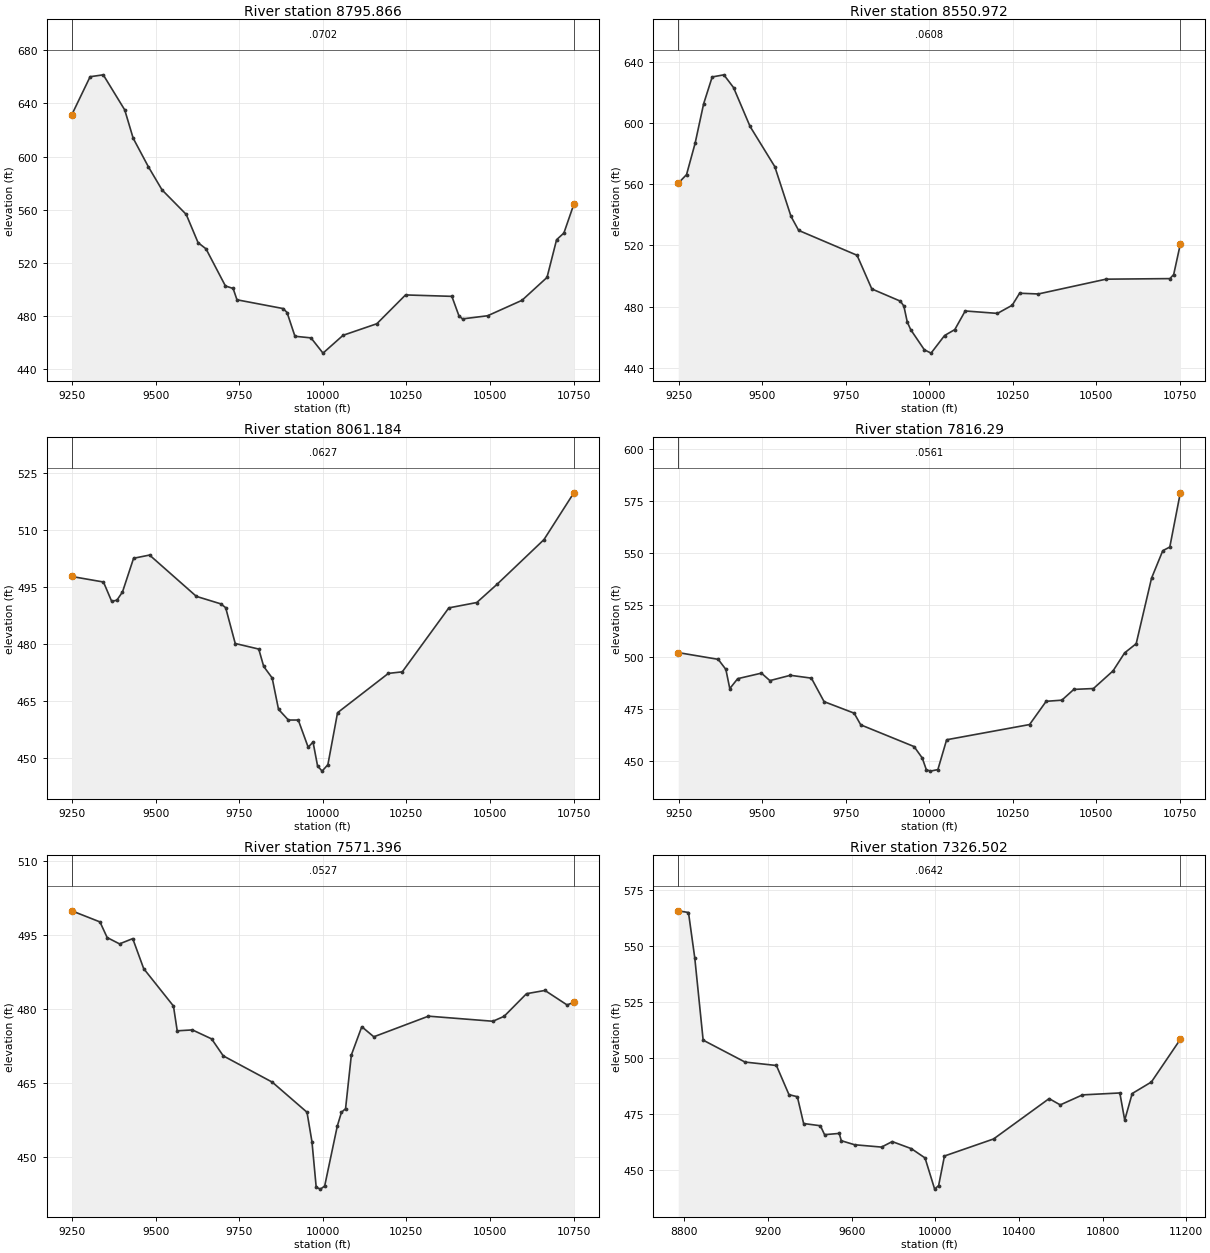
Type RM Length L Ch R = 1 ,8795.866,244.894000,244.894000,244.894000
XS GIS Cut Line= 6
565381.194489581812243.175847368565487.516370183812371.422172495
565572.373899015812489.064517893 565746.79660784812784.003760695
565847.482110612812938.315515472566097.554495865813552.158192857
#Sta/Elev= 30
9249.057631.34089303.908659.94679343.252661.37389407.465635.01769432.679613.7719
9478.309592.23449519.113574.90289591.416556.48879626.902535.23579650.559530.6323
9708.677 502.7169731.728500.83559743.254492.3245 9881.56485.72649893.085482.7429
9916.656464.91729964.647463.6992 10000.6452.243210060.57465.631210161.64474.3271
10247.47495.974210386.07494.906810407.39480.1637 10418.1477.970610493.11480.3317
10595.78491.923310670.68509.116510699.36537.476210721.24 542.51110750.95564.1554
#Mann= 3 , 0 , 0
9249.057  0.0702       09249.057  0.0702       010750.95  0.0702       0
#XS Ineff= 2 , 0
       0                               0
Bank Sta=9249.057,10750.95
Exp/Cntr=0.3,0.1

Type RM Length L Ch R = 1 ,8550.972,489.788200,489.788200,489.788200
XS GIS Cut Line= 6
565209.922701209812305.554958568565398.241984845812552.801435384
565508.578685247812735.736354076565561.594475465812863.431760187
565618.732446846 813114.08185867 565879.89271684813632.622325838
#Sta/Elev= 30
9249.157 560.6939274.019566.3719 9299.59586.83629325.161612.75329350.733630.2982
 9385.69631.68989414.661623.32039464.026 597.892 9538.07571.54489586.456539.0156
9609.394 529.829    9784513.55949828.154491.51249913.789483.49329924.059480.2582
9934.329469.7836  9944.6464.82469985.279 451.67510005.39449.485110045.79461.0114
10076.37464.882110107.52477.089410203.99475.499210248.04480.823610270.26488.7027
10326.19488.220710528.66497.900610719.87498.274910731.12500.958210750.94520.8251
#Mann= 3 , 0 , 0
9249.157  0.0608       09249.157  0.0608       010750.94  0.0608       0
#XS Ineff= 2 , 0
       0                               0
Bank Sta=9249.157,10750.94
Exp/Cntr=0.3,0.1

Type RM Length L Ch R = 1 ,8061.184,244.894100,244.894100,244.894100
XS GIS Cut Line= 6
  564727.3417228812706.926239585564964.507613134813012.374463101
565303.212910028813337.731212434565413.132058607813459.654228842
565527.984702176813618.012966659565674.562612626813862.495862859
#Sta/Elev= 30
9249.036 497.7699343.862496.31759368.533491.21439384.142491.55699400.739493.6963
9433.933502.5571 9481.76503.40439621.792492.54059694.952490.56989709.397489.5682
9738.034480.15159808.384478.68989823.164474.12399848.544471.08129867.503462.8446
9897.063 460.0289926.623460.03379956.183452.88689970.768454.24239984.348447.9545
9997.929 446.59810015.19448.299710044.12461.962210196.07472.290110237.72472.7008
   10377489.5183 10460.6490.925210521.27495.719310661.55507.461910750.94519.7638
#Mann= 3 , 0 , 0
9249.036  0.0627       09249.036  0.0627       010750.94  0.0627       0
#XS Ineff= 2 , 0
       0                               0
Bank Sta=9249.036,10750.94
Exp/Cntr=0.3,0.1

Type RM Length L Ch R = 1 , 7816.29,244.894000,244.894000,244.894000
XS GIS Cut Line= 6
564605.619427781812811.704596557564770.277819133813075.178870706
565009.171655739813377.208683906565233.344989901813688.337735394
565352.908215343813876.510522322  565449.9791353814050.656191292
#Sta/Elev= 30
9249.053502.24399368.594     4999391.527494.16679403.255484.93249426.891489.7011
9497.893492.36269523.266488.77049584.415491.32339647.368489.96119685.339478.6561
9775.255473.11959795.037467.49329954.581457.05019978.974451.56259991.171445.9352
10003.27  445.2410025.73 445.97810051.96460.326710300.02467.6414 10349.7478.8163
10396.59479.360610432.44484.544910491.13484.963710549.81493.466910584.41502.1139
10618.98506.524410664.93538.049210698.52551.259910719.52553.010210750.97579.0786
#Mann= 3 , 0 , 0
9249.053  0.0561       09249.053  0.0561       010750.97  0.0561       0
#XS Ineff= 2 , 0
       0                               0
Bank Sta=9249.053,10750.97
Exp/Cntr=0.3,0.1

Type RM Length L Ch R = 1 ,7571.396,244.894100,244.894100,244.894100
XS GIS Cut Line= 6
564490.702136891812926.722247054 564575.57861066813128.233924205
564652.347566508813278.092280455564754.048365111813442.767333052
564995.961646218813791.549640017565221.896940178 814233.36846632
#Sta/Elev= 30
9249.043499.92569333.375497.67889354.922494.50489391.953493.22599431.409494.2924
9464.197488.2053 9553.24480.62259564.467475.59919609.907 475.7829667.365473.9647
 9702.18470.52239848.846465.1924 9952.72459.09299967.608453.09549980.244443.8883
 9992.88443.504510005.58444.131610043.44456.317610055.77459.064810068.09459.8231
10085.41470.702510116.58476.430410152.61474.388910316.07  478.5710508.91477.5396
 10542.4 478.54110609.37 483.12510664.57 483.78510730.72480.845210750.97481.3941
#Mann= 3 , 0 , 0
9249.043  0.0527       09249.043  0.0527       010750.97  0.0527       0
#XS Ineff= 2 , 0
       0                               0
Bank Sta=9249.043,10750.97
Exp/Cntr=0.3,0.1

Type RM Length L Ch R = 1 ,7326.502,136.140600,136.140600,136.140600
XS GIS Cut Line= 5
564383.628804356 812566.01592733564353.246859908813347.265927315
564500.816304356813529.557594001564783.843589276813868.759595573
565102.920393914814755.066995904
#Sta/Elev= 30
8771.034565.56948820.055564.81398850.077544.52418890.108507.82049090.259498.0327
9240.372496.49839300.418483.47829340.448482.55559370.471 470.5839450.531469.5957
9470.546465.60789540.599 466.1679550.607462.90819614.289461.10339742.948 460.065
 9793.94462.52519885.665459.35089950.784455.21879996.855 441.288 10015.9442.9053
10043.68456.079210278.33463.681510544.03481.711610597.18 478.90310703.46 483.373
10882.09484.2323 10905.4472.111910941.13 483.98211032.94 489.13111171.17508.1697
#Mann= 3 , 0 , 0
8771.034  0.0642       08771.034  0.0642       011171.17  0.0642       0
#XS Ineff= 2 , 0
       0                               0
Bank Sta=8771.034,11171.17
Exp/Cntr=0.3,0.1

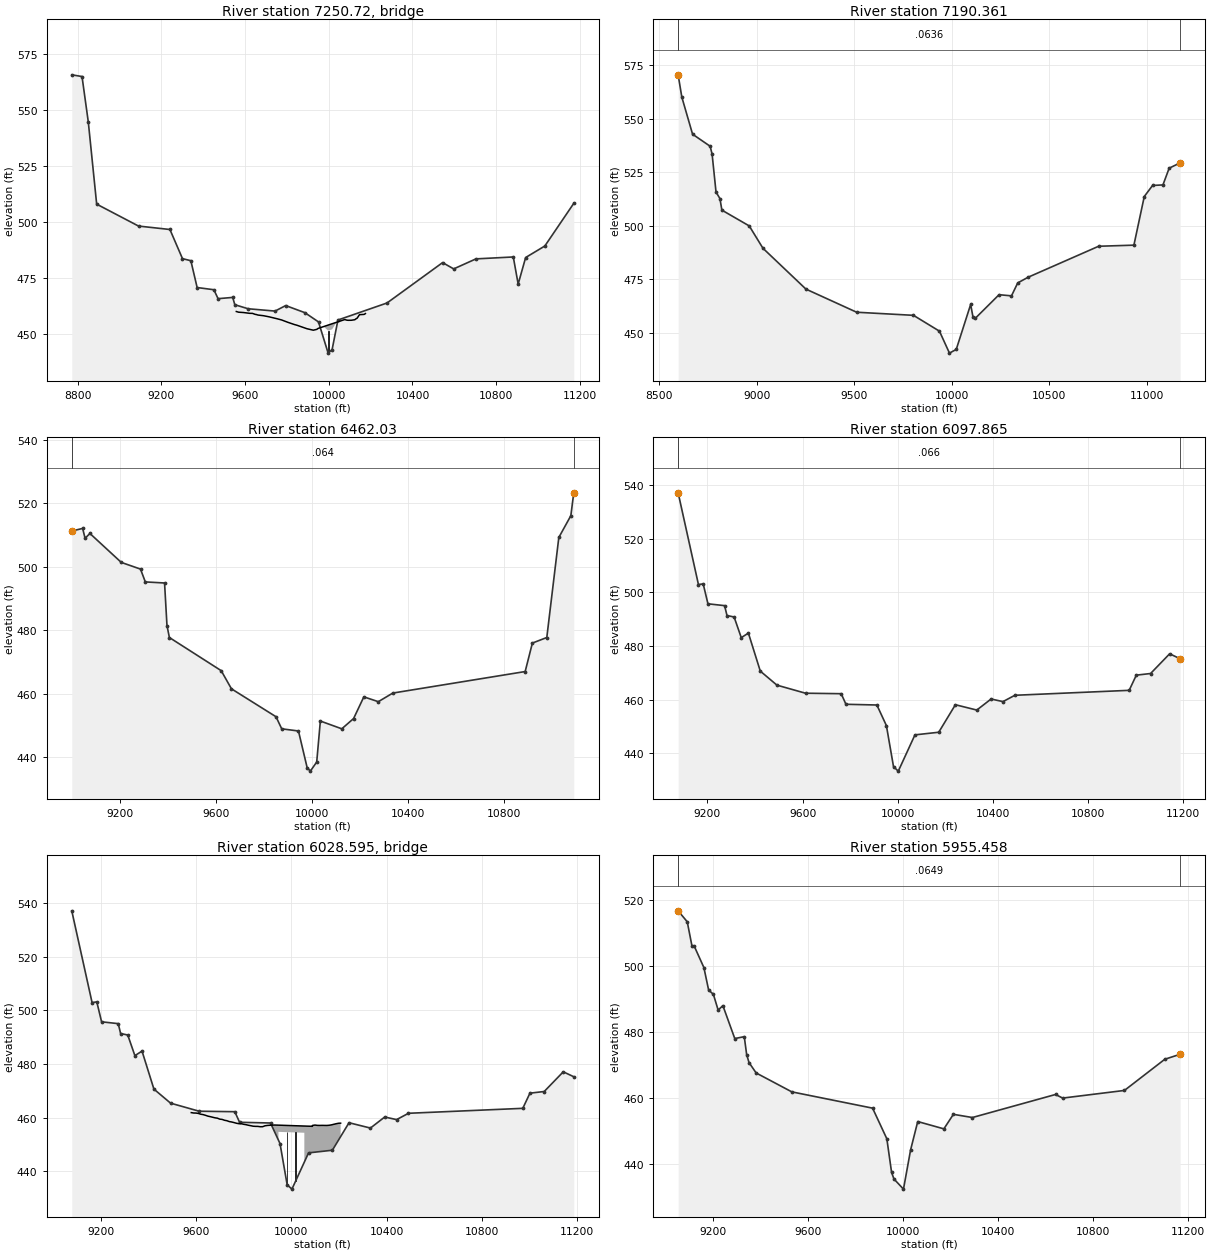
Type RM Length L Ch R = 3 , 7250.72,,,
BEGIN DESCRIPTION:
END DESCRIPTION:
Bridge Culvert--1,0,-1,-1, 0
Deck Dist Width WeirC Skew NumUp NumDn MinLoCord MaxHiCord MaxSubmerge Is_Ogee
53.306550,29.527500,2.6,0, 32, 33, , , 0.95, 0, 0,0,,
 9557.79 9568.62 9591.62 9622.03 9634.99 9648.26 9652.44 9661.54 9688.09 9714.64
 9754.46 9774.09 9804.50 9834.91 9847.38 9895.73 9925.95 9942.48 9942.48 9948.80
10051.0710051.0710076.2410086.5210091.9310107.3210124.5610128.3410135.5910146.62
10168.6910175.08
  459.87  459.57  459.42  459.06  459.04  458.59  458.55  458.29  457.99  457.50
  456.60  456.11  455.04  454.07  453.75  452.18  451.53  451.90  451.90  452.32
  455.50  455.50  456.28  456.00  455.95  455.96  456.21  456.51  456.91  458.46
  458.58  458.94
 -540.13 -540.43 -540.58 -540.94 -540.96 -541.41 -541.45 -541.71 -542.01 -542.50
 -543.40 -543.89 -544.96 -545.93 -546.25 -547.82 -548.47 -548.10  449.40  449.82
  453.00 -544.50 -543.72 -544.00 -544.05 -544.04 -543.79 -543.49 -543.09 -541.54
 -541.42 -541.06
 9557.79 9568.62 9591.62 9622.03 9634.99 9648.26 9652.44 9661.54 9688.09 9714.64
 9754.46 9774.09 9804.50 9834.91 9847.38 9895.73 9925.95 9941.77 9945.70 9945.70
 9948.8010054.3010054.3010076.2410086.5210091.9310107.3210124.5610128.3410135.59
10146.6210168.6910175.08
  459.87  459.57  459.42  459.06  459.04  458.59  458.55  458.29  457.99  457.50
  456.60  456.11  455.04  454.07  453.75  452.18  451.53  451.85  452.11  452.11
  452.32  455.60  455.60  456.28  456.00  455.95  455.96  456.21  456.51  456.91
  458.46  458.58  458.94
 -540.13 -540.43 -540.58 -540.94 -540.96 -541.41 -541.45 -541.71 -542.01 -542.50
 -543.40 -543.89 -544.96 -545.93 -546.25 -547.82 -548.47 -548.15 -547.89  449.61
  449.82  453.10 -544.40 -543.72 -544.00 -544.05 -544.04 -543.79 -543.49 -543.09
 -541.54 -541.42 -541.06
Pier Skew, UpSta & Num, DnSta & Num=  ,9996.78, 2 ,10000.00, 2 , 0 , 0 , 0 ,,
    4.00    4.00
 -546.19  453.81
    4.00    4.00
 -546.09  453.91
BR Coef=-1 , 0 , 0 ,, 0 ,,,0.8,0,1,0,
WSPro=,,,, 1 ,,,, 0 ,,,, 0 ,,,,-1 ,-1 ,-1 , 0 , 0 , 0 , 0 , 0
BC Design=,, 0 ,, 0 ,,,,,,

Type RM Length L Ch R = 1 ,7190.361,728.330800,728.330800,728.330800
XS GIS Cut Line= 6
564239.890097946812569.981197074564201.337137699812539.974260643
564153.594082147813373.307593986564451.436181784813662.046632573
564645.012570679813932.011910379564964.492441982 814817.84246248
#Sta/Elev= 30
8597.378570.44428616.247560.04958671.299542.74818761.446537.11188771.463533.4306
8791.496515.73938811.528512.70838821.545507.31628961.774499.94479031.889489.5329
 9252.25470.46729512.097 459.6799803.227458.23349936.307450.84789987.678440.5996
10022.44442.337310096.27463.311210108.58457.257510120.88456.922310241.76467.8592
10305.54467.321510337.43473.352810390.59476.006710752.02490.461610932.74490.9749
10985.89513.668311028.41518.829311081.57519.080111113.46526.888811169.63529.3687
#Mann= 3 , 0 , 0
8597.378  0.0636       08597.378  0.0636       011169.63  0.0636       0
#XS Ineff= 2 , 0
       0                               0
Bank Sta=8597.378,11169.63
Exp/Cntr=0.3,0.1

Type RM Length L Ch R = 1 , 6462.03,364.165400,364.165400,364.165400
XS GIS Cut Line= 6
564089.565997453812620.250295342564114.104902748812911.675769827
564068.126671664813215.075980047563986.364890732813390.814499327
563741.081375569813697.239620992563732.306869656814597.130697817
#Sta/Elev= 30
8999.078 511.2729044.385512.0984 9054.51508.99939074.654510.5066  9205.2501.3937
9285.238499.28499305.248495.24639385.398  494.919395.437481.50329405.477477.7323
9621.147467.29089663.799461.57569849.426452.77249873.115448.96969942.832 448.283
9979.009436.73599992.312435.641210018.82438.510310033.98451.420110123.21448.9726
10172.42 452.21410215.06459.0396 10275.3457.515910335.55460.231510886.63467.0116
10916.65 475.982 10976.7477.733611026.74509.250411076.78516.108511088.92523.3124
#Mann= 3 , 0 , 0
8999.078   0.064       08999.078   0.064       011088.92   0.064       0
#XS Ineff= 2 , 0
       0                               0
Bank Sta=8999.078,11088.92
Exp/Cntr=0.3,0.1

Type RM Length L Ch R = 1 ,6097.865,142.406500,142.406500,142.406500
XS GIS Cut Line= 4
563559.370801034812480.453434146563565.475533664812504.754965961
563533.669978142813929.060521498 563502.34677422814589.008024305
#Sta/Elev= 30
9076.673537.06739161.989502.88319181.994503.10279201.999495.68679272.017495.0007
9282.019491.32449312.027490.76059342.034483.07099372.042484.76269422.054470.5881
9492.072 465.3549612.101462.34799762.139462.16619782.144 458.2229912.176457.9511
9952.186450.28059982.194 434.928 10002.2433.295910072.22446.816110172.24447.7944
10242.26458.053910332.28 456.066 10392.3460.186210442.31459.216910492.32461.5776
10972.83463.420611002.87469.079311062.93469.697711143.02477.044111187.08475.2004
#Mann= 3 , 0 , 0
9076.673   0.066       09076.673   0.066       011187.08   0.066       0
#XS Ineff= 2 , 0
       0                               0
Bank Sta=9076.673,11187.08
Exp/Cntr=0.3,0.1

Type RM Length L Ch R = 3 ,6028.595,,,
BEGIN DESCRIPTION:
END DESCRIPTION:
Bridge Culvert--1,0,-1,-1, 0
Deck Dist Width WeirC Skew NumUp NumDn MinLoCord MaxHiCord MaxSubmerge Is_Ogee
50.698050,41.010400,2.6,0, 56, 56, , , 0.95, 0, 0,0,,
 9579.10 9588.92 9598.92 9608.92 9617.05 9618.92 9628.93 9638.93 9648.93 9658.93
 9668.93 9678.93 9688.94 9698.94 9708.94 9718.94 9728.94 9738.95 9748.95 9758.95
 9768.95 9778.95 9788.96 9798.96 9808.96 9818.96 9828.96 9838.97 9848.97 9858.97
 9868.97 9878.97 9888.97 9898.98 9908.98 9918.98 9928.87 9945.54 9945.5410054.46
10054.4610088.1610089.0110099.0110109.0210119.0210129.0210131.4410139.0210149.02
10159.0310169.0310179.0310189.0310199.0310206.92
  461.82  461.68  461.66  461.52  461.28  461.23  461.08  460.82  460.51  460.32
  460.10  459.88  459.75  459.39  459.29  458.97  458.80  458.48  458.33  458.11
  457.86  457.70  457.70  457.48  457.33  457.12  456.95  456.76  456.70  456.69
  456.56  456.57  456.91  457.04  457.11  457.16  457.20  457.15  457.15  456.82
  456.82  456.72  457.05  457.19  457.07  457.05  457.07  457.07  457.05  457.04
  457.11  457.27  457.49  457.70  457.87  457.89
 -538.18 -538.32 -538.34 -538.48 -538.72 -538.77 -538.92 -539.18 -539.49 -539.68
 -539.90 -540.12 -540.25 -540.61 -540.71 -541.03 -541.20 -541.52 -541.67 -541.89
 -542.14 -542.30 -542.30 -542.52 -542.67 -542.88 -543.05 -543.24 -543.30 -543.31
 -543.44 -543.43 -543.09 -542.96 -542.89 -542.84 -542.80 -542.85  454.65  454.32
 -543.18 -543.28 -542.95 -542.81 -542.93 -542.95 -542.93 -542.93 -542.95 -542.96
 -542.89 -542.73 -542.51 -542.30 -542.13 -542.11
 9579.10 9588.92 9598.92 9608.92 9617.05 9618.92 9628.93 9638.93 9648.93 9658.93
 9668.93 9678.93 9688.94 9698.94 9708.94 9718.94 9728.94 9738.95 9748.95 9758.95
 9768.95 9778.95 9788.96 9798.96 9808.96 9818.96 9828.96 9838.97 9848.97 9858.97
 9868.97 9878.97 9888.97 9898.98 9908.98 9918.98 9928.87 9945.54 9945.5410054.46
10054.4610088.1610089.0110099.0110109.0210119.0210129.0210131.4410139.0210149.02
10159.0310169.0310179.0310189.0310199.0310206.92
  461.82  461.68  461.66  461.52  461.28  461.23  461.08  460.82  460.51  460.32
  460.10  459.88  459.75  459.39  459.29  458.97  458.80  458.48  458.33  458.11
  457.86  457.70  457.70  457.48  457.33  457.12  456.95  456.76  456.70  456.69
  456.56  456.57  456.91  457.04  457.11  457.16  457.20  457.15  457.15  456.82
  456.82  456.72  457.05  457.19  457.07  457.05  457.07  457.07  457.05  457.04
  457.11  457.27  457.49  457.70  457.87  457.89
 -538.18 -538.32 -538.34 -538.48 -538.72 -538.77 -538.92 -539.18 -539.49 -539.68
 -539.90 -540.12 -540.25 -540.61 -540.71 -541.03 -541.20 -541.52 -541.67 -541.89
 -542.14 -542.30 -542.30 -542.52 -542.67 -542.88 -543.05 -543.24 -543.30 -543.31
 -543.44 -543.43 -543.09 -542.96 -542.89 -542.84 -542.80 -542.85  454.65  454.32
 -543.18 -543.28 -542.95 -542.81 -542.93 -542.95 -542.93 -542.93 -542.95 -542.96
 -542.89 -542.73 -542.51 -542.30 -542.13 -542.11
Pier Skew, UpSta & Num, DnSta & Num=  ,9981.35, 2 ,9981.35, 2 , 0 , 0 , 0 ,,
    3.00    3.00
 -542.96  457.04
    3.00    3.00
 -542.96  457.04
Pier Skew, UpSta & Num, DnSta & Num=  ,10018.65, 2 ,10018.65, 2 , 0 , 0 , 0 ,,
    3.00    3.00
 -543.07  456.93
    3.00    3.00
 -543.07  456.93
BR Coef=-1 , 0 , 0 ,, 0 ,,,0.8,0,1,0,
WSPro=,,,, 1 ,,,, 0 ,,,, 0 ,,,,-1 ,-1 ,-1 , 0 , 0 , 0 , 0 , 0
BC Design=,, 0 ,, 0 ,,,,,,

Type RM Length L Ch R = 1 ,5955.458,288.349300,288.349300,288.349300
XS GIS Cut Line= 4
 563386.64500599812477.016104889563389.433866978 812488.08829926
563410.267200351813668.643854812563405.951062262814589.419971779
#Sta/Elev= 30
9053.118516.80079091.452513.47269111.455506.06429121.457505.98139161.463499.5739
9181.466492.73669201.469491.44499221.472486.66229241.475488.00499291.483478.0077
9331.489478.58059341.491473.14019351.493 470.7059381.497467.55489531.521461.8156
9871.573456.86789931.583447.55879951.586437.33189961.587435.350210001.59432.2733
 10031.6444.1957 10061.6452.800210171.62450.579110211.63454.990710291.63454.0233
10641.64461.021510671.64459.925810931.64462.247811101.64471.721411166.06473.2325
#Mann= 3 , 0 , 0
9053.118  0.0649       09053.118  0.0649       011166.06  0.0649       0
#XS Ineff= 2 , 0
       0                               0
Bank Sta=9053.118,11166.06
Exp/Cntr=0.3,0.1

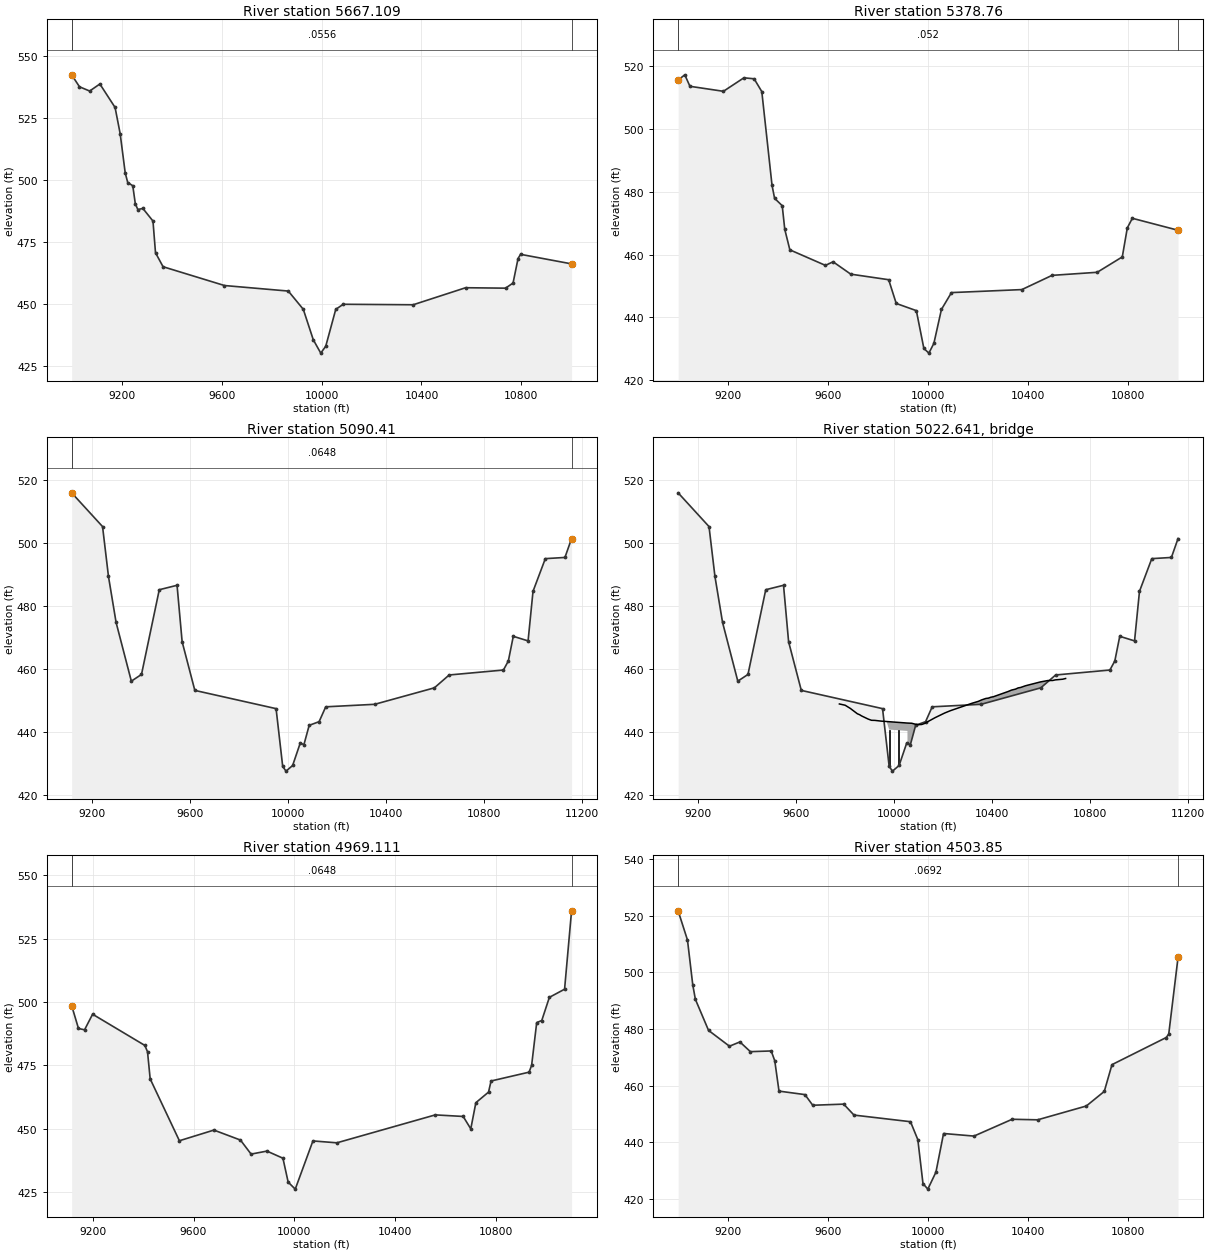
Type RM Length L Ch R = 1 ,5667.109,288.349300,288.349300,288.349300
XS GIS Cut Line= 6
563019.774106223812424.265836337 563076.64883572812751.171265059
563113.612621711813151.023294215563118.367030392813358.034687583
563110.682984912814126.476194033563116.388597011814419.242123623
#Sta/Elev= 30
8999.032 542.4759030.384 537.6429071.188535.93029111.992 538.7729172.918529.2887
9193.224518.7419 9213.45502.87359223.562 498.9649243.787497.67549253.899490.4056
9264.011488.06049284.236488.49589324.685483.40379334.783470.60869365.007464.9525
9610.941457.35679866.627455.1195 9926.63447.74919966.631435.44989996.632430.0467
10016.63432.852810056.64447.735310086.64449.782510366.68449.584410576.68456.4667
10736.68456.290710766.69458.369210786.69468.272510796.69469.959511000.99466.1024
#Mann= 3 , 0 , 0
8999.032  0.0556       08999.032  0.0556       011000.99  0.0556       0
#XS Ineff= 2 , 0
       0                               0
Bank Sta=8999.032,11000.99
Exp/Cntr=0.3,0.1

Type RM Length L Ch R = 1 , 5378.76,288.349300,288.349300,288.349300
XS GIS Cut Line= 6
562644.619033876812439.133920495562692.814747041812629.948364781
562735.392137916812823.598351714562806.616218477813224.879322717
562889.928153742813950.628848805562934.398758283814417.207948955
#Sta/Elev= 30
 8999.04515.64019025.719517.31399046.347513.65419180.429512.05929262.453516.3642
9303.408516.04499334.125511.9693 9375.08482.07979385.319477.94039415.909475.5732
9426.088468.03719446.447461.50359588.961 456.548  9619.5457.69479690.412453.7479
9842.188451.97639872.451444.40689953.015442.11399983.149430.061610003.23428.5657
10023.32431.703710053.45442.490910093.63447.868510375.58 448.82710496.41 453.364
10677.32454.342910777.77459.251810797.86468.500110817.95471.565111000.98467.7531
#Mann= 3 , 0 , 0
 8999.04   0.052       0 8999.04   0.052       011000.98   0.052       0
#XS Ineff= 2 , 0
       0                               0
Bank Sta=8999.04,11000.98
Exp/Cntr=0.3,0.1

Type RM Length L Ch R = 1 , 5090.41,121.299100,121.299100,121.299100
XS GIS Cut Line= 6
562261.646299481812670.024365887562458.878311425 813389.32093814
562673.808867007813625.779271498562742.556417137 814011.44165498
562796.335575968814469.844961628562802.734383702814591.997820824
#Sta/Elev= 30
9117.479515.84879243.609505.14039267.806489.30059298.914474.70239361.128456.0856
9402.605458.22049475.189485.09969547.773486.50739568.511468.59629620.356453.1537
9952.083447.36649979.111429.02719992.624427.537610019.65429.324910050.84 436.474
 10065.7435.923610087.22442.069210127.76443.232710154.79447.943510354.76448.7419
10598.33 453.96710658.74458.047310880.25459.616410900.39462.496210920.53 470.319
10980.94468.862911001.07484.586111051.33 494.96511131.44495.341411158.48501.3347
#Mann= 3 , 0 , 0
9117.479  0.0648       09117.479  0.0648       011158.48  0.0648       0
#XS Ineff= 2 , 0
       0                               0
Bank Sta=9117.479,11158.48
Exp/Cntr=0.3,0.1

Type RM Length L Ch R = 3 ,5022.641,,,
BEGIN DESCRIPTION:
END DESCRIPTION:
Bridge Culvert--1,0,-1,-1, 0
Deck Dist Width WeirC Skew NumUp NumDn MinLoCord MaxHiCord MaxSubmerge Is_Ogee
40.964550,39.370000,2.6,0, 40, 40, , , 0.95, 0, 0,0,,
 9775.90 9799.33 9820.19 9849.46 9858.75 9865.80 9893.18 9906.87 9920.56 9946.19
 9946.1910053.8110053.8110071.1510084.8410098.5310112.2310122.3010166.6210205.24
10228.8310318.7510342.8910356.5910373.9110384.1010394.2110404.3210464.9910478.55
10495.3210505.4310515.5410535.7610596.4010626.7210646.9310657.0310687.3410699.46
  448.85  448.45  447.45  445.73  445.43  445.08  444.06  443.67  443.64  443.41
  443.41  442.79  442.79  442.73  442.45  442.28  442.34  442.62  444.50  445.96
  446.71  449.11  449.67  450.14  450.60  450.70  450.99  451.14  452.81  453.25
  453.57  453.94  454.08  454.63  455.84  456.28  456.30  456.49  456.70  456.93
 -551.15 -551.55 -552.55 -554.27 -554.57 -554.92 -555.94 -556.33 -556.36 -556.59
  440.91  440.29 -557.21 -557.27 -557.55 -557.72 -557.66 -557.38 -555.50 -554.04
 -553.29 -550.89 -550.33 -549.86 -549.40 -549.30 -549.01 -548.86 -547.19 -546.75
 -546.43 -546.06 -545.92 -545.37 -544.16 -543.72 -543.70 -543.51 -543.30 -543.07
 9775.90 9799.33 9820.19 9849.46 9858.75 9865.80 9893.18 9906.87 9920.56 9946.19
 9946.1910053.8110053.8110071.1510084.8410098.5310112.2310122.3010166.6210205.24
10228.8310318.7510342.8910356.5910373.9110384.1010394.2110404.3210464.9910478.55
10495.3210505.4310515.5410535.7610596.4010626.7210646.9310657.0310687.3410699.46
  448.85  448.45  447.45  445.73  445.43  445.08  444.06  443.67  443.64  443.41
  443.41  442.79  442.79  442.73  442.45  442.28  442.34  442.62  444.50  445.96
  446.71  449.11  449.67  450.14  450.60  450.70  450.99  451.14  452.81  453.25
  453.57  453.94  454.08  454.63  455.84  456.28  456.30  456.49  456.70  456.93
 -551.15 -551.55 -552.55 -554.27 -554.57 -554.92 -555.94 -556.33 -556.36 -556.59
  440.91  440.29 -557.21 -557.27 -557.55 -557.72 -557.66 -557.38 -555.50 -554.04
 -553.29 -550.89 -550.33 -549.86 -549.40 -549.30 -549.01 -548.86 -547.19 -546.75
 -546.43 -546.06 -545.92 -545.37 -544.16 -543.72 -543.70 -543.51 -543.30 -543.07
Pier Skew, UpSta & Num, DnSta & Num=  ,9981.56, 2 ,9981.56, 2 , 0 , 0 , 0 ,,
    3.00    3.00
 -556.79  443.21
    3.00    3.00
 -556.79  443.21
Pier Skew, UpSta & Num, DnSta & Num=  ,10018.44, 2 ,10018.44, 2 , 0 , 0 , 0 ,,
    3.00    3.00
 -557.00  443.00
    3.00    3.00
 -557.00  443.00
BR Coef=-1 , 0 , 0 ,, 0 ,,,0.8,0,1,0,
WSPro=,,,, 1 ,,,, 0 ,,,, 0 ,,,,-1 ,-1 ,-1 , 0 , 0 , 0 , 0 , 0
BC Design=,, 0 ,, 0 ,,,,,,

Type RM Length L Ch R = 1 ,4969.111,465.261700,465.261700,465.261700
XS GIS Cut Line= 5
562128.989763304812739.340393804562355.116737396813425.026956692
562370.568126231813475.026956663562579.769515127813687.700567797
 562672.18796438814592.555711523
#Sta/Elev= 30
9116.712498.60469143.731 489.5719167.832 489.0489199.761495.20169406.975482.8835
9417.505480.39159428.034469.69169543.862445.28029680.748449.48789786.046445.5458
9828.165440.01239891.028441.19479954.416438.38659975.181428.957110003.24426.1909
10073.37445.207510168.32444.461510558.59455.480810669.16454.865310699.32 449.971
10719.42 460.29210769.68464.468410779.73468.856110930.51 472.34110940.56475.0405
10960.67491.897310980.77492.721111010.93501.857311071.24505.073611098.94535.9939
#Mann= 3 , 0 , 0
9116.712  0.0648       09116.712  0.0648       011098.94  0.0648       0
#XS Ineff= 2 , 0
       0                               0
Bank Sta=9116.712,11098.94
Exp/Cntr=0.3,0.1

Type RM Length L Ch R = 1 , 4503.85,465.261700,465.261700,465.261700
XS GIS Cut Line= 6
561739.160923515812679.491862439561839.618071766812994.498689084
561931.784642355813331.155495715562010.509670348813677.907356043
562095.728049946814119.181334176562219.795697621814620.997416375
#Sta/Elev= 30
8999.042521.68689036.484511.37979057.573495.60189068.118 490.4569120.841479.4923
9204.611473.90789246.482475.41789288.353 471.9869371.799472.23339386.059 468.756
9402.982458.06199506.929456.82719538.088453.07189662.073453.46659703.248449.6025
9929.534447.26529958.933440.93029979.581425.4318    9999423.470510031.46429.4737
10061.97443.102110183.79442.191510336.64448.124510438.81447.932210633.71452.8079
 10705.6457.955510736.41467.403610953.35476.9607 10963.7478.182611000.94 505.221
#Mann= 3 , 0 , 0
8999.042  0.0692       08999.042  0.0692       011000.94  0.0692       0
#XS Ineff= 2 , 0
       0                               0
Bank Sta=8999.042,11000.94
Exp/Cntr=0.3,0.1