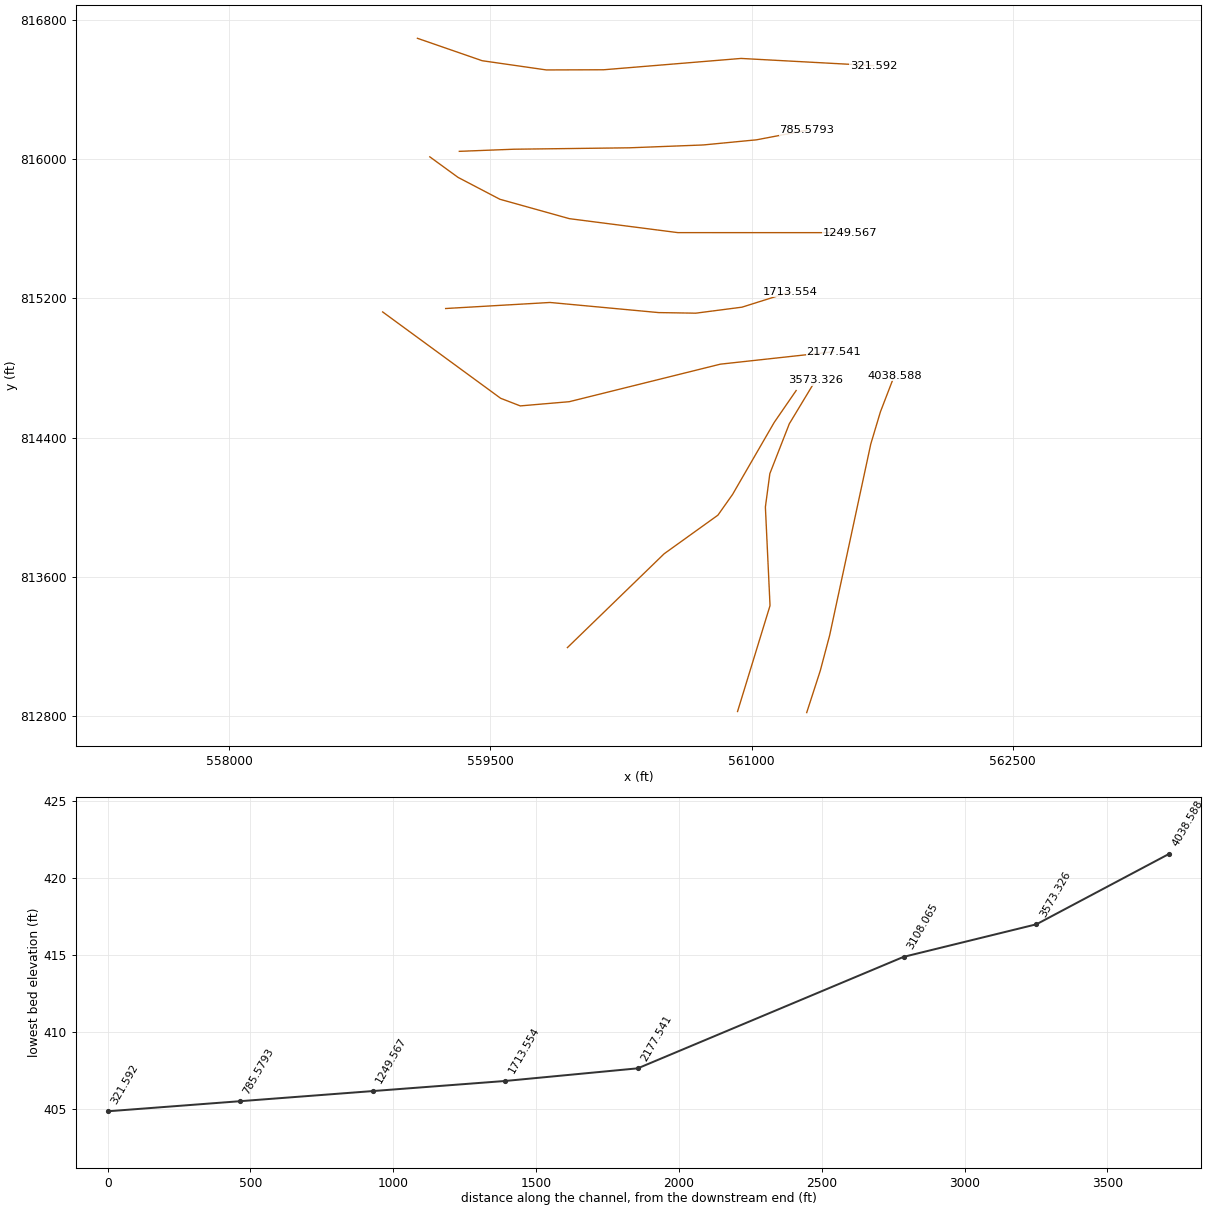
HEC-RAS study 11081_ras.prj: 11081

--- 11081_ras.g01 (geometry) --- (continued)

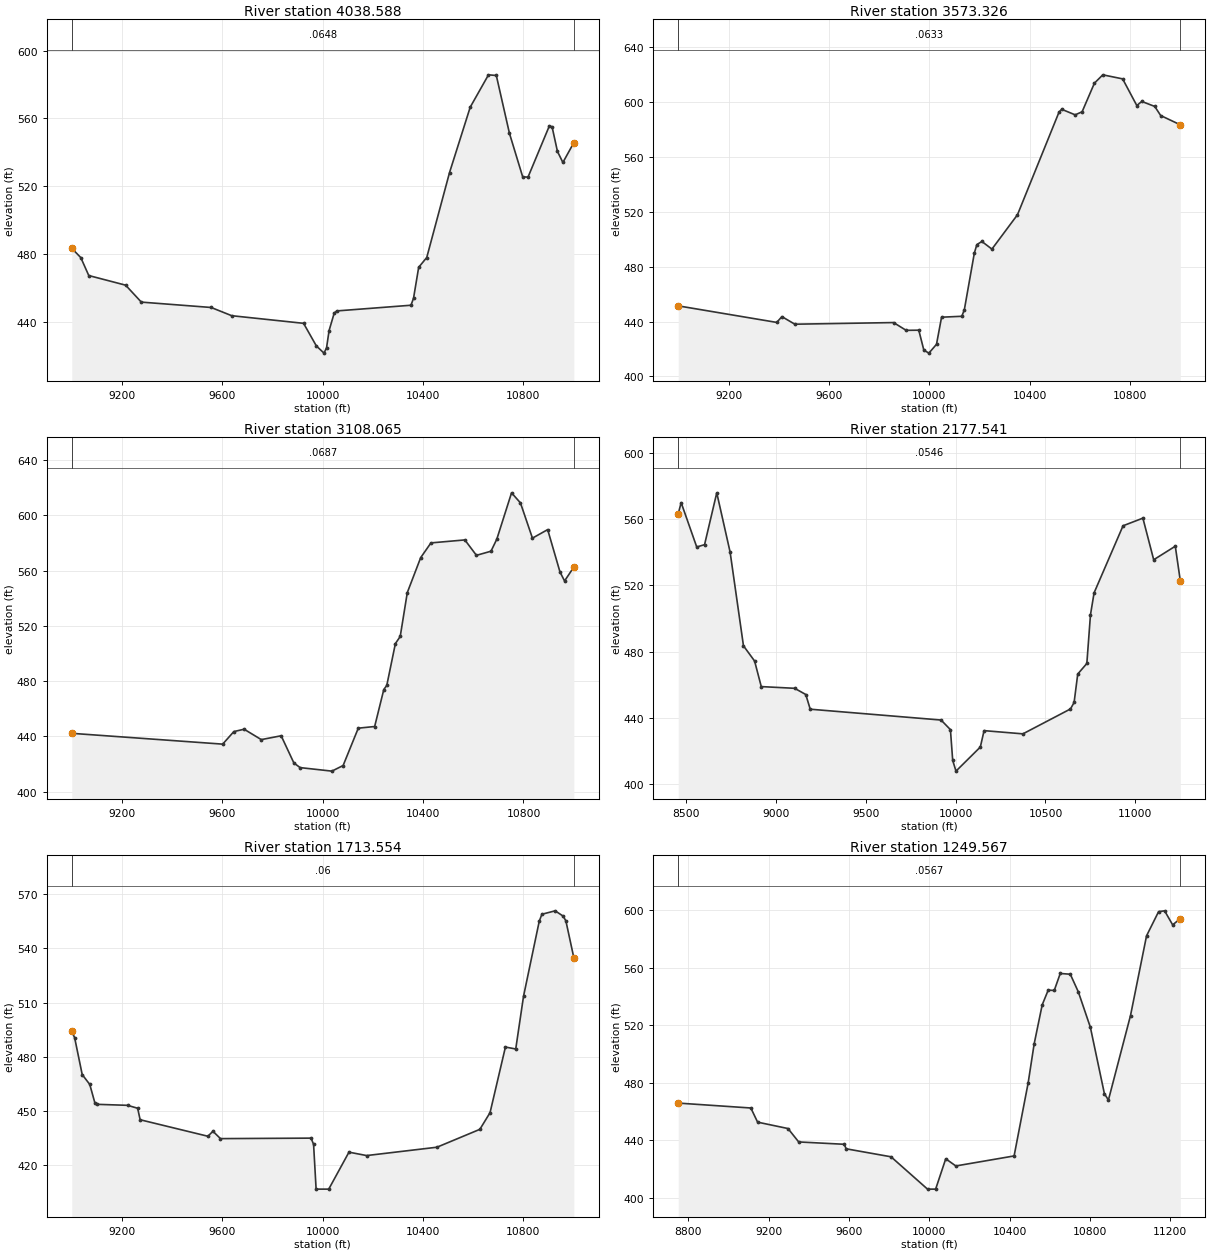
Type RM Length L Ch R = 1 ,4038.588,465.261700,465.261700,465.261700
XS GIS Cut Line= 6
 561316.97409107812820.880228026561394.960391415813061.666193631
561448.698174783813264.458109831561684.795557524814362.679771602
561740.258820619814547.973532398561819.995906259814755.215952861
#Sta/Elev= 30
8999.024483.38169035.088477.89079066.797467.3248  9213.8461.64129276.364451.6563
9554.857448.48729636.879443.63849923.326439.14559974.258425.819210004.77421.5686
10014.93424.718310025.09434.907610045.42445.161610055.58446.454110351.56 449.811
10361.77453.945810382.26 472.18310414.44477.954210505.35528.071210587.84566.6371
10660.65585.689110691.85585.303210744.22551.177210796.92525.576210818.12525.3275
10903.47555.623110914.19 555.02910935.63540.503610957.28533.992411000.98545.6996
#Mann= 3 , 0 , 0
8999.024  0.0648       08999.024  0.0648       011000.98  0.0648       0
#XS Ineff= 2 , 0
       0                               0
Bank Sta=8999.024,11000.98
Exp/Cntr=0.3,0.1

Type RM Length L Ch R = 1 ,3573.326,465.261600,465.261600,465.261600
XS GIS Cut Line= 6
560919.787926928812827.024816278561106.339565946813435.093671051
561079.685132338814001.097776547 561105.31849521814193.253401635
561217.205813518814479.544031827561368.476610065814730.031940807
#Sta/Elev= 30
8999.063451.4675 9391.74439.39839412.441443.61399464.014438.09149857.672439.2847
9907.842433.61989958.158433.73119978.347419.18559998.535 416.99210028.81423.4378
10048.99443.202510129.62 443.86910139.65448.485810179.71489.985310189.71496.1513
10209.72498.445210249.75 492.879 10351.7517.938710517.29 592.78910527.92594.8683
10581.73590.820210609.38593.051410658.52613.950710691.91620.007610770.97617.0522
10827.46597.616110847.34600.590910899.01596.951910922.66590.309411000.93583.5473
#Mann= 3 , 0 , 0
8999.063  0.0633       08999.063  0.0633       011000.93  0.0633       0
#XS Ineff= 2 , 0
       0                               0
Bank Sta=8999.063,11000.93
Exp/Cntr=0.3,0.1

Type RM Length L Ch R = 1 ,3108.065,930.523400,930.523400,930.523400
XS GIS Cut Line= 6
559942.869088198813194.093374194 560498.52900657813732.994471726
560807.061230473813954.522382756560891.159558607814073.596842564
561130.404165759814487.295082819561256.388173105814670.175426174
#Sta/Elev= 30
8999.061442.23289600.674434.41269645.306443.49879686.318445.20399754.673437.6873
9833.938440.46259884.619420.79779909.517417.421110036.15414.876710080.96418.9247
10141.41445.960410206.72447.163410243.18473.942110255.04476.902310289.36 507.178
10308.65512.330310336.84544.080510390.27569.388410431.08580.039610566.28582.1964
 10612.5571.045310670.55574.021810693.77582.7537 10752.5616.278110787.99608.9906
 10835.8583.487510896.54 589.65810945.54559.054710963.86552.495511000.89562.5521
#Mann= 3 , 0 , 0
8999.061  0.0687       08999.061  0.0687       011000.89  0.0687       0
#XS Ineff= 2 , 0
       0                               0
Bank Sta=8999.061,11000.89
Exp/Cntr=0.3,0.1

Type RM Length L Ch R = 1 ,2177.541,463.987300,463.987300,463.987300
XS GIS Cut Line= 6
558881.887102157815121.568515658559559.259578466814625.765702248
559672.120954841814581.967468157559953.421968132814606.159604847
560821.161411941814821.675856754561472.915502876814893.051037014
#Sta/Elev= 30
8455.036563.40288471.286 570.1588558.034543.30028601.604544.71398669.567576.0889
8743.922540.21438818.277 483.495 8880.24474.28578917.418458.80559103.306457.7717
9165.268454.01939190.053445.12229918.728438.56399970.763432.74449983.437 414.156
10001.76407.643610137.33422.222510158.17432.1521 10374.4430.205210639.27445.2704
10659.52449.221810679.78 466.41110730.41 472.79510750.63502.250210770.79515.5508
10932.04556.140311042.55560.765211102.72535.575311222.97543.780611250.94522.8552
#Mann= 3 , 0 , 0
8455.036  0.0546       08455.036  0.0546       011250.94  0.0546       0
#XS Ineff= 2 , 0
       0                               0
Bank Sta=8455.036,11250.94
Exp/Cntr=0.3,0.1

Type RM Length L Ch R = 1 ,1713.554,463.987300,463.987300,463.987300
XS GIS Cut Line= 6
 559243.59546318815141.242686324 559843.07363865815175.947640594
560466.390977324815117.828876779 560680.00657389 815114.48284488
560945.542871567815149.005546777561224.487333284815236.826460021
#Sta/Elev= 30
8999.044494.1716 9010.51490.5474 9040.67470.17519070.831464.71649090.937454.6494
9100.991453.71639221.563453.16979261.659451.55149271.683445.19789541.912436.0622
9561.912438.82829591.913434.75519953.125435.02989963.201431.60829973.277406.8233
10023.66406.823310104.29427.270210174.69425.385810455.09430.000710626.17439.8913
10666.81449.102210728.13485.397110769.26484.330410800.38 513.52210862.93554.9359
10873.51558.840810926.37560.7383 10958.4557.811510969.18555.184511000.95534.7792
#Mann= 3 , 0 , 0
8999.044    0.06       08999.044    0.06       011000.95    0.06       0
#XS Ineff= 2 , 0
       0                               0
Bank Sta=8999.044,11000.95
Exp/Cntr=0.3,0.1

Type RM Length L Ch R = 1 ,1249.567,463.987400,463.987400,463.987400
XS GIS Cut Line= 6
559152.601388211816012.241026672559314.807930558815894.207791224
559555.043895385815768.604469583559954.038662146815657.223271313
560577.454109451815577.011058971561563.219426132815576.903092136
#Sta/Elev= 30
8749.029466.01689110.854462.60159144.534452.75639296.014448.31489349.281438.9951
 9575.85437.36559586.059434.21149809.358428.65799991.297406.167210031.72406.1672
10082.05427.276810132.31422.283710422.71429.253910492.71480.011310522.72507.2268
10562.72534.333410592.72544.613810622.72544.348810652.72556.184910702.73555.6506
10742.73543.394710802.73518.768810872.74472.523210892.74468.147111002.75526.8928
11082.75582.379911142.75599.198111172.75599.756611212.75590.012811250.97594.2805
#Mann= 3 , 0 , 0
8749.029  0.0567       08749.029  0.0567       011250.97  0.0567       0
#XS Ineff= 2 , 0
       0                               0
Bank Sta=8749.029,11250.97
Exp/Cntr=0.3,0.1

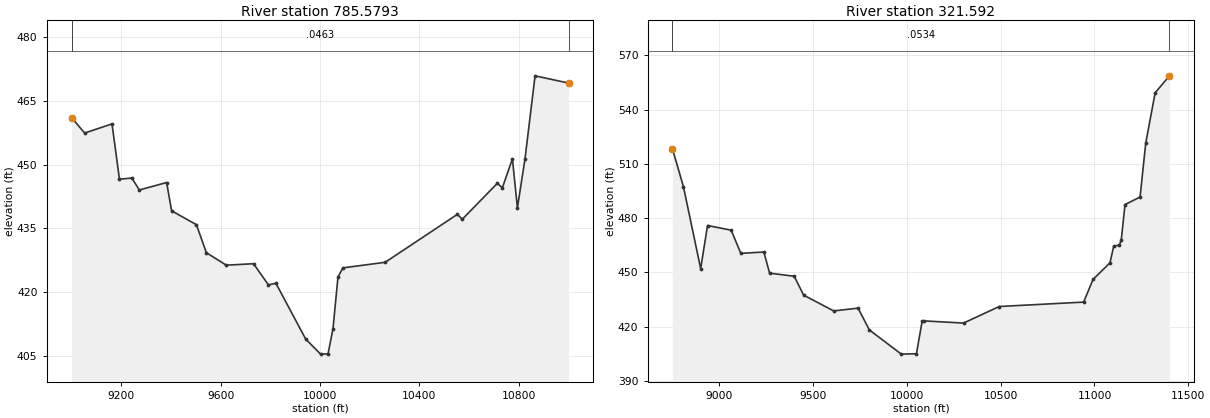
Type RM Length L Ch R = 1 ,785.5793,463.987300,463.987300,463.987300
XS GIS Cut Line= 6
559322.102692731816043.800607349559634.498217813816055.948512876
560298.914690635816064.083919617 560722.63216234816080.423039553
561029.122971646816110.001205005 561316.65079685 816164.78644275
#Sta/Elev= 30
8999.015461.00989051.969457.39559162.085  459.549192.108446.55349242.129446.8412
9272.142444.02429382.165445.78429402.166439.13879502.174435.89179542.177429.3167
9622.183 426.3899732.191426.72699792.195421.75379822.198422.14499942.207 409.056
10002.22 405.51110032.23405.566810052.24411.478210072.26423.595810092.27425.7539
10262.38427.059910553.04438.3115 10573.1437.1692 10714.1445.591110734.36444.5406
10774.89451.311410795.15439.851510825.55451.317110866.15470.819711000.97469.1198
#Mann= 3 , 0 , 0
8999.015  0.0463       08999.015  0.0463       011000.97  0.0463       0
#XS Ineff= 2 , 0
       0                               0
Bank Sta=8999.015,11000.97
Exp/Cntr=0.3,0.1

Type RM Length L Ch R = 1 , 321.592,0.000000,0.000000,0.000000
XS GIS Cut Line= 6
559081.546574503816692.959164485559453.543062985816564.136457413
559821.975371629816511.272570193560150.887060136816512.264920682
560939.909678221816577.315957233561700.896146059816536.168183967
#Sta/Elev= 30
8749.028518.41168807.549497.49268899.721452.11368936.326475.95859062.215473.3805
9113.871460.56569236.817461.2982 9267.29  449.639398.615447.8962 9448.83437.4599
9609.118428.7368 9739.13430.28089799.179418.24169969.793404.854810050.43 405.059
10080.67422.916810090.75423.228710301.67422.023810492.11431.1757 10942.3 433.619
10992.38446.154711082.56455.321111102.65464.530411132.78465.143811142.83467.9159
11162.92487.522311243.27491.7103 11273.4521.502711323.62549.324111399.86558.7048
#Mann= 3 , 0 , 0
8749.028  0.0534       08749.028  0.0534       011399.86  0.0534       0
#XS Ineff= 2 , 0
       0                               0
Bank Sta=8749.028,11399.86
Exp/Cntr=0.3,0.1